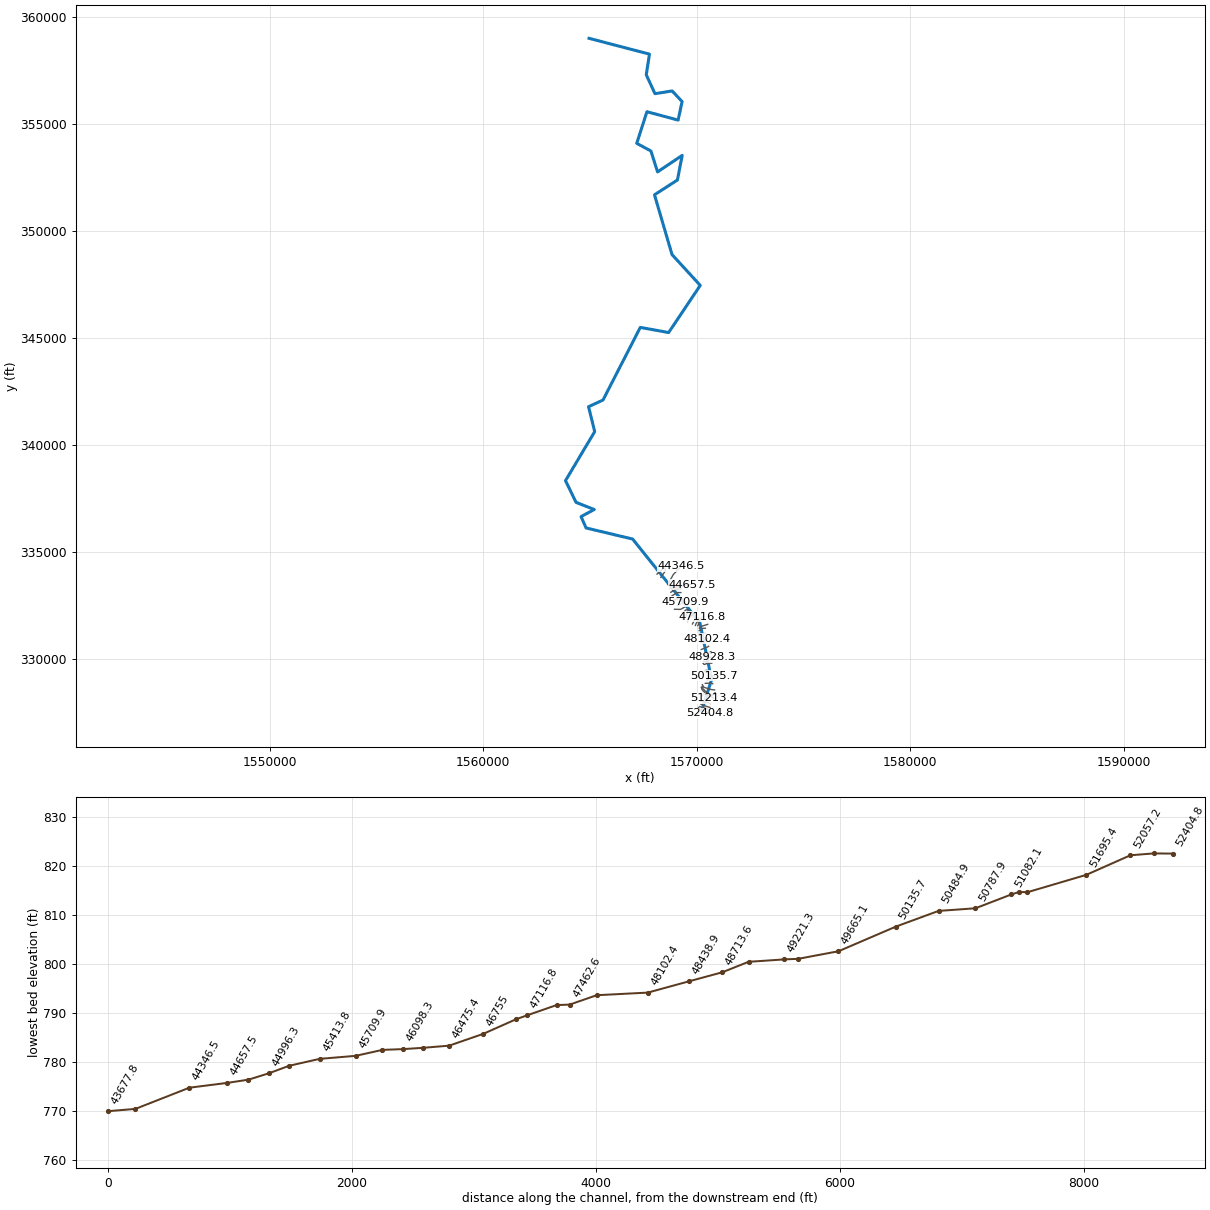
--- SNCHOCRK.prj (project) ---

Proj Title=SNCHOCRK
Current Plan=p01
Default Exp/Contr=0,0
English Units
Geom File=g01
Flow File=f01
Plan File=p01
BEGIN DESCRIPTION:
END DESCRIPTION:
DSS Export Rating Curves= 0
DSS Export Rating Curve Sorted= 0
DSS Export Volume Flow Curves= 0
DXF OffsetX= 0
DXF OffsetY= 0
DXF ScaleX= 0
DXF ScaleY= 0

--- SNCHOCRK.p01 (plan) ---

Plan Title=Floodplain
Program Version=4.00
Geom File=g01
Flow File=f01
K Sum by GR=0
Std Step Tol=0.01
Critical Tol=0.01
Num of Std Step Trials=20
Max Error Tol=0.3
Flow Tol Ratio=0.001
Split Flow NTrial=30
Split Flow Tol=0.02
Split Flow Ratio=0.02
Log Output Level=0
Friction Slope Method=1
Unsteady Friction Slope Method=2
Unsteady Bridges Friction Slope Method=1
Global Log Level=0
CheckData=False
Run HTab=0
Run UNet=0
Run PostProcess=0
UNET Theta=0
UNET Theta Warmup=0
UNET ZTol=0
UNET ZSATol=0
UNET MxIter=0
UNET MaxInSteps=0
UNET DtIC=0
UNET DtMin=0
UNET MaxCRTS=0
UNET WFStab=0
UNET SFStab=0
UNET WFX=0
UNET SFX=0
UNET DSS MLevel=0
UNET DZMax Abort=0
UNET Convert EG Bridges=0
UNET Use Existing IB Tables=0
UNET Froude Limit=0
UNET Froude Power=0
Write IC File=0
Echo Input=False
Echo Output=False
Write Detailed=0

--- SNCHOCRK.f01 (steady flow) ---

Flow Title=NFF Regression Equation
Program Version=4.10
Number of Profiles= 1
Profile Names=P100yr
River Rch & RM=SNCHOCRK,Main            ,52404.8
951.3075
River Rch & RM=SNCHOCRK,Main            ,49665.1
1135.414
River Rch & RM=SNCHOCRK,Main            ,46755
1371.893
River Rch & RM=SNCHOCRK,Main            ,45928.5
1457.742
River Rch & RM=SNCHOCRK,Main            ,43904.7
1616.723
River Rch & RM=SNCHOCRK,Main            ,42762.4
1777.986
River Rch & RM=SNCHOCRK,Main            ,41224.5
2014.752
River Rch & RM=SNCHOCRK,Main            ,38879.2
2085.392
River Rch & RM=SNCHOCRK,Main            ,32116.9
2294.128
River Rch & RM=SNCHOCRK,Main            ,29501.7
2543.876
River Rch & RM=SNCHOCRK,Main            ,23254.2
3171.216
River Rch & RM=SNCHOCRK,Main            ,17019.3
4222.779
River Rch & RM=SNCHOCRK,Main            ,508.7
4477.337
Boundary for River Rch & Prof#=SNCHOCRK,Main            , 1
Up Type= 0
Dn Type= 3
Dn Slope=0.002
DSS Import GetInterval= 0
DSS Import GetPeak= 0
DSS Import FillOption= 0

--- SNCHOCRK.g01 (geometry) ---

Geom Title=USGS 10m DEM
Program Version=4.10

River Reach=SNCHOCRK        ,Main
Reach XY= 30
      1570235.96      327568.387     1570691.888      329016.504
     1570145.056      331669.586     1566993.544      335590.176
     1564818.162      336107.208     1564579.348      336638.073
     1565200.464      336970.962     1564348.284      337303.748
     1563852.142      338321.174     1565219.526      340613.901
     1564931.764      341780.751     1565607.276      342091.348
     1567354.459      345490.667     1568680.549      345250.022
     1570161.693      347456.811     1568840.084      348897.145
     1568018.667      351694.353     1569092.848      352386.973
     1569315.303       353539.77     1568162.959      352765.959
     1567851.794      353744.705      1567187.29      354103.048
      1567665.51      355582.218      1569123.84      355190.488
     1569312.057      356054.855     1568847.409      356553.457
     1568040.833      356426.156     1567633.672        357307.8
     1567783.019      358276.648     1564955.817      359015.313

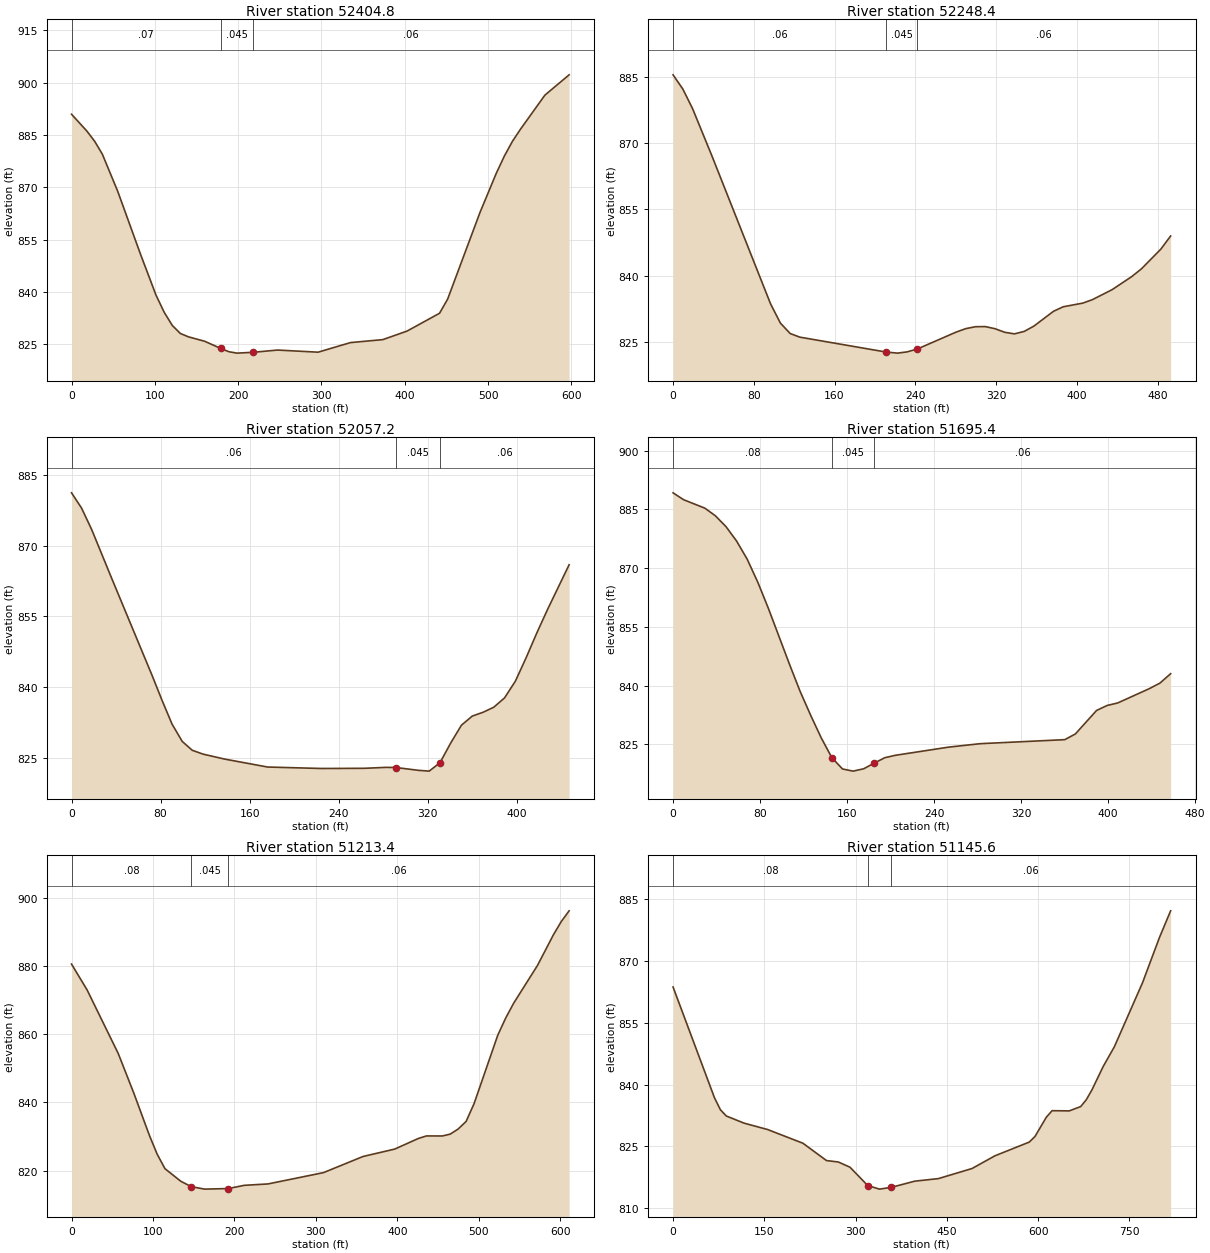
Type RM Length L Ch R = 1 ,52404.8 ,149.1,156.4,160.2
XS GIS Cut Line= 3
     1570080.522      327703.832      1570148.23      327628.311
     1570603.959      327432.999
#Sta/Elev= 30
       0  890.92    18.4   886.1    27.7  883.19    36.9  879.51    55.3  868.92
      83  850.66   101.4  839.07   111.2  834.17   120.9   830.4   130.6  828.09
   140.3  827.13   159.8  825.86   179.2  823.79   188.9  822.86   198.6  822.46
   218.1   822.7   247.3  823.34   295.9  822.73   334.8  825.48   373.6  826.33
   402.8  828.79   441.7  833.89   451.4  837.94   490.3  862.82   509.8  874.01
   519.5  878.95   529.2  883.17   538.9  886.66   568.1  896.39   597.2  902.22
#Mann= 3 , 0 , 0
       0     .07       0   179.2    .045       0   218.1     .06       0
Bank Sta=179.2,218.1
XS Rating Curve= 0 ,0
Exp/Cntr=0.3,0.1

Type RM Length L Ch R = 1 ,52248.4 ,194.7,191.2,188.9
XS GIS Cut Line= 2
     1570136.605      327750.107     1570607.525      327604.707
#Sta/Elev= 30
       0  885.39     9.7  882.17    19.3  877.77    38.7  866.96    96.6  833.63
   106.3   829.3     116  826.93   125.6  826.11     211 822.746   222.3   822.5
   231.9  822.78     242823.4359   280.2  827.23   289.9  828.03   299.6  828.47
   309.2   828.5   318.9  828.02   328.6  827.21   338.2  826.85   347.9  827.41
   357.6  828.63   376.9  831.96   386.6  832.98   405.9   833.8   415.5  834.59
   434.9  836.84   454.2  839.77   463.9  841.53   483.2     846   492.9  848.97
#Mann= 3 , 0 , 0
       0     .06       0     211    .045       0     242     .06       0
Bank Sta=211,242
XS Rating Curve= 0 ,0
Exp/Cntr=0.3,0.1

Type RM Length L Ch R = 1 ,52057.2 ,357,361.8,357.9
XS GIS Cut Line= 3
     1570197.709      327854.874     1570296.667      327810.603
     1570619.584      327709.041
#Sta/Elev= 30
       0  881.19       9  877.95    18.1  873.39    36.1  863.02    72.3  842.46
    81.3  837.14    90.3  832.09    99.4  828.43   108.4  826.55   118.1  825.73
   137.4  824.68   176.1  822.99   224.5  822.68   263.2  822.72   282.5  822.92
   291.5822.8829   311.5  822.29   321.2  822.12   330.9  823.89   340.5  828.07
   350.2  831.87   359.9   833.8   369.6  834.61   379.2  835.68   388.9  837.66
   398.6   841.2   408.2  846.14   417.9  851.45   427.6  856.47   446.9  865.92
#Mann= 3 , 0 , 0
       0     .06       0   291.5    .045       0   330.9     .06       0
Bank Sta=291.5,330.9
XS Rating Curve= 0 ,0
Exp/Cntr=0.3,0.1

Type RM Length L Ch R = 1 ,51695.4 ,476,482,471.5
XS GIS Cut Line= 2
     1570195.105      328018.936     1570635.209      327893.936
#Sta/Elev= 30
       0  889.22     9.7  887.46    29.2  885.31    38.9  883.36    48.7  880.58
    58.4  876.91    68.1  872.31    77.9   866.4    87.6  859.74   107.1   845.4
   116.8  838.52   126.6  832.35   136.3   826.6     146  821.57   155.8  818.68
   165.5  818.13   175.2  818.72     185  820.18   194.7  821.56   204.4  822.17
   253.1  824.25   282.3  825.14   360.2  826.17   369.9  827.62   389.4  833.63
   399.1   834.9   408.8  835.54     438  839.21   447.8  840.64   457.5  843.02
#Mann= 3 , 0 , 0
       0     .08       0     146    .045       0     185     .06       0
Bank Sta=146,185
XS Rating Curve= 0 ,0
Exp/Cntr=0.3,0.1

Type RM Length L Ch R = 1 ,51213.4 ,78.5,67.8,56.3
XS GIS Cut Line= 4
     1570239.376      328261.124     1570327.917      328334.041
      1570679.48      328219.457     1570781.042      328143.936
#Sta/Elev= 30
       0  880.55    19.1  872.99    57.4  854.32    76.5  842.72    95.6  830.36
   105.1  824.87   114.7   820.6   134.2   816.9     147815.3276   163.4   814.6
   192.6  814.77     212  815.71   241.2  816.12   309.3  819.43     358  824.17
   396.9  826.34   426.1  829.47   435.8  830.19   455.3  830.18     465  830.72
   474.7  832.21   484.5  834.44   494.2   839.6   523.4  859.72   533.1  864.73
   542.9  869.09   572.1  880.14   591.6  889.09   601.3  893.01     611  896.17
#Mann= 3 , 0 , 0
       0     .08       0     147    .045       0   192.6     .06       0
Bank Sta=147,192.6
XS Rating Curve= 0 ,0
Exp/Cntr=0.3,0.1

Type RM Length L Ch R = 1 ,51145.6 ,63.8,63.5,63.7
XS GIS Cut Line= 6
     1570210.187      328649.904      1570247.08      328539.227
     1570490.135      328289.661     1570516.177      328285.321
     1570693.043      328261.449     1570815.656      328343.915
#Sta/Elev= 30
       0  863.66      68  836.83    77.8   833.9    87.5  832.38   116.7  830.65
   155.4   829.1   213.4  825.78   252.1  821.58   271.5  821.23   290.8  819.96
   319.9  815.52   339.2  814.65   358.6  815.08   397.3  816.58     436   817.2
   491.4  819.65     529  822.73   585.4  826.06   594.8  827.42   613.5   832.1
   622.9  833.67   651.1  833.62   669.9  834.67   679.1  836.33   688.4  838.72
   706.8  844.37   725.3  849.19   771.5  864.69   799.2  875.61   817.7  882.13
#Mann= 3 , 0 , 0
       0     .08       0   319.9    .045       0   358.6     .06       0
Bank Sta=319.9,358.6
XS Rating Curve= 0 ,0
Exp/Cntr=0.3,0.1

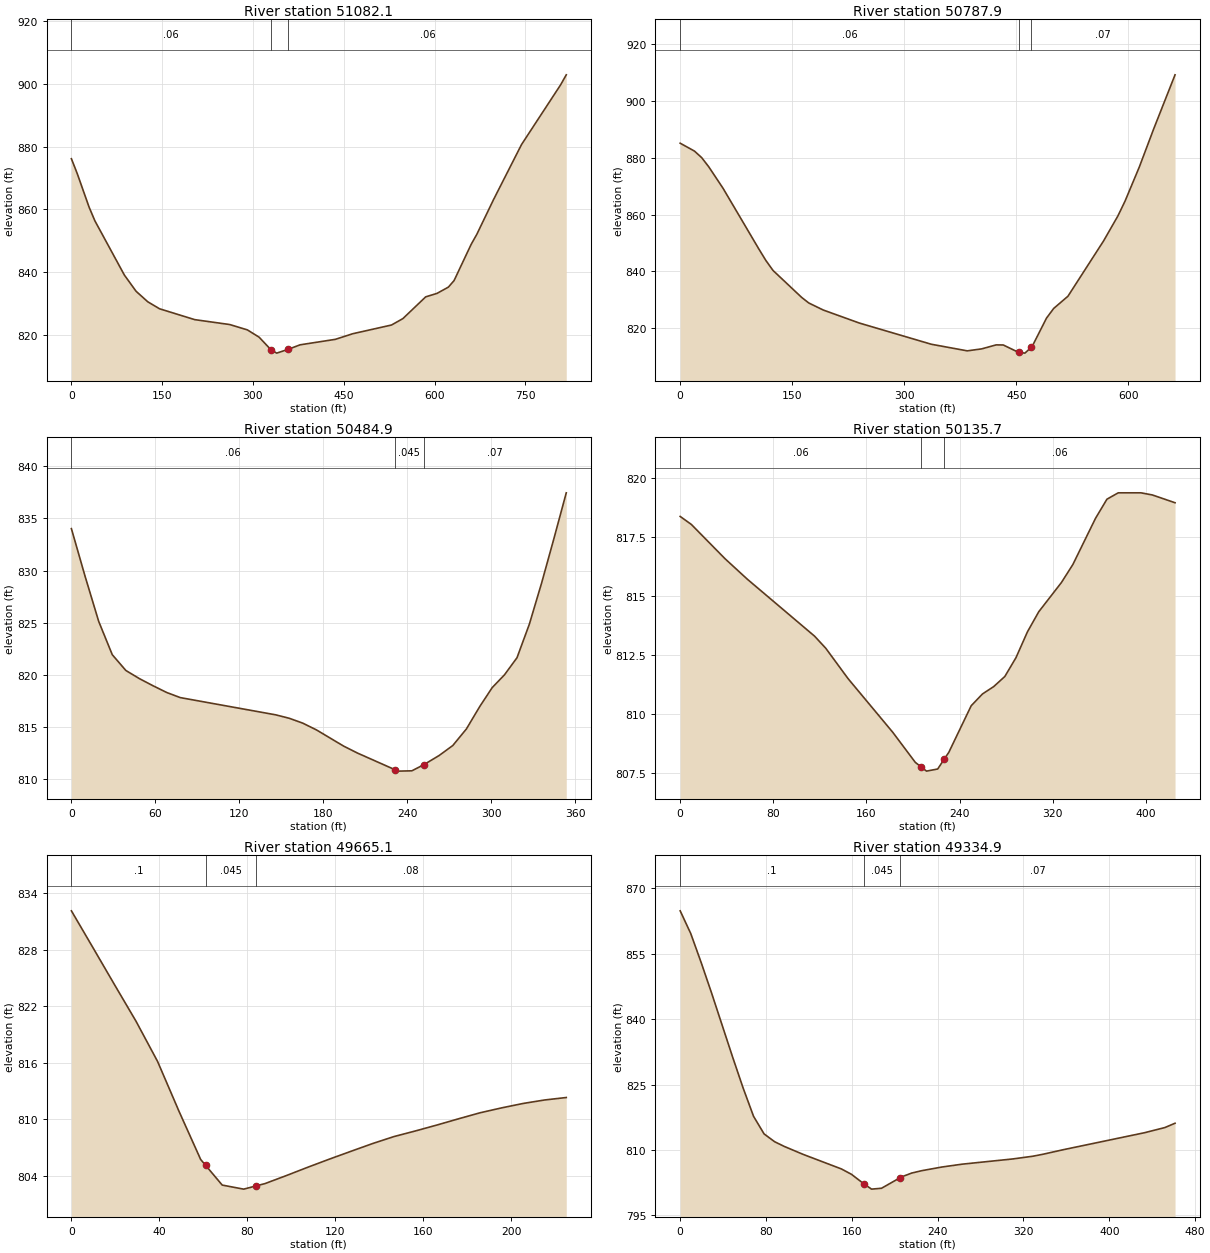
Type RM Length L Ch R = 1 ,51082.1 ,274.4,294.3,306.3
XS GIS Cut Line= 6
     1570250.335      328698.732     1570287.227      328588.055
     1570530.283      328338.489     1570556.325      328334.149
     1570733.191      328310.278     1570855.804      328392.743
#Sta/Elev= 30
       0  876.15     9.7  871.39    29.2  860.72    38.9  856.31    87.5  839.06
   106.9  833.87   126.3  830.51   145.7  828.29   203.8  824.83   261.8  823.26
   290.8  821.56   310.2  819.23   329.6  815.26   339.2  814.15   358.6  815.39
   377.9   816.8     436  818.54     465  820.34     529  823.12   547.8  825.17
   585.4  832.09   604.2  833.21   622.9   835.2   632.3  837.28   660.5  848.82
   669.9  852.04   697.6  863.14   743.8  880.68   808.4  899.73   817.7  902.91
#Mann= 3 , 0 , 0
       0     .06       0   329.6    .045       0   358.6     .06       0
Bank Sta=329.6,358.6
XS Rating Curve= 0 ,0
Exp/Cntr=0.3,0.1

Type RM Length L Ch R = 1 ,50787.9 ,295.9,302.9,309
XS GIS Cut Line= 4
     1570259.341      328777.834     1570329.654      328652.834
     1570670.799      328548.667     1570832.258      328530.438
#Sta/Elev= 30
       0  885.03    19.1  882.27    28.7  879.99    38.2  876.77    57.4   869.2
   105.2  847.95   114.7  843.88   124.3  840.36   162.7  830.88   172.3  828.92
   191.6  826.46   239.8   821.9   336.2  814.45   384.4  812.13   403.7  812.82
     423  814.22   432.6  814.19     453811.6041   461.6  811.33     470813.3513
   471.8  813.94   490.5  823.62   500.1  827.01   519.2   831.3     567  850.76
   586.1   859.5   595.7  864.72   614.8   876.7   633.9  889.97   662.6  909.04
#Mann= 3 , 0 , 0
       0     .06       0     453    .045       0     470     .07       0
Bank Sta=453,470
XS Rating Curve= 0 ,0
Exp/Cntr=0.3,0.1

Type RM Length L Ch R = 1 ,50484.9 ,330,349.2,365.4
XS GIS Cut Line= 3
      1570398.99      328839.791     1570690.873      328845.217
     1570746.212       328818.09
#Sta/Elev= 30
       0  834.01     9.7  829.48    19.5  825.13    29.2  821.94    38.9  820.43
    48.7  819.64    58.4  818.96    68.1  818.32    77.8  817.83     146  816.18
   155.7  815.85   165.4  815.38   175.2  814.73   194.6  813.18   204.4  812.52
     231810.9374   233.6  810.79   243.3  810.82     252811.4211   262.7  812.28
   272.5  813.24   282.2  814.82   291.9     817   300.7  818.79   309.5  820.02
   318.4  821.65   327.2  824.85     336  828.81   344.8  833.07   353.6  837.44
#Mann= 3 , 0 , 0
       0     .06       0     231    .045       0     252     .07       0
Bank Sta=231,252
XS Rating Curve= 0 ,0
Exp/Cntr=0.3,0.1

Type RM Length L Ch R = 1 ,50135.7 ,480.6,470.6,451.5
XS GIS Cut Line= 3
     1570476.029      328977.595     1570682.193      329179.418
     1570817.826      329195.694
#Sta/Elev= 29
       0  818.39     9.6  818.05    38.5   816.6    57.7  815.73   115.4  813.32
     125  812.81   144.2  811.52   182.7  809.24     202  807.97     207807.7786
   211.6   807.6   221.2  807.69     227  808.12   230.8   808.4     250  810.37
   259.7  810.87   269.3  811.18   278.9  811.61   288.5  812.41   298.3   813.5
     308  814.35   327.5  815.59   337.3  816.35   356.8  818.31   366.6  819.12
   376.3  819.39   395.8  819.39   405.6   819.3   425.1  818.97
#Mann= 3 , 0 , 0
       0     .06       0     207    .045       0     227     .06       0
Bank Sta=207,227
XS Rating Curve= 0 ,0
Exp/Cntr=0.3,0.1

Type RM Length L Ch R = 1 ,49665.1 ,327.4,330.2,339
XS GIS Cut Line= 4
     1570357.757      329414.878     1570408.755      329444.175
     1570496.646      329446.345      1570559.58      329399.687
#Sta/Elev= 28
       0  832.14     9.8  828.23    19.6   824.3    29.4  820.41    39.2  816.14
      49  810.82    58.8  805.73      61805.1189    62.4  804.73    68.6  803.01
    77.4  802.62    78.4  802.58      84802.9206    88.1  803.17    97.9  804.03
   107.7  804.92   117.4  805.77   127.2   806.6     137  807.42   146.7  808.16
   156.5  808.76   166.3  809.39   176.1  810.05   185.9  810.69   195.7  811.21
   205.5  811.68   215.3  812.05   225.1  812.31
#Mann= 3 , 0 , 0
       0      .1       0      61    .045       0      84     .08       0
Bank Sta=61,84
XS Rating Curve= 0 ,0
Exp/Cntr=0.3,0.1

Type RM Length L Ch R = 1 ,49334.9 ,128.9,113.7,95.7
XS GIS Cut Line= 5
     1570287.227      329788.142     1570342.566      329719.783
     1570393.564      329733.889     1570504.241      329784.887
     1570702.809      329787.057
#Sta/Elev= 29
       0  864.87     9.8  859.69    19.5  853.06    29.3     846    48.9  831.32
    58.6  824.28    68.4  817.74    78.2  813.71      88  811.92    96.8  810.86
   114.4  809.03   150.2  805.68   159.6  804.45     171802.2996   178.4  801.04
   187.7  801.24     205803.6589   206.5  803.86   215.9  804.73   225.2  805.27
     244  806.11   262.7  806.76     310  807.96   328.9  808.59   338.4  809.05
   357.3  810.09   432.9  813.98   451.8  815.16   461.3  816.15
#Mann= 3 , 0 , 0
       0      .1       0     171    .045       0     205     .07       0
Bank Sta=171,205
XS Rating Curve= 0 ,0
Exp/Cntr=0.3,0.1

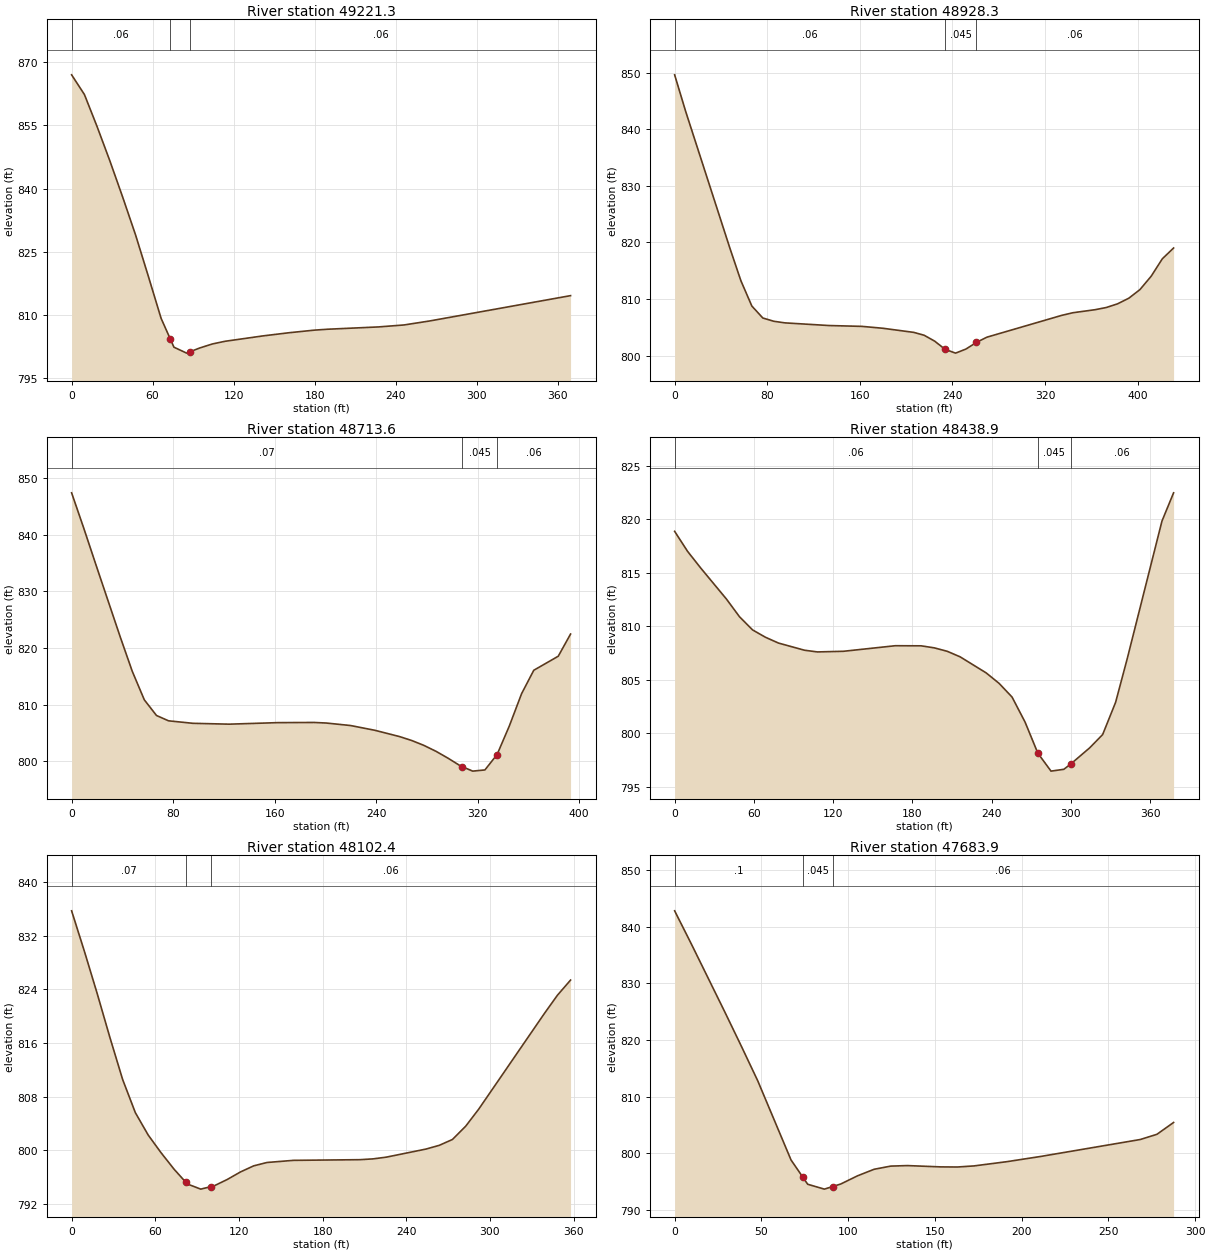
Type RM Length L Ch R = 1 ,49221.3 ,297.4,293,287.4
XS GIS Cut Line= 4
      1570324.12      329873.863     1570385.969      329849.991
     1570494.476      329816.354     1570683.278      329797.908
#Sta/Elev= 23
       0     867     9.5  862.32    18.9  854.69    28.4  846.52    37.9   837.9
    47.4  828.96    56.8  819.21    66.3  809.17      73804.3497    75.8  802.33
    85.2  800.92      88801.2764    94.7  802.12   104.2  803.09   113.6  803.73
     142  805.02     161  805.76   179.9  806.38   189.4  806.59   227.3  807.14
   246.3  807.61   265.3  808.56   369.6  814.57
#Mann= 3 , 0 , 0
       0     .06       0      73    .045       0      88     .06       0
Bank Sta=73,88
XS Rating Curve= 0 ,0
Exp/Cntr=0.3,0.1

Type RM Length L Ch R = 1 ,48928.3 ,190.6,214.7,237.7
XS GIS Cut Line= 5
     1570316.351      330102.476     1570475.813      330130.896
     1570515.294      330110.133     1570609.696      330056.964
     1570725.798      330053.709
#Sta/Elev= 29
       0  849.65     9.5   843.2    47.6  819.08    57.2  813.26    66.7  808.76
    76.2  806.64    85.8  806.06    95.3  805.78   133.4  805.31     162  805.16
   179.8  804.83   206.6   804.1   215.6  803.59   224.6  802.56   233.7   801.1
   242.7  800.43   251.7  801.15   260.8  802.33   269.8  803.25   334.3   807.1
     344  807.57   363.3  808.11     373   808.5   382.7  809.15   392.4  810.14
     402  811.66   411.7  814.02   421.4  817.12   431.1  819.02
#Mann= 3 , 0 , 0
       0     .06       0   233.7    .045       0   260.8     .06       0
Bank Sta=233.7,260.8
XS Rating Curve= 0 ,0
Exp/Cntr=0.3,0.1

Type RM Length L Ch R = 1 ,48713.6 ,277.3,274.7,272.2
XS GIS Cut Line= 3
     1570304.588      330158.151     1570519.432      330238.446
     1570661.576      330319.826
#Sta/Elev= 30
       0  847.37     9.6  841.12    19.1  834.73    38.2  822.04    47.8   815.9
    57.3  810.87    66.9  808.11    76.4  807.17    95.6  806.73   124.2  806.58
   162.5  806.85   191.1  806.88   200.7  806.78   219.8  806.34     239   805.5
   258.3   804.4   267.9  803.71   277.5  802.85   287.2  801.79   296.8  800.56
   306.4  799.22     308799.0688   316.1   798.3   325.7  798.51   335.3  801.22
     345  806.29   354.6  811.95   364.2  816.08   383.5  818.56   393.2  822.47
#Mann= 3 , 0 , 0
       0     .07       0     308    .045       0   335.3     .06       0
Bank Sta=308,335.3
XS Rating Curve= 0 ,0
Exp/Cntr=0.3,0.1

Type RM Length L Ch R = 1 ,48438.9 ,331.3,336.4,341.7
XS GIS Cut Line= 4
     1570209.102      330421.823     1570455.413      330520.564
     1570518.347      330547.691      1570555.24      330571.562
#Sta/Elev= 30
       0  818.86     9.8  816.99    19.7  815.44    39.3  812.52    49.1  810.88
      59  809.65    68.8  808.96    78.6  808.42    98.3  807.75   108.1  807.59
   127.8  807.65   167.1  808.17   186.7  808.16   196.6  807.97   206.4  807.65
   216.2  807.13   235.9  805.63   245.7  804.65   255.5  803.37   265.4  801.02
     275798.1302     285  796.45   294.7  796.62     300797.1229   314.3  798.63
   324.1  799.87   333.9  802.88   342.7  806.96     369  819.82   377.8  822.46
#Mann= 3 , 0 , 0
       0     .06       0     275    .045       0     300     .06       0
Bank Sta=275,300
XS Rating Curve= 0 ,0
Exp/Cntr=0.3,0.1

Type RM Length L Ch R = 1 ,48102.4 ,432.5,418.5,402.2
XS GIS Cut Line= 4
     1570184.146      330754.939     1570248.165      330754.939
     1570404.415      330863.446     1570485.795      330927.465
#Sta/Elev= 30
       0  835.75     9.2  829.68    18.3  823.42    27.4  816.87    36.6  810.54
    45.7  805.59    54.9  802.25      64  799.64    73.5  797.13      82795.1616
      83  794.93    92.6  794.16     100 794.535   102.1  794.64   111.6   795.6
   121.1  796.73   130.6  797.64   140.1  798.14   159.1  798.46   206.7  798.56
   216.2  798.68   225.7  798.94   254.2  800.15   263.7  800.71   273.1  801.58
   282.5  803.54   291.9   806.1     339   820.4   348.4  823.14   357.8   825.4
#Mann= 3 , 0 , 0
       0     .07       0      82    .045       0     100     .06       0
Bank Sta=82,100
XS Rating Curve= 0 ,0
Exp/Cntr=0.3,0.1

Type RM Length L Ch R = 1 ,47683.9 ,206.8,221.3,233.1
XS GIS Cut Line= 2
      1570101.68       331168.35     1570389.224      331165.095
#Sta/Elev= 23
       0  842.82     9.6  836.98    28.8  825.02    38.3  818.99    47.9  812.78
    67.1  798.78      74795.6974    76.7  794.49    86.3  793.63      91794.0787
    95.8  794.54   105.4  795.98     115  797.14   124.6   797.7   134.2  797.79
   153.4  797.56     163  797.54   172.5  797.73   191.7  798.49   210.9   799.4
   268.4   802.4     278  803.32   287.6  805.41
#Mann= 3 , 0 , 0
       0      .1       0      74    .045       0      91     .06       0
Bank Sta=74,91
XS Rating Curve= 0 ,0
Exp/Cntr=0.3,0.1

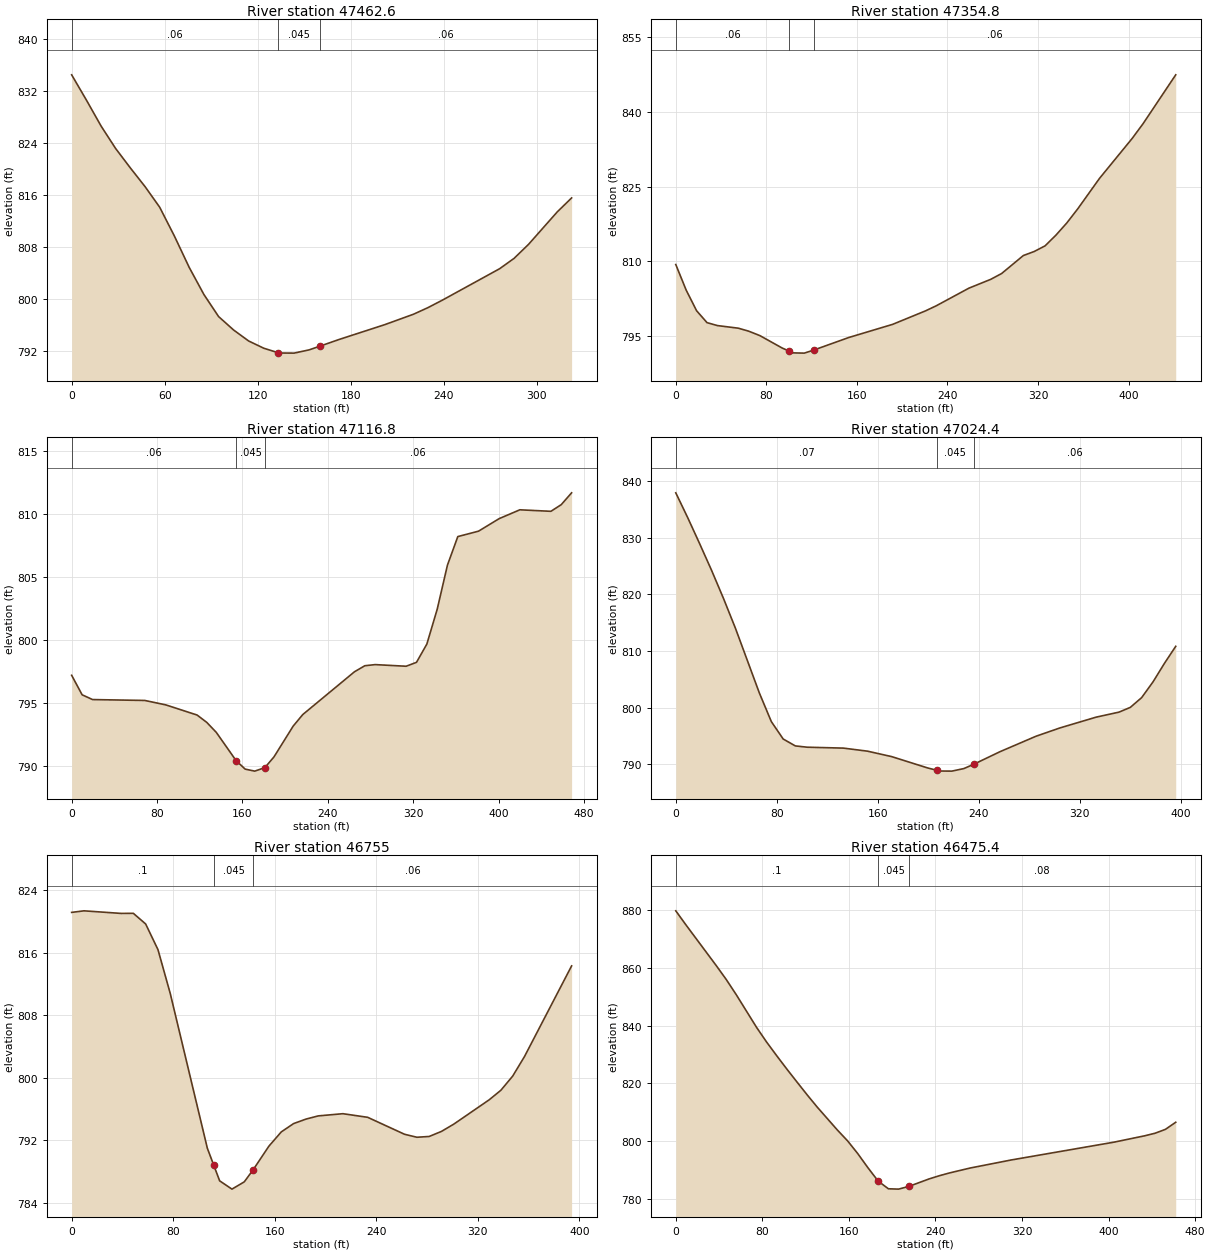
Type RM Length L Ch R = 1 ,47462.6 ,109.2,107.8,107.9
XS GIS Cut Line= 4
     1570110.361      331302.899     1570183.061      331363.663
     1570279.632      331410.321     1570400.075      331416.831
#Sta/Elev= 29
       0  834.56     9.5  830.68      19  826.67    28.4  823.21    37.9  820.22
    47.4  817.34    56.8  814.18    66.3  809.74    75.8  804.94    85.3  800.76
    94.8  797.35   104.5  795.28   114.2  793.59     124  792.47     133791.7996
   133.8  791.74   143.5  791.72   153.2  792.22     160792.7751   172.8  793.84
     202   796.1   220.6  797.71   229.8  798.71   239.1  799.86   276.2  804.72
   285.5  806.31   294.8  808.46   313.3  813.45   322.6  815.61
#Mann= 3 , 0 , 0
       0     .06       0     133    .045       0     160     .06       0
Bank Sta=133,160
XS Rating Curve= 0 ,0
Exp/Cntr=0.3,0.1

Type RM Length L Ch R = 1 ,47354.8 ,217.9,238,257.8
XS GIS Cut Line= 4
     1570114.701      331419.001     1570160.274      331464.574
      1570253.59      331518.828     1570510.954      331597.763
#Sta/Elev= 30
       0  809.38     9.2  804.24    18.4  800.11    27.6  797.73    36.8  797.14
    55.2  796.62    64.4  796.02    74.3  795.13    93.9  792.65     100  792.04
   103.7  791.67   113.5  791.62     122792.2441   152.8  794.75   191.6  797.39
   220.5  800.08   230.1  801.11   258.9  804.64   278.2  806.41   287.8  807.57
     307  811.18   316.6  811.99   326.2  813.12   335.8  815.27   345.4  817.71
   355.1  820.55   374.3  826.65   403.1  834.64   412.8  837.62   441.6   847.4
#Mann= 3 , 0 , 0
       0     .06       0     100    .045       0     122     .06       0
Bank Sta=100,122
XS Rating Curve= 0 ,0
Exp/Cntr=0.3,0.1

Type RM Length L Ch R = 1 ,47116.8 ,99.1,92.4,84.2
XS GIS Cut Line= 4
     1570048.512      331534.019     1570098.425      331640.356
     1570114.701      331738.012     1570251.623      331949.326
#Sta/Elev= 30
       0  797.18     9.8  795.63    19.6  795.25    68.5  795.18    88.1  794.83
   117.5  794.02   126.5  793.44   135.5  792.64     154   790.4   162.5  789.72
   171.5  789.56     181  789.84   189.5  790.69   207.5  793.14   216.5  794.06
   264.9  797.46   274.6  797.94   284.3  798.03   313.3   797.9     323  798.21
   332.7  799.66   342.4  802.43     352  805.94   361.7  808.21   381.1  808.64
   400.5  809.64   419.8  810.34   448.9  810.22   458.6  810.75   468.3  811.69
#Mann= 3 , 0 , 0
       0     .06       0     154    .045       0     181     .06       0
Bank Sta=154,181
XS Rating Curve= 0 ,0
Exp/Cntr=0.3,0.1

Type RM Length L Ch R = 1 ,47024.4 ,267.8,269.4,270.7
XS GIS Cut Line= 4
     1569935.867       331545.68     1569960.824       331627.06
     1570095.373      331835.393     1570097.543      331898.327
#Sta/Elev= 30
       0  837.97     9.5  833.56    18.9  828.98    28.4  824.24    37.8  819.29
    47.3     814    66.2  802.58    75.7  797.51    85.1  794.43    94.7  793.21
   104.2  792.98   132.8  792.82   151.9  792.28     171  791.32   199.6  789.31
     207788.8894   209.1  788.77   218.7  788.75   228.2   789.2     236789.9554
   256.8  792.18   285.4  794.92   304.5   796.4   333.1   798.3   351.1  799.18
   360.1  800.02   369.1  801.75   378.1  804.53   387.1  807.79   396.1  810.82
#Mann= 3 , 0 , 0
       0     .07       0     207    .045       0     236     .06       0
Bank Sta=207,236
XS Rating Curve= 0 ,0
Exp/Cntr=0.3,0.1

Type RM Length L Ch R = 1 ,46755   ,287.1,279.6,272.1
XS GIS Cut Line= 3
     1569795.893      331615.124      1569938.92      331880.156
     1569971.472      331966.962
#Sta/Elev= 30
       0  821.14     9.7  821.34    38.9  821.01    48.6  821.02    58.3  819.66
      68  816.38    77.7  810.76   106.9     791     112788.8058   116.6  786.83
   126.3  785.77     136   786.7     143788.2443   155.4  791.26   165.2  793.09
   174.9  794.15   184.6  794.72   194.3  795.13   213.7  795.41   233.2  794.95
   262.3  792.78     272   792.4   281.7   792.5   291.4  793.15   301.2  794.09
     329  797.19   338.2  798.41   347.5  800.22   356.8  802.72   393.9   814.3
#Mann= 3 , 0 , 0
       0      .1       0     112    .045       0     143     .06       0
Bank Sta=112,143
XS Rating Curve= 0 ,0
Exp/Cntr=0.3,0.1

Type RM Length L Ch R = 1 ,46475.4 ,202.6,214.5,225.3
XS GIS Cut Line= 4
     1569570.199      331729.056     1569615.808      331881.115
     1569733.842      331989.748      1569857.54      332061.363
#Sta/Elev= 30
       0  879.72     9.3   874.9    37.4  860.76    46.7  855.92      56  850.62
    74.7  839.35      84  834.26    93.4   829.5   102.7  824.91   112.1  820.42
   121.4  816.02   130.7  811.78   149.4  803.81   158.8  800.07   168.2  795.66
   177.6  790.77   187.1  786.13   196.5  783.48   205.9  783.36   215.4   784.3
   234.2   786.9   243.7  788.01   253.1  788.97     272  790.66   309.7  793.43
   404.9  799.61   433.5  801.83     443  802.71   452.6  804.06   462.1  806.51
#Mann= 3 , 0 , 0
       0      .1       0   187.1    .045       0   215.4     .08       0
Bank Sta=187.1,215.4
XS Rating Curve= 0 ,0
Exp/Cntr=0.3,0.1

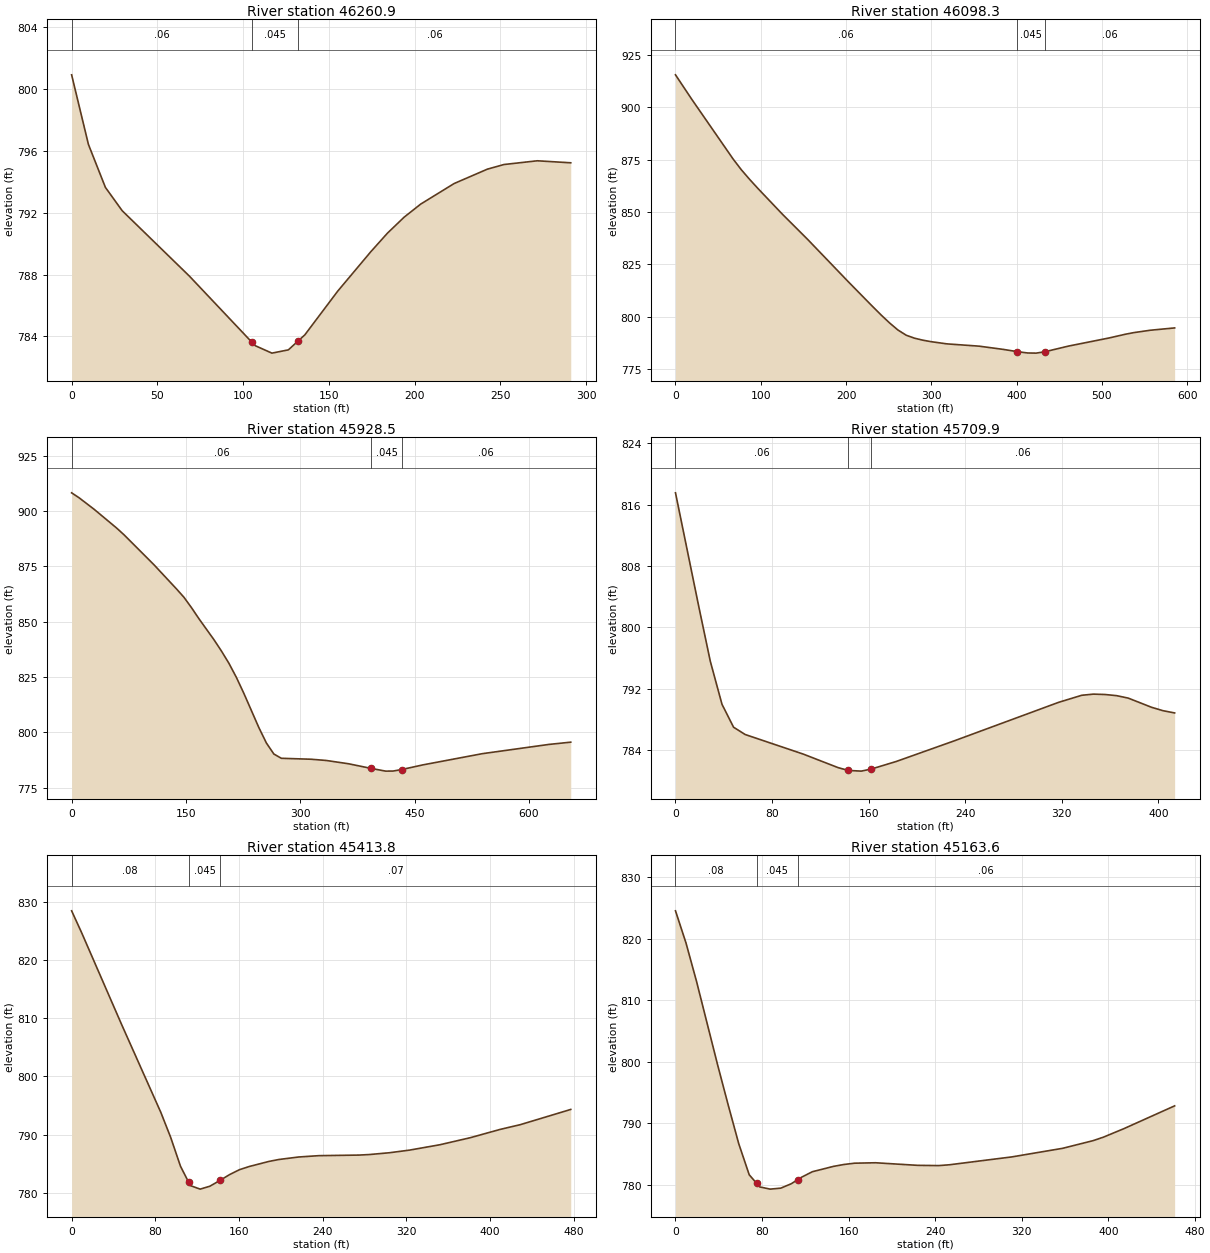
Type RM Length L Ch R = 1 ,46260.9 ,173.1,162.7,153.6
XS GIS Cut Line= 4
     1569502.722      331984.323     1569520.083      332040.746
     1569562.401      332148.168     1569591.698      332261.015
#Sta/Elev= 21
       0  800.92     9.8  796.42    19.7  793.64    29.5  792.13    68.7   787.9
     105783.6406   107.1   783.4   116.8  782.92   126.4  783.13     132783.6958
     136   784.1   155.2  786.93   174.5  789.48   184.2  790.68   193.9  791.71
   203.6  792.56   223.1  793.89   242.5  794.82   252.2  795.12   271.6  795.36
   291.1  795.23
#Mann= 3 , 0 , 0
       0     .06       0     105    .045       0     132     .06       0
Bank Sta=105,132
XS Rating Curve= 0 ,0
Exp/Cntr=0.3,0.1

Type RM Length L Ch R = 1 ,46098.3 ,175.8,169.8,162.9
XS GIS Cut Line= 4
     1569332.865      331838.525     1569331.281      332109.106
     1569495.127      332281.632     1569571.082      332269.696
#Sta/Elev= 30
       0  915.48    19.3  903.68    67.6  875.29    77.3  870.13      87  865.56
    96.6  861.28   125.6  848.87   154.6   837.1   202.9  816.64   231.9  804.61
   241.6   800.7   251.3  796.99   260.9  793.69   270.6   791.2   280.1  789.82
   289.6  788.88   299.1  788.17   318.2  787.08   356.2  785.98   384.8  784.42
     400 783.426     413  782.73   422.9  782.66     433783.2932   460.9  786.02
   508.5  789.89   527.7  791.68   537.4  792.44   556.6  793.57   585.4  794.69
#Mann= 3 , 0 , 0
       0     .06       0     400    .045       0     433     .06       0
Bank Sta=400,433
XS Rating Curve= 0 ,0
Exp/Cntr=0.3,0.1

Type RM Length L Ch R = 1 ,45928.5 ,219.9,218.6,216.9
XS GIS Cut Line= 4
     1568955.261      332304.671     1569240.135      332297.908
     1569451.724      332419.435     1569568.911      332465.008
#Sta/Elev= 30
       0  908.24     9.8     906    29.5  900.81      59  892.34    68.8  889.26
   108.1  875.71   137.6  864.81   147.4  861.02   157.2  856.37     167  851.36
   186.7  841.88   196.5  836.77   206.4  831.18   216.2   824.8     226  817.58
   245.6  802.17   255.5   795.2   265.3  790.22   275.1   788.3   314.2  787.87
   333.8  787.32     363  785.84     393 783.725   411.8   782.5   421.6  782.53
     433783.2169   460.6  785.31   538.6  790.38   625.7  794.55   654.7  795.59
#Mann= 3 , 0 , 0
       0     .06       0     393    .045       0     433     .06       0
Bank Sta=393,433
XS Rating Curve= 0 ,0
Exp/Cntr=0.3,0.1

Type RM Length L Ch R = 1 ,45709.9 ,296.8,296.1,295.2
XS GIS Cut Line= 2
     1569092.566      332468.264     1569462.575      332652.725
#Sta/Elev= 22
       0  817.54    19.2  802.79    28.8  795.62    38.5     790    48.1  787.01
    57.7  786.06   105.8  783.51   134.6  781.75     143781.3837   153.8  781.29
     162781.5545   182.7  782.54   230.8  785.23   317.3  790.25   336.5  791.17
   346.1  791.32   355.8  791.27   365.4  791.12     375   790.8   394.2  789.61
   403.8  789.16   413.4  788.87
#Mann= 3 , 0 , 0
       0     .06       0     143    .045       0     162     .06       0
Bank Sta=143,162
XS Rating Curve= 0 ,0
Exp/Cntr=0.3,0.1

Type RM Length L Ch R = 1 ,45413.8 ,247.3,250.2,253
XS GIS Cut Line= 4
     1568930.891      332739.531      1568997.08      332746.041
     1569125.321       332804.36     1569393.333      332772.893
#Sta/Elev= 27
       0  828.41     9.5  824.69    47.5  809.03    85.3  793.83    94.7  789.55
   104.1  784.59     112781.8082   113.5  781.28   122.9  780.67   132.2  781.17
     142782.1834     151  783.16   160.4     784   169.8  784.55   188.6  785.42
     198  785.75     217  786.18   236.3  786.41   274.8  786.51   284.5   786.6
   303.8  786.91     323  787.36     352  788.28   380.9  789.48   409.8  790.92
     429  791.73   477.2  794.34
#Mann= 3 , 0 , 0
       0     .08       0     112    .045       0     142     .07       0
Bank Sta=112,142
XS Rating Curve= 0 ,0
Exp/Cntr=0.3,0.1

Type RM Length L Ch R = 1 ,45163.6 ,168.1,167.3,166.8
XS GIS Cut Line= 3
      1568836.49      332932.673      1569084.97      333085.668
     1569254.241      333084.583
#Sta/Elev= 28
       0  824.55     9.7  819.32    19.4  813.09    38.9  799.49    48.6  793.01
    58.4  786.67    68.1   781.6      75780.1915    77.8  779.62    87.5  779.26
    97.3  779.42     107  780.14     113 780.808   116.7  781.22   126.4  782.09
   145.9  782.96   155.6  783.27   165.4  783.48   184.8  783.55   223.7  783.13
   243.2  783.09   252.9  783.22   310.6   784.5   357.6   785.9   385.8  787.15
   395.2  787.71   414.1  789.09   461.1  792.81
#Mann= 3 , 0 , 0
       0     .08       0      75    .045       0     113     .06       0
Bank Sta=75,113
XS Rating Curve= 0 ,0
Exp/Cntr=0.3,0.1

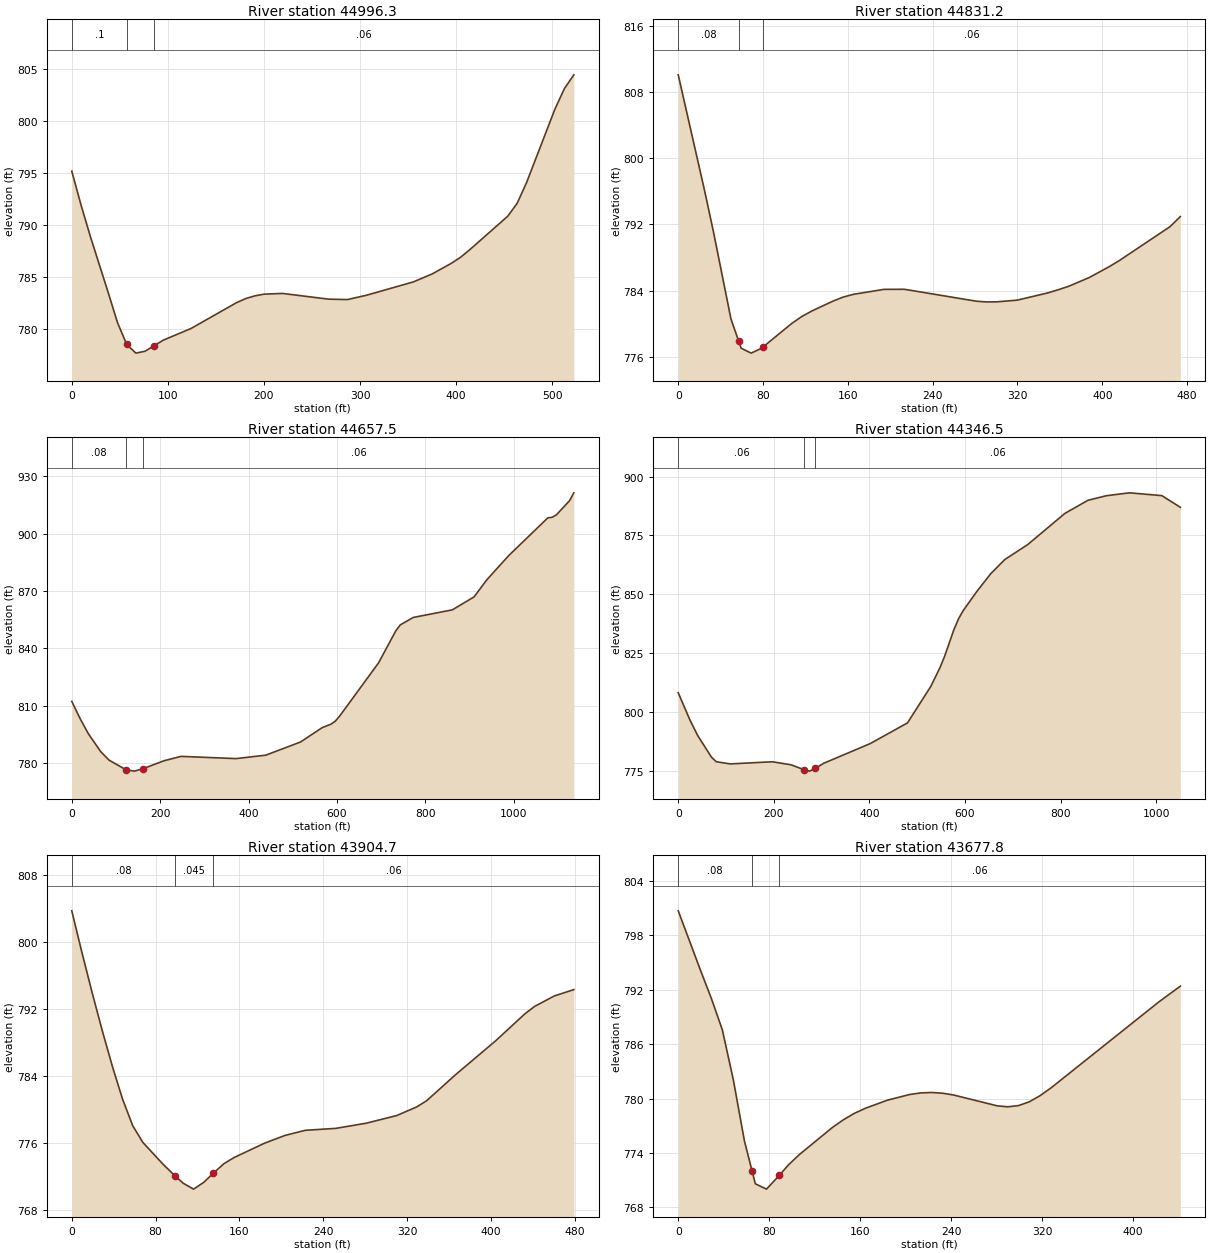
Type RM Length L Ch R = 1 ,44996.3 ,168.8,165.2,159.6
XS GIS Cut Line= 3
     1568782.171      333097.795     1569006.129      333224.531
     1569269.017      333258.253
#Sta/Elev= 30
       0  795.22     9.5  792.01    19.1  789.01    38.1  783.49    47.6  780.65
    57.2  778.55    66.7  777.72    76.2   777.9    85.8  778.44    95.3  778.97
   123.9  780.08   171.6  782.58   181.1  782.97   190.6  783.23   200.2  783.39
   219.2  783.46   267.2  782.91   286.8  782.87   306.4  783.28   355.5  784.57
   375.1  785.34   394.8  786.35   404.6  786.94   414.4  787.69   453.7  790.89
   463.5  792.14   473.3  794.14   502.7  801.18   512.6  803.16   522.4  804.48
#Mann= 3 , 0 , 0
       0      .1       0    57.2    .045       0    85.8     .06       0
Bank Sta=57.2,85.8
XS Rating Curve= 0 ,0
Exp/Cntr=0.3,0.1

Type RM Length L Ch R = 1 ,44831.2 ,188.3,173.7,160.1
XS GIS Cut Line= 5
     1568732.323      333256.024     1568774.641      333282.066
     1568857.106      333307.022     1569118.608      333303.767
     1569191.307      333326.554
#Sta/Elev= 29
       0  810.09    24.8  796.12    33.1  791.19    49.7  780.59      57777.8905
    59.3  777.04    68.8  776.44    78.4  777.02      80777.1833   107.1  780.03
   116.7  780.88   126.3  781.55   145.5   782.7   155.2   783.2   164.9  783.54
     194  784.15   213.3  784.16   281.1  782.72   290.8  782.63   300.5  782.64
   319.9  782.85   348.9  783.73   358.6  784.11   368.3  784.52   387.7  785.58
   406.9  786.92   416.4  787.66     464  791.74   473.6  792.95
#Mann= 3 , 0 , 0
       0     .08       0      57    .045       0      80     .06       0
Bank Sta=57,80
XS Rating Curve= 0 ,0
Exp/Cntr=0.3,0.1

Type RM Length L Ch R = 1 ,44657.5 ,278.2,311,341.4
XS GIS Cut Line= 4
     1568659.406      333453.073     1568741.003      333473.906
     1569079.545      333368.003     1569770.365      333460.921
#Sta/Elev= 30
       0  812.26    18.7  803.32    37.4   795.4    65.5  785.98    84.2  781.56
   122.6  776.49   141.7  775.78   160.9  777.02   208.8  781.22   247.2  783.49
   371.8  782.33   438.9  784.12   517.5     791   566.6  798.51   586.2   800.3
     596  801.86   605.8  804.46   694.2  832.41   733.5  849.27   743.3  852.25
   772.7  856.14   861.1  860.11   910.2  866.88   939.6  875.96   988.7  888.49
  1077.1  908.21  1086.9   908.5  1096.7  909.82  1126.2  917.16    1136   921.3
#Mann= 3 , 0 , 0
       0     .08       0   122.6    .045       0   160.9     .06       0
Bank Sta=122.6,160.9
XS Rating Curve= 0 ,0
Exp/Cntr=0.3,0.1

Type RM Length L Ch R = 1 ,44346.5 ,444.3,441.8,438.7
XS GIS Cut Line= 5
     1568640.309      333496.475     1568669.823      333524.253
     1568812.184      333769.045     1568906.614      333939.628
      1569285.99      334312.484
#Sta/Elev= 30
       0  808.15    24.3  796.63    40.5  790.01    69.8  780.66    79.6   778.8
   108.9  777.87   196.8  778.78   235.8  777.51     264775.3568   274.9   774.8
     287775.9531   304.2  778.12   401.7  786.51   479.7   795.3   528.4  810.79
   547.7   818.8   557.4  823.62   576.7  834.88   586.4  839.52     596  842.98
   625.1  851.26   654.1  858.79   683.1  864.73   731.4  871.15   808.8  884.35
   857.2  889.96   895.9  891.91   944.2  893.14  1011.9  891.95  1050.6     887
#Mann= 3 , 0 , 0
       0     .06       0     264    .045       0     287     .06       0
Bank Sta=264,287
XS Rating Curve= 0 ,0
Exp/Cntr=0.3,0.1

Type RM Length L Ch R = 1 ,43904.7 ,231.2,226.8,222.5
XS GIS Cut Line= 3
     1568315.859      333790.688     1568497.065       334054.36
     1568528.532       334210.61
#Sta/Elev= 30
       0   803.7     9.7  798.73    19.4  793.96    29.1  789.41    38.8  785.13
    48.5  781.22    58.2  778.06    67.9  776.06    87.3  773.44      99772.0192
   106.6  771.18   116.3  770.49     126   771.3     135772.3763   145.4  773.54
   155.1  774.27   184.2  775.98   203.6   776.9     223  777.51   252.1  777.74
   281.2  778.36   310.2  779.27   329.3   780.3   338.7  781.03   366.8  784.19
   404.3  788.15   432.4  791.39   441.8  792.29   460.6  793.54   479.3   794.3
#Mann= 3 , 0 , 0
       0     .08       0      99    .045       0     135     .06       0
Bank Sta=99,135
XS Rating Curve= 0 ,0
Exp/Cntr=0.3,0.1

Type RM Length L Ch R = 1 ,43677.8 ,338.6,348,356.7
XS GIS Cut Line= 3
     1568136.837      333947.864     1568324.337      334116.267
     1568475.378       334230.85
#Sta/Elev= 30
       0  800.71    19.4  794.21    29.1  791.06    38.8  787.58    48.5  782.05
    58.2  775.34      65771.9813    67.8   770.6    77.6  770.01      89771.5398
    96.9  772.68   106.6  773.83   135.7  776.82   145.4  777.67   155.1  778.38
   164.8  778.94   184.2  779.83   203.6  780.45   213.2  780.62   222.9  780.67
   232.6  780.59   242.3  780.39   280.5   779.2   289.9  779.09   299.4  779.23
   308.9  779.65   318.4  780.33   327.9  781.18   422.6  790.65   441.6   792.4
#Mann= 3 , 0 , 0
       0     .08       0      65    .045       0      89     .06       0
Bank Sta=65,89
XS Rating Curve= 0 ,0
Exp/Cntr=0.3,0.1