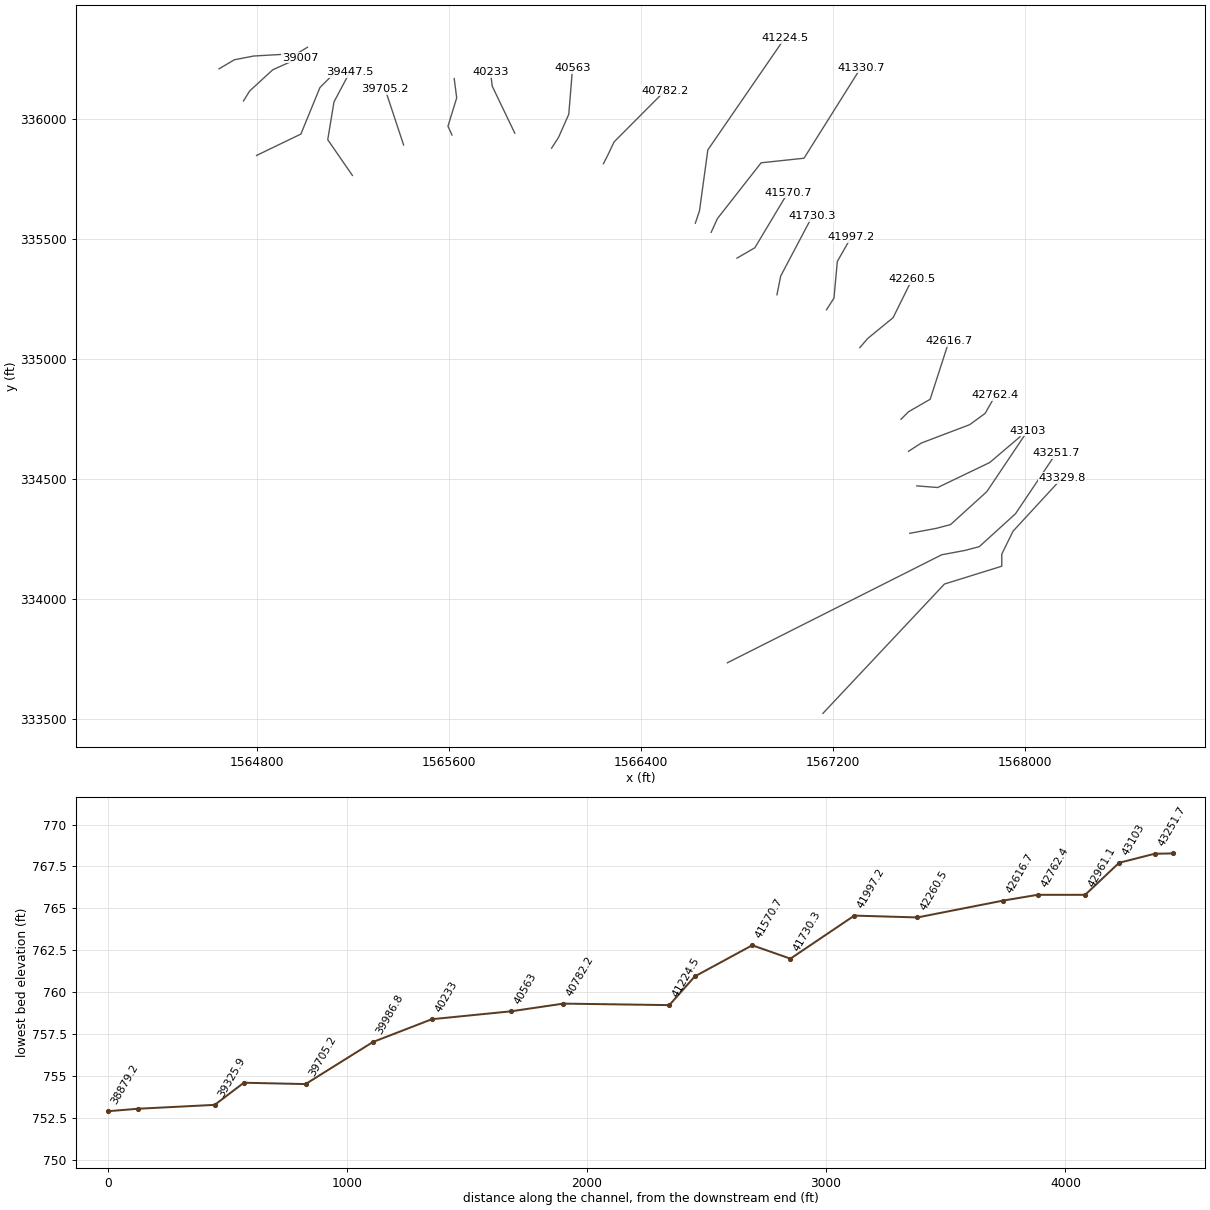
HEC-RAS study SNCHOCRK.prj: SNCHOCRK

--- SNCHOCRK.g01 (geometry) --- (continued)

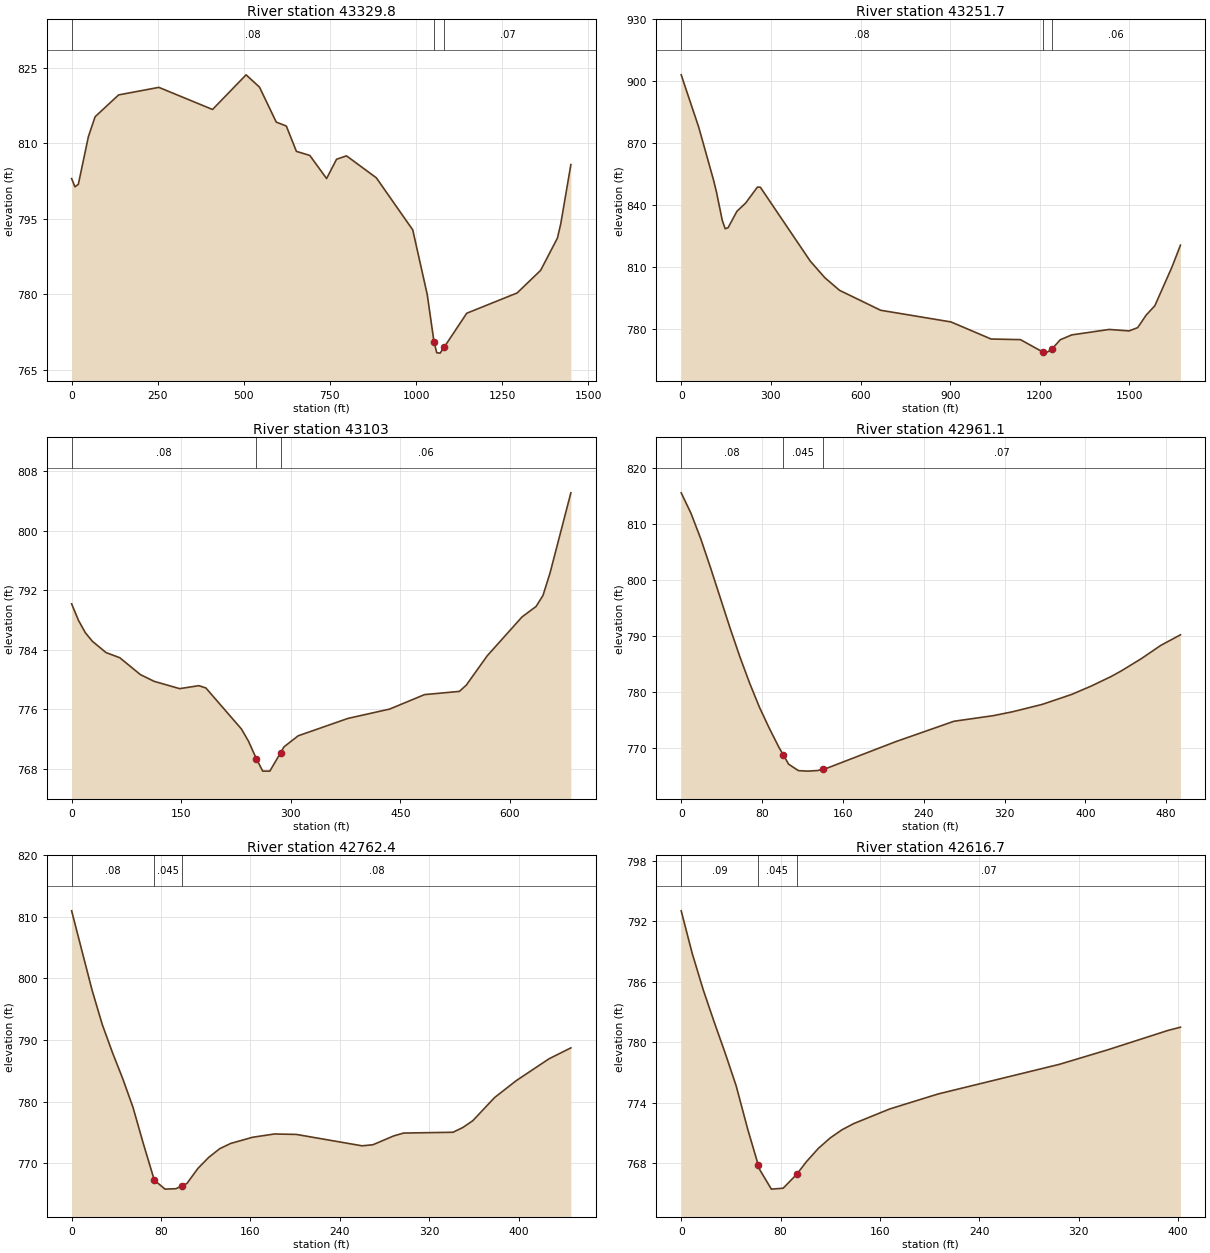
Type RM Length L Ch R = 1 ,43329.8 ,87.3,78.2,69.5
XS GIS Cut Line= 6
     1567158.386      333523.421     1567665.278      334062.842
     1567904.198        334137.1     1567904.198      334187.448
     1567951.073      334282.934     1568155.934      334505.156
#Sta/Elev= 30
       0  802.94     9.7  801.31    19.5  801.81    48.7  811.28    68.2  815.23
   136.4  819.56   253.2  821.06   409.1  816.67   506.5  823.55   545.4  821.11
   594.1  814.16   623.3  813.38   652.6  808.35   691.5  807.54   740.2  802.95
   769.1  806.78     798  807.46   884.6   803.1   990.4  792.75  1032.4  779.92
    1052770.5553  1060.1  768.35  1069.8  768.28    1082 769.504  1147.1   776.2
  1293.4  780.23  1361.6  784.72  1410.4  791.13  1420.1  793.99  1449.4  805.72
#Mann= 3 , 0 , 0
       0     .08       0    1052    .045       0    1082     .07       0
Bank Sta=1052,1082
XS Rating Curve= 0 ,0
Exp/Cntr=0.3,0.1

Type RM Length L Ch R = 1 ,43251.7 ,148.7,148.7,148.7
XS GIS Cut Line= 6
     1566759.949      333734.359     1567653.691      334184.748
      1567751.42      334203.073     1567810.448      334218.698
      1567961.49       334355.85     1568131.628      334609.323
#Sta/Elev= 30
       0  903.05    58.9  877.55   107.9  852.24   117.7  846.47   137.4  832.59
   147.2   828.5     157  829.03   186.4  836.95   215.9  840.98   255.1   848.7
   264.9   848.6   431.7  812.86   480.8  804.77   529.8  798.68   667.2  789.03
   902.7  783.37    1037  775.09  1135.1   774.8    1210768.8143  1219.6  768.26
    1240 770.123  1268.2  774.72    1307  777.09  1432.1  779.73  1498.9  779.02
  1527.5  780.62  1556.1  786.72  1584.8  791.19    1642  809.89  1670.6  820.54
#Mann= 3 , 0 , 0
       0     .08       0    1210    .045       0    1240     .06       0
Bank Sta=1210,1240
XS Rating Curve= 0 ,0
Exp/Cntr=0.3,0.1

Type RM Length L Ch R = 1 ,43103   ,148.4,141.9,135.2
XS GIS Cut Line= 5
     1567520.517      334274.253     1567631.628      334295.087
     1567690.656      334310.712     1567841.698      334447.864
     1568011.837      334701.337
#Sta/Elev= 30
       0  790.17     9.4  787.95    18.8  786.29    28.3  785.16    47.1  783.63
    65.9  782.94    94.2  780.67     113  779.77   147.9  778.79   174.1  779.19
   183.8  778.88   232.4  773.38   242.1  771.74     253769.3615   261.6  767.72
   271.3  767.72     286770.1805   290.7  770.98   310.1  772.46   378.1  774.79
   435.4  776.05   483.1  777.99   530.8  778.42   540.3  779.27   568.9   783.2
   616.6  788.42   635.7  789.81   645.2  791.29   654.8  794.28   683.4  805.07
#Mann= 3 , 0 , 0
       0     .08       0     253    .045       0     286     .06       0
Bank Sta=253,286
XS Rating Curve= 0 ,0
Exp/Cntr=0.3,0.1

Type RM Length L Ch R = 1 ,42961.1 ,199.6,198.7,196.7
XS GIS Cut Line= 4
     1567550.031       334472.17     1567636.837      334465.225
     1567853.851      334569.392     1567980.587      334677.031
#Sta/Elev= 30
       0  815.58     9.7  811.91    19.4  807.34      29   802.2    48.4  791.37
    58.1  786.24    67.7  781.56    77.4  777.25    87.1  773.51    96.7  770.07
     101768.7218   106.3  767.06   110.2  766.59     116   765.9   125.2  765.81
   135.2  765.92     140766.1476   144.9  766.38   212.3  771.08     270  774.73
   308.5  775.72   327.8  776.42   357.2  777.74   386.5  779.53     406  781.04
   425.6  782.74   435.4  783.72     455  785.88   474.5  788.28   494.1  790.19
#Mann= 3 , 0 , 0
       0     .08       0     101    .045       0     140     .07       0
Bank Sta=101,140
XS Rating Curve= 0 ,0
Exp/Cntr=0.3,0.1

Type RM Length L Ch R = 1 ,42762.4 ,142.9,145.7,149.3
XS GIS Cut Line= 5
     1567515.309      334616.267     1567569.128      334650.989
     1567770.517      334727.378     1567834.753      334774.253
     1567878.156      334850.642
#Sta/Elev= 30
       0  810.98    18.3  798.11    27.4  792.54    36.6  787.95    45.8  783.71
    54.9   779.1      64  773.31      74767.2693    83.6  765.81    93.4  765.88
      99766.3657   103.2  766.73     113  769.17   122.8  770.98   132.6  772.38
   142.4  773.23     162  774.23   181.5  774.76   201.1  774.69   259.9  772.84
   269.6  773.01   288.3  774.45   297.1  774.91   341.3  775.04   350.1  775.81
     359  776.91   378.5  780.67     398  783.43   427.3  786.97   446.8  788.74
#Mann= 3 , 0 , 0
       0     .08       0      74    .045       0      99     .08       0
Bank Sta=74,99
XS Rating Curve= 0 ,0
Exp/Cntr=0.3,0.1

Type RM Length L Ch R = 1 ,42616.7 ,352.2,356.3,359.8
XS GIS Cut Line= 4
     1567484.059      334749.948     1567515.309      334781.198
     1567605.587      334833.281     1567683.712        335074.6
#Sta/Elev= 23
       0  793.03     8.8  788.84    17.7  785.22    26.5  782.04    35.4  778.94
    44.2  775.72    53.7  771.34      62767.8787    63.1  767.42    72.6  765.46
    82.1  765.55      93766.9235     101   768.2   110.5   769.5     120  770.53
   129.5  771.34   138.9  771.95   167.9   773.4     207  774.89   304.5  777.82
   343.5  779.26   392.3  781.19   402.1   781.5
#Mann= 3 , 0 , 0
       0     .09       0      62    .045       0      93     .07       0
Bank Sta=62,93
XS Rating Curve= 0 ,0
Exp/Cntr=0.3,0.1

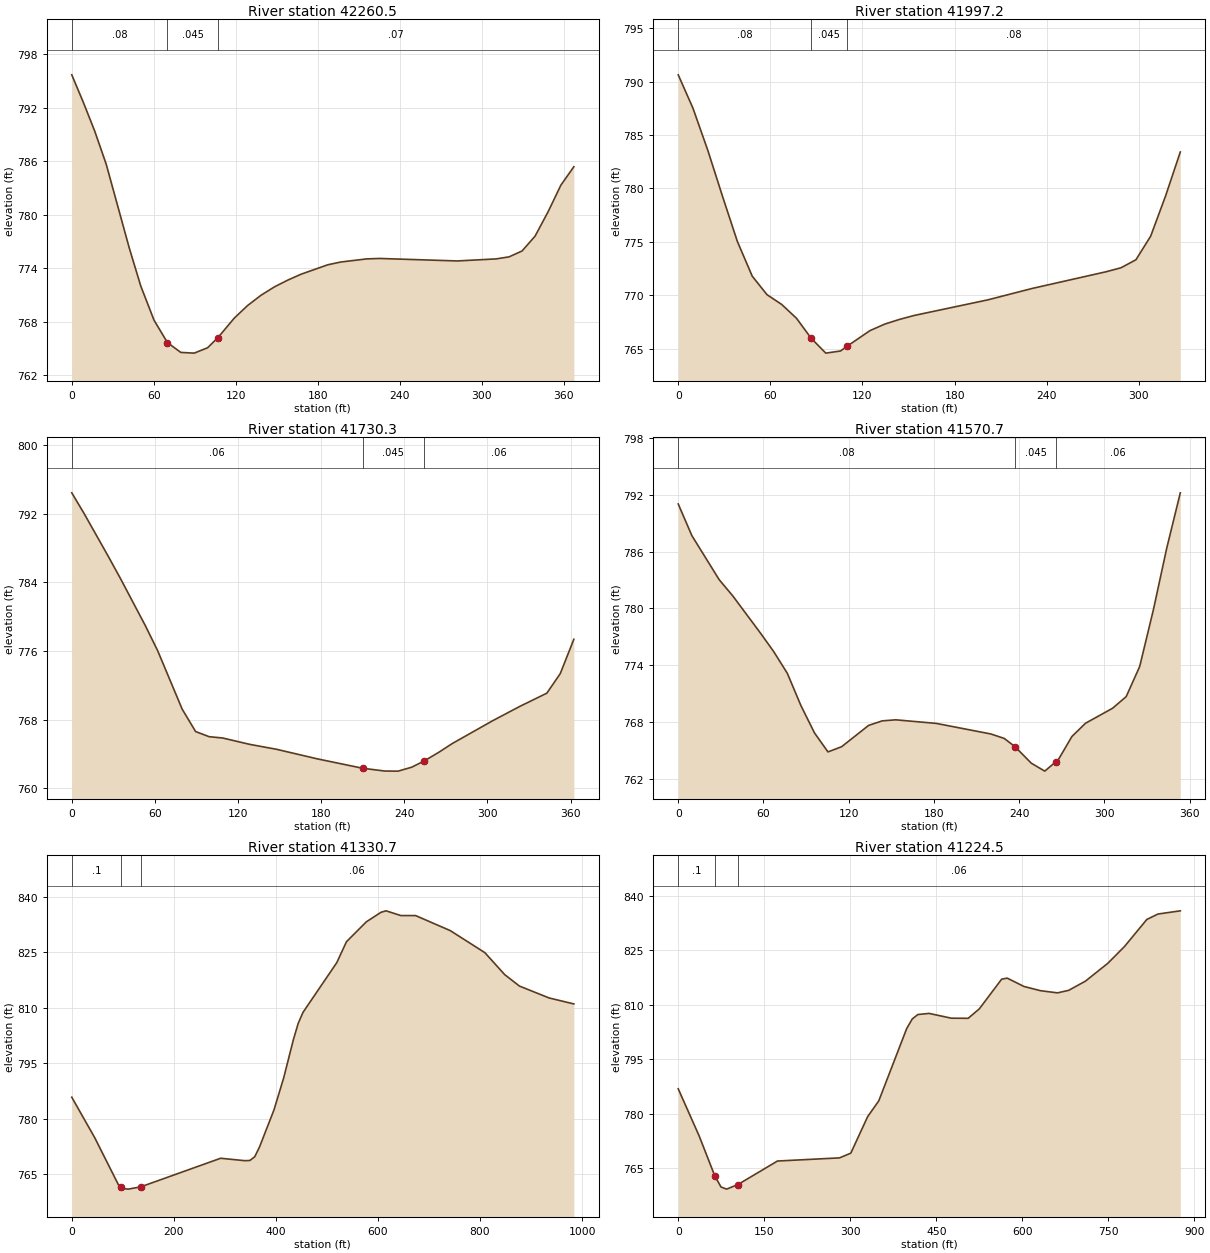
Type RM Length L Ch R = 1 ,42260.5 ,245.4,263.3,281.6
XS GIS Cut Line= 4
     1567312.184      335048.559      1567345.17      335086.753
     1567451.073      335173.559     1567530.934      335335.017
#Sta/Elev= 30
       0  795.68     8.4  792.62    16.8  789.37    25.2  785.66    42.1  776.25
    50.5  771.99    60.2  768.16      70  765.65    79.8  764.54    89.6  764.46
    99.4  765.06     107   766.2   118.9  768.38   128.7   769.8   138.5  770.95
   148.3  771.89   158.1  772.65   167.8  773.31   187.4  774.37   196.9  774.68
   215.8  775.03   225.3  775.08   282.2   774.8   310.6  775.03   320.1  775.26
   329.6  775.92   339.1  777.58   348.6   780.3     358   783.3   367.5  785.37
#Mann= 3 , 0 , 0
       0     .08       0      70    .045       0     107     .07       0
Bank Sta=70,107
XS Rating Curve= 0 ,0
Exp/Cntr=0.3,0.1

Type RM Length L Ch R = 1 ,41997.2 ,271.5,266.9,259.2
XS GIS Cut Line= 4
     1567173.295      335206.545     1567204.545      335255.156
     1567218.434      335407.934     1567275.726      335508.628
#Sta/Elev= 25
       0  790.65     9.6  787.52    19.3  783.56    28.9  779.24    38.5  775.04
    48.2  771.78    57.8  770.05    67.4  769.13      77  767.84    86.6  765.96
    96.1  764.57   105.7  764.77     110 765.218   124.9  766.68   134.5  767.29
   144.1  767.73   153.7   768.1   201.6  769.56   230.5  770.63   278.8   772.2
   288.4  772.57   298.1  773.32   307.7  775.53   317.4   779.3     327  783.42
#Mann= 3 , 0 , 0
       0     .08       0    86.6    .045       0     110     .08       0
Bank Sta=86.6,110
XS Rating Curve= 0 ,0
Exp/Cntr=0.3,0.1

Type RM Length L Ch R = 1 ,41730.3 ,165.2,159.6,156.8
XS GIS Cut Line= 3
     1566966.698      335269.045     1566982.323       335347.17
     1567114.267       335597.17
#Sta/Elev= 26
       0  794.42     8.8  792.04    26.6  786.95    35.4  784.36    53.1  778.95
      62  776.03    79.7  769.22    89.4  766.61    99.2  766.01   108.9  765.86
   128.4  765.12   147.9  764.54   177.2  763.43     210762.3335   225.9  762.01
   232.4     762   235.6     762   245.4  762.46     254763.1514   264.9  764.19
   274.6  765.21   303.9  767.88   323.4  769.54   342.9  771.08   352.6  773.36
   362.4  777.36
#Mann= 3 , 0 , 0
       0     .06       0     210    .045       0     254     .06       0
Bank Sta=210,254
XS Rating Curve= 0 ,0
Exp/Cntr=0.3,0.1

Type RM Length L Ch R = 1 ,41570.7 ,241.9,240,235.8
XS GIS Cut Line= 3
     1566800.031      335421.823     1566874.684      335465.225
     1567011.837      335694.392
#Sta/Elev= 30
       0  791.02     9.6  787.68    28.8  783.03    38.4  781.31    57.6  777.44
    67.2  775.43    76.8  773.13    86.4  769.71    95.9  766.84   105.4  764.83
     115  765.38     134  767.63   143.6  768.11   153.1  768.22   181.7  767.84
   219.9  766.73   229.4  766.26     237765.3892   248.5  763.64     258   762.8
     266763.8149   267.6  764.02   277.1  766.46   286.7  767.86   305.7  769.44
   315.3  770.67   324.8  773.85   334.4  779.81   343.9  786.39   353.4   792.2
#Mann= 3 , 0 , 0
       0     .08       0     237    .045       0     266     .06       0
Bank Sta=237,266
XS Rating Curve= 0 ,0
Exp/Cntr=0.3,0.1

Type RM Length L Ch R = 1 ,41330.7 ,93.7,106.2,118
XS GIS Cut Line= 5
     1566692.392      335529.462     1566718.434      335586.753
     1566900.726      335819.392     1567079.545      335838.489
      1567316.51      336215.819
#Sta/Elev= 30
       0   785.8      45  774.85    91.5   762.1      96761.6171   101.1  761.07
   110.6  760.94     135761.5483   291.8  769.29   339.4  768.63     349  768.69
   358.5  769.69     368  772.36   396.4  782.42   415.3  791.04   434.2  801.31
   443.7  805.75   453.1  808.74   519.4  822.21   538.3  827.85   577.1  833.22
   606.1  835.82   615.8  836.21   644.9  834.93   673.9  834.92   741.7  830.86
   809.5   824.9   848.3  818.97   877.3  815.86   935.5  812.64   983.9  811.03
#Mann= 3 , 0 , 0
       0      .1       0      96    .045       0     135     .06       0
Bank Sta=96,135
XS Rating Curve= 0 ,0
Exp/Cntr=0.3,0.1

Type RM Length L Ch R = 1 ,41224.5 ,449.4,442.4,435.3
XS GIS Cut Line= 4
      1566626.42      335567.656     1566643.781      335619.739
     1566678.503      335873.212     1566998.584      336338.431
#Sta/Elev= 30
       0  786.87    36.6  773.84      64762.7793    74.6  759.82    84.4  759.23
   104.1   760.5     173  766.97   281.2  767.84   300.9  769.14   330.2  779.18
   349.7  783.56   398.4  803.49   408.1  806.12   417.8  807.33   437.3  807.64
   476.2  806.32   505.5  806.29   524.9  808.88   563.9  817.07   573.6  817.36
   602.8  815.06     632  813.89   661.2   813.3   680.7  813.99   709.9  816.52
   748.9  821.43   778.1  826.07     817  833.52   836.5  835.02   875.4   835.9
#Mann= 3 , 0 , 0
       0      .1       0      64    .045       0   104.1     .06       0
Bank Sta=64,104.1
XS Rating Curve= 0 ,0
Exp/Cntr=0.3,0.1

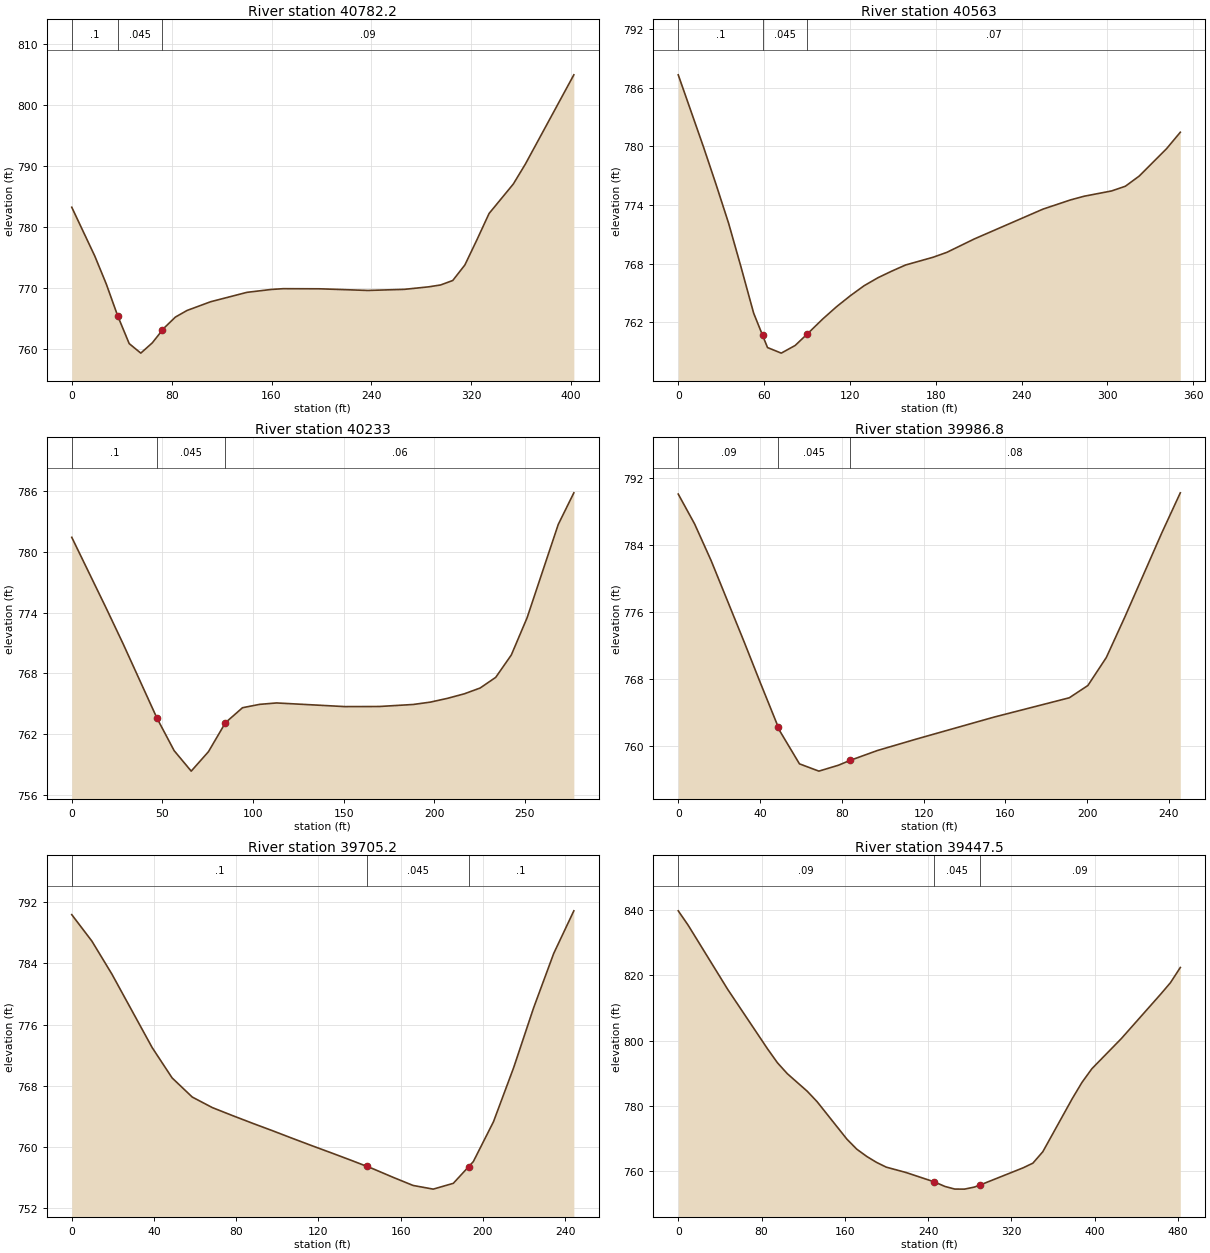
Type RM Length L Ch R = 1 ,40782.2 ,219.4,219.1,219.7
XS GIS Cut Line= 4
      1566243.05      335815.735     1566259.919      335848.407
     1566287.816      335906.854     1566499.995      336119.902
#Sta/Elev= 27
       0   783.2    18.4  775.23    27.6  770.66    36.8  765.42      46  760.88
    55.3  759.32    64.5     761    72.4763.0388    73.8   763.4      83  765.22
    92.3   766.3   111.2  767.73   140.3  769.27   159.7  769.74   169.4  769.87
   198.5  769.85   237.3  769.58   266.4  769.76   285.8  770.17   295.5  770.48
   305.2  771.21   314.9  773.75   324.6  777.89   334.3  782.18   353.7     787
   363.4  790.28   402.2  804.88
#Mann= 3 , 0 , 0
       0      .1       0    36.8    .045       0    72.4     .09       0
Bank Sta=36.8,72.4
XS Rating Curve= 0 ,0
Exp/Cntr=0.3,0.1

Type RM Length L Ch R = 1 ,40563   ,306.9,330.1,350
XS GIS Cut Line= 4
     1566027.028       335880.59     1566055.674      335924.861
     1566098.628      336021.953     1566114.253      336213.359
#Sta/Elev= 29
       0  787.31    17.6  779.96    26.4  776.12    35.2  772.14    43.9  767.65
    52.7  762.95      59760.6621    62.4  759.43      72  758.86    81.7  759.64
      90760.7899     101  762.35   110.6   763.6   120.3  764.73   129.9  765.75
   139.6  766.57   149.2  767.24   158.9  767.87   178.1  768.66   187.7  769.16
   206.9  770.53   254.9  773.58   274.1  774.52   283.7   774.9   302.9  775.44
   312.5  775.92   322.1  776.95   341.3  779.76   350.9  781.44
#Mann= 3 , 0 , 0
       0      .1       0      59    .045       0      90     .07       0
Bank Sta=59,90
XS Rating Curve= 0 ,0
Exp/Cntr=0.3,0.1

Type RM Length L Ch R = 1 ,40233   ,263,246.2,229.4
XS GIS Cut Line= 3
     1565873.382       335943.09     1565779.632      336138.403
     1565771.819      336198.298
#Sta/Elev= 23
       0   781.4    18.8   774.5    28.3  770.93    47.1  763.57    56.5   760.4
    65.9  758.39    75.4   760.3    84.8  763.16    94.2  764.63   103.6  764.96
     113   765.1   150.7  764.74   169.6  764.75   188.4  764.95   197.8  765.18
   207.2  765.55   216.6     766   225.3  766.57   233.9  767.62   242.5  769.82
   251.2  773.48   268.4  782.67     277  785.78
#Mann= 3 , 0 , 0
       0      .1       0    47.1    .045       0    84.8     .06       0
Bank Sta=47.1,84.8
XS Rating Curve= 0 ,0
Exp/Cntr=0.3,0.1

Type RM Length L Ch R = 1 ,39986.8 ,266.9,281.6,295.4
XS GIS Cut Line= 4
     1565611.663      335935.278     1565594.736      335971.736
     1565631.194      336090.225     1565620.778      336170.955
#Sta/Elev= 20
       0  790.12       8  786.56    16.1  782.17    32.2  772.49    40.2  767.56
      49 762.243    49.7  761.82    59.3   757.9    68.8  757.03    78.3  757.73
      84758.3059    97.4  759.49   116.5  760.86   154.6  763.49   191.3  765.79
   200.4  767.26   209.4   770.6   218.4   775.4   236.5  785.46   245.6  790.27
#Mann= 3 , 0 , 0
       0     .09       0      49    .045       0      84     .08       0
Bank Sta=49,84
XS Rating Curve= 0 ,0
Exp/Cntr=0.3,0.1

Type RM Length L Ch R = 1 ,39705.2 ,268.7,257.7,246.6
XS GIS Cut Line= 2
      1565409.84      335893.611     1565333.017      336125.382
#Sta/Elev= 30
       0  790.35     9.8  786.89    19.5   782.6    29.3   777.8    39.1     773
    48.8  769.04    58.6  766.54    68.4  765.16    78.1  764.13    87.9  763.12
    97.7  762.14   107.4  761.14   117.2  760.15     127  759.18   136.7   758.2
   143.6757.4818   146.5  757.18   156.3  756.06     166     755   171.1  754.75
   175.8  754.52   185.6  755.28   186.1  755.43     193  757.44   195.3  758.11
   205.1  763.31   214.9  770.36   224.6  778.16   234.4  785.28   244.2  790.85
#Mann= 3 , 0 , 0
       0      .1       0   143.6    .045       0     193      .1       0
Bank Sta=143.6,193
XS Rating Curve= 0 ,0
Exp/Cntr=0.3,0.1

Type RM Length L Ch R = 1 ,39447.5 ,125.8,121.6,115.6
XS GIS Cut Line= 4
     1565196.284      335766.745     1565093.434      335915.746
     1565119.476      336073.298     1565185.882      336198.298
#Sta/Elev= 30
       0  839.64     9.5  835.26    47.6   815.6    85.8  797.46    95.3  793.21
   104.8  789.87   123.9  784.52   133.4  781.32     162  769.88   171.5  766.81
     181  764.61   190.4  762.79   199.8  761.32   218.6   759.7     246756.8145
   256.2  755.42   265.6  754.62     275   754.6   284.4  755.22     290755.8634
   331.4  761.12   340.7  762.54   350.2  766.02   378.5  782.25   387.9  787.24
   397.4  791.41   425.7  800.62   463.4  814.16   472.8  817.67   482.3  822.32
#Mann= 3 , 0 , 0
       0     .09       0     246    .045       0     290     .09       0
Bank Sta=246,290
XS Rating Curve= 0 ,0
Exp/Cntr=0.3,0.1

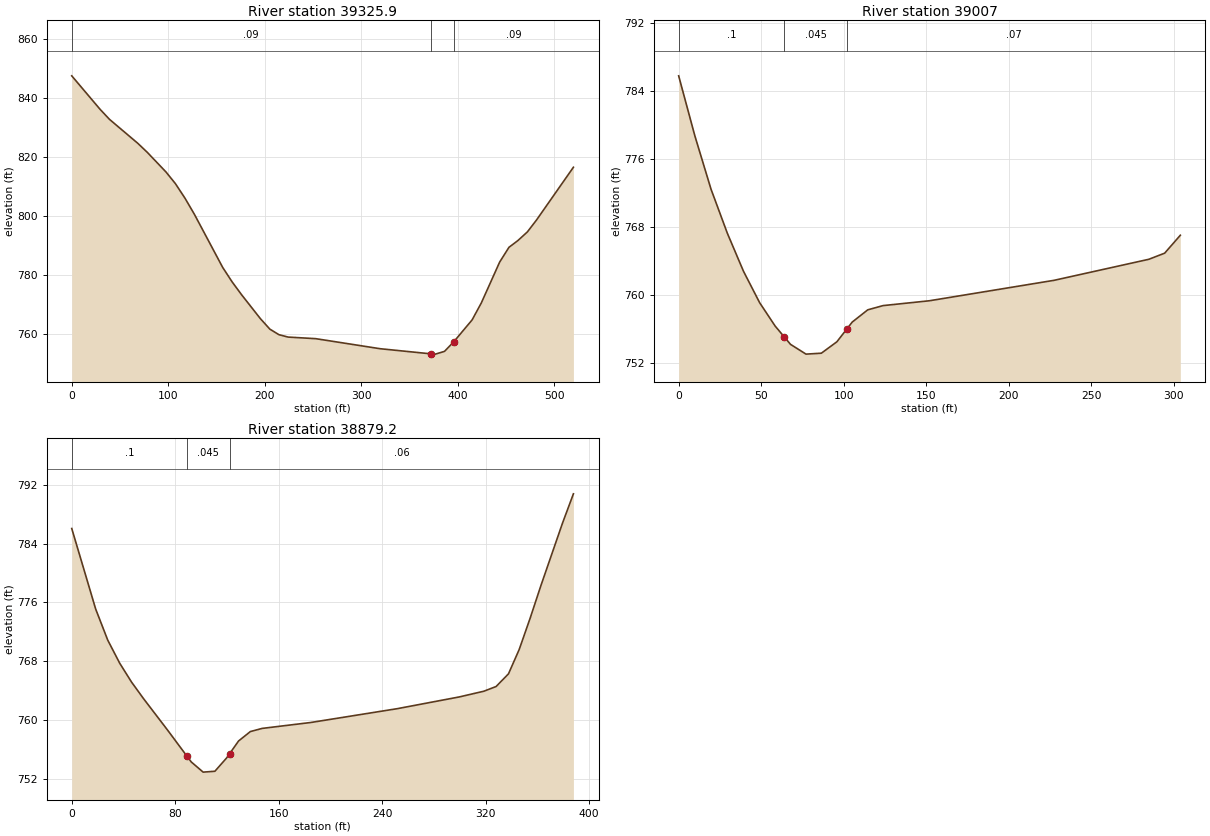
Type RM Length L Ch R = 1 ,39325.9 ,328.6,319,308.5
XS GIS Cut Line= 4
     1564796.544      335850.078     1564981.455      335939.184
     1565060.882      336133.194     1565135.101      336207.413
#Sta/Elev= 30
       0  847.49    29.3  836.18    39.1  832.76    68.4  824.66    78.2  821.62
    97.7  814.93   107.5  810.96   117.3  806.09   127.1  800.62   156.4  782.65
   166.2  777.74   175.9  773.43   195.5  765.29   205.3  761.74   214.8  759.85
   224.3  759.05   252.9  758.51   319.6  755.11     372753.3817   376.8  753.28
   386.3  754.21     396757.4973   414.9  764.86   424.4  770.57   443.5  784.46
   453.1  789.43   462.6  791.79   472.2  794.66   481.7   798.7   519.9  816.54
#Mann= 3 , 0 , 0
       0     .09       0     372    .045       0     396     .09       0
Bank Sta=372,396
XS Rating Curve= 0 ,0
Exp/Cntr=0.3,0.1

Type RM Length L Ch R = 1 ,39007   ,140.2,127.7,114.8
XS GIS Cut Line= 4
     1564741.871      336077.205     1564767.913      336118.871
     1564864.267      336207.413     1564977.549      336258.194
#Sta/Elev= 21
       0   785.8     9.8  778.75    19.6  772.47    29.5  767.28    39.3   762.8
    49.1   759.1    58.5  756.35      64755.0785    67.8   754.2    77.2  753.05
    86.5  753.16    95.9   754.5     102756.0217   105.2  756.82   114.6  758.26
   123.9  758.76     152  759.33   227.7  761.74     285  764.21   294.6  764.93
   304.1  767.04
#Mann= 3 , 0 , 0
       0      .1       0      64    .045       0     102     .07       0
Bank Sta=64,102
XS Rating Curve= 0 ,0
Exp/Cntr=0.3,0.1

Type RM Length L Ch R = 1 ,38879.2 ,131.3,144.6,158
XS GIS Cut Line= 5
     1564640.309      336211.319     1564704.111       336249.08
      1564784.84      336264.705      1564965.83      336275.121
     1565008.799      336301.163
#Sta/Elev= 27
       0  786.06    18.5   775.1    27.8  770.88    37.1  767.72    46.3  765.14
    55.6  762.88    74.1  758.62      89755.0895    92.4  754.29   101.6   752.9
   110.7  753.02   119.8  754.84     122  755.39     129  757.14   138.1  758.42
   147.2  758.85     185  759.66   251.8  761.54   299.5  763.13   318.6  763.91
   328.1  764.55   337.7  766.28     346   769.6   354.4  773.83   362.8  778.31
   379.5  786.81   387.9  790.78
#Mann= 3 , 0 , 0
       0      .1       0      89    .045       0     122     .06       0
Bank Sta=89,122
XS Rating Curve= 0 ,0
Exp/Cntr=0.3,0.1