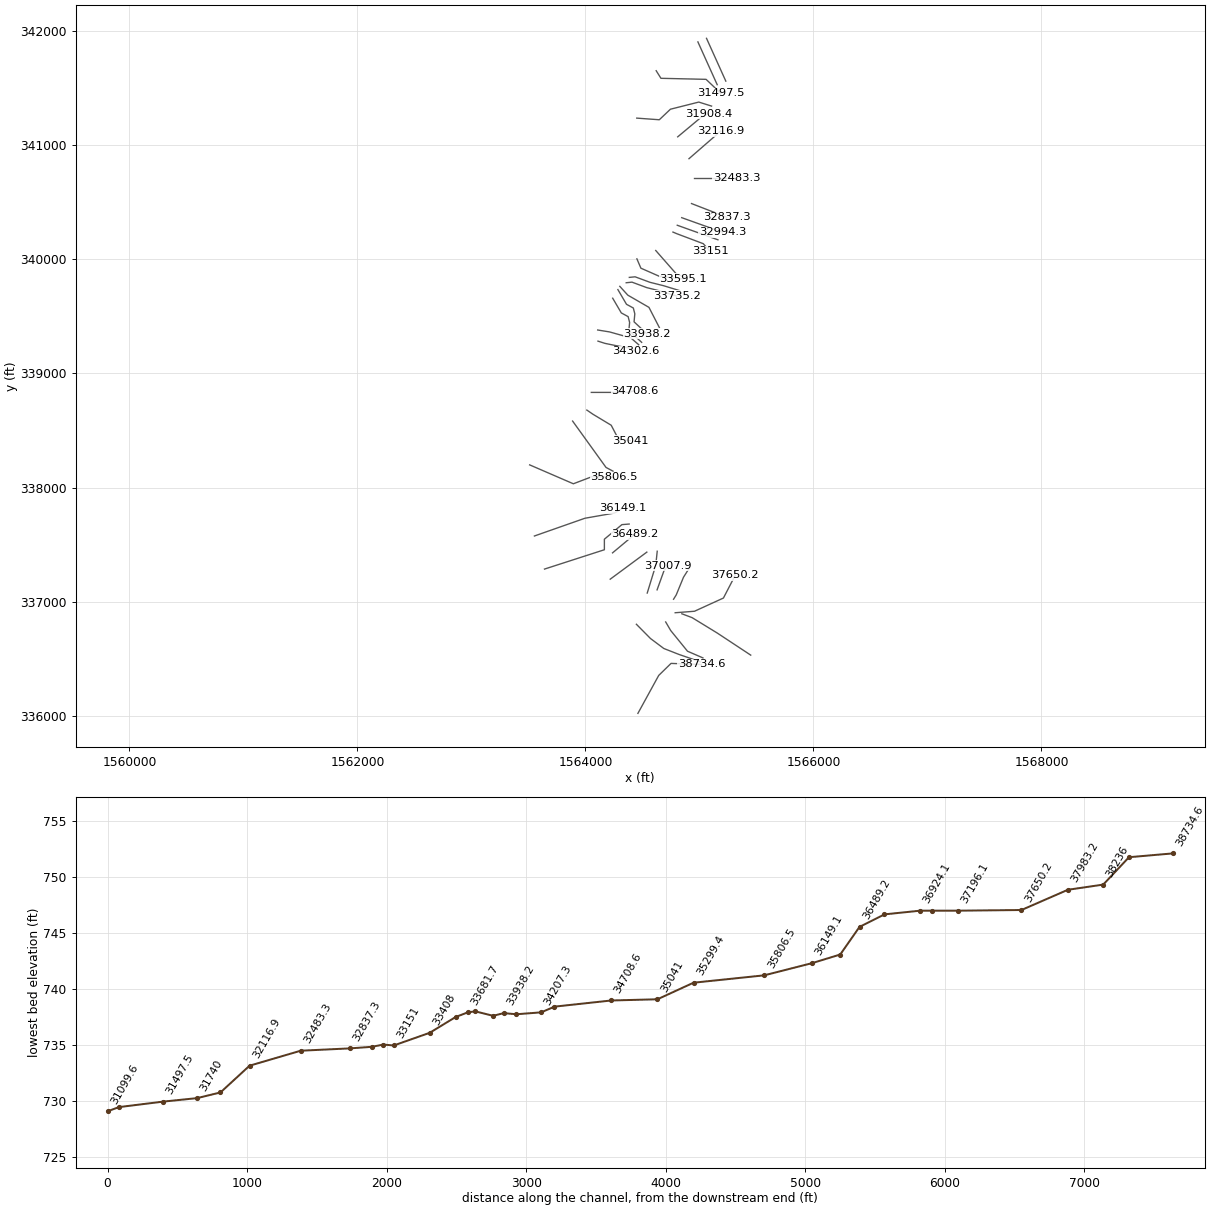
HEC-RAS study SNCHOCRK.prj: SNCHOCRK

--- SNCHOCRK.g01 (geometry) --- (continued)

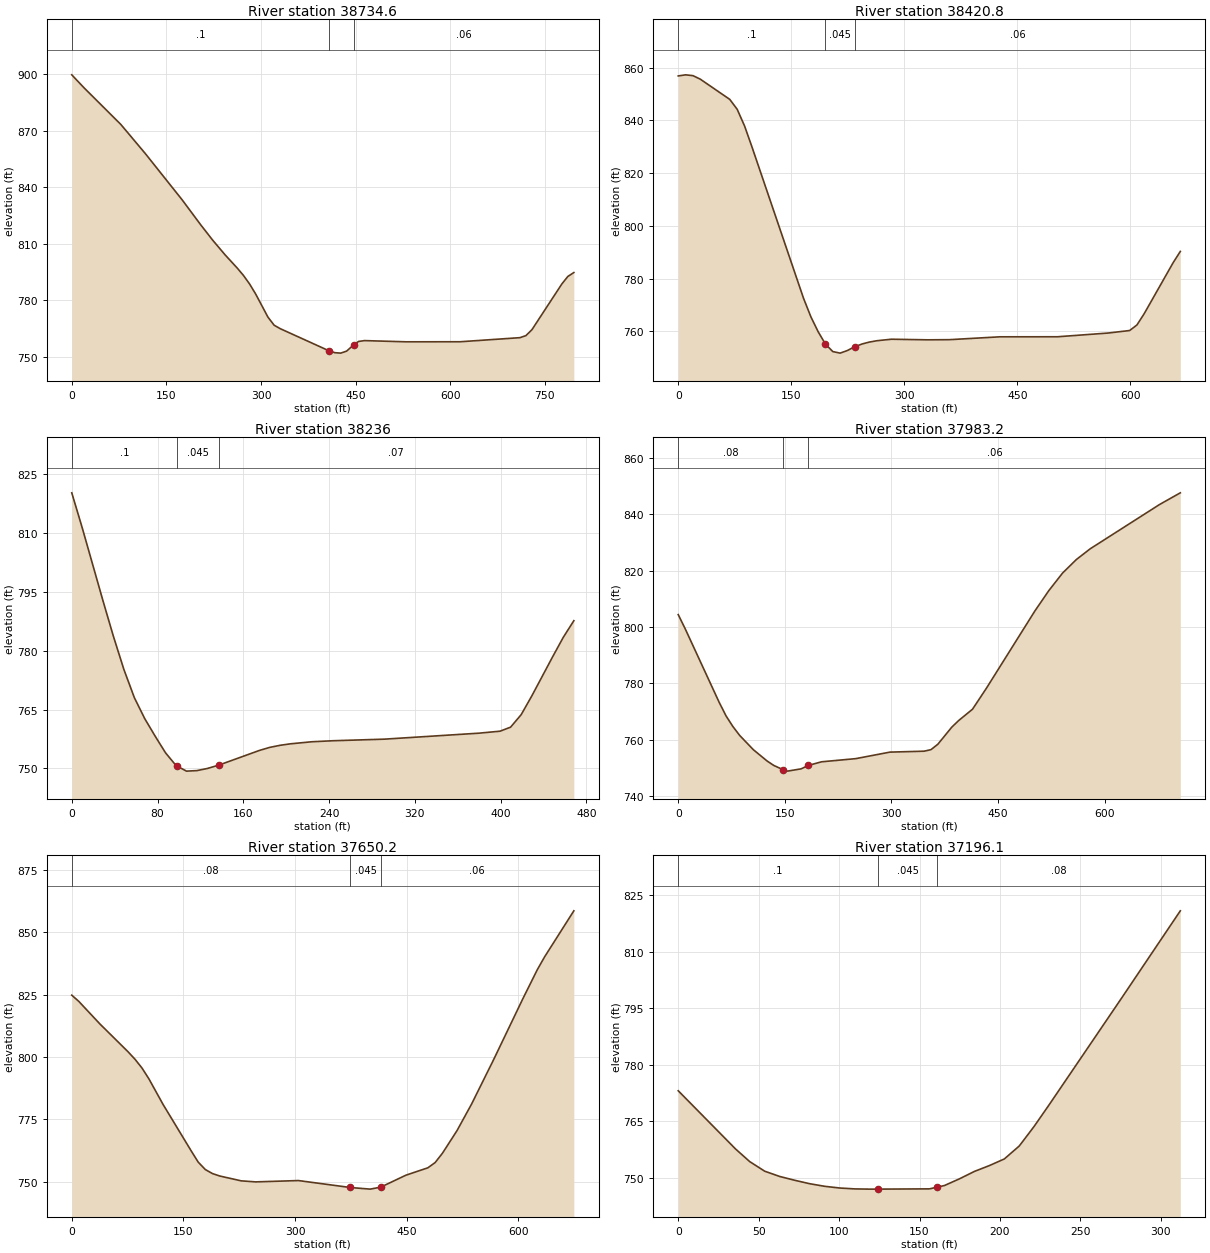
Type RM Length L Ch R = 1 ,38734.6 ,345.5,313.8,283.9
XS GIS Cut Line= 4
      1564460.47      336020.817     1564642.913      336353.246
     1564750.986      336458.715     1565016.611        336449.6
#Sta/Elev= 30
       0  899.49    19.4  892.63    77.8  873.21   116.7  857.75     175  833.29
   204.2  820.18   223.6  811.86   243.1  804.16   262.5  797.11   272.2  793.26
     282   788.7   291.7  783.34   311.1  771.14   320.9  766.89   330.6  765.06
     408753.3267     417  752.36   426.4  752.12   435.8   753.2     447756.5143
   454.7   758.3   464.1  758.75   530.2  758.11   615.6  758.14   710.6  760.31
     720  761.38   729.6  764.55     777  788.75   786.5  792.73     796  794.79
#Mann= 3 , 0 , 0
       0      .1       0     408    .045       0     447     .06       0
Bank Sta=408,447
XS Rating Curve= 0 ,0
Exp/Cntr=0.3,0.1

Type RM Length L Ch R = 1 ,38420.8 ,190,184.8,176.7
XS GIS Cut Line= 5
     1564447.148      336801.638     1564571.037      336676.638
      1564687.67      336589.459     1564821.037      336537.194
     1565011.403      336471.736
#Sta/Elev= 30
       0  856.83     9.8  857.25    19.6  856.93    29.3   855.6    68.4  847.94
    78.2   844.2      88  837.88    97.8  829.96   166.2  772.61     176  765.55
   185.7  759.87   195.4  755.17   205.1  752.37   214.8  751.78   224.5  752.78
   234.2   754.2     244  755.25   253.6  755.97   263.4  756.47   282.8  757.05
   331.2  756.82   359.8  756.88   426.6  757.96   503.2  757.98   570.3  759.39
     599  760.35   608.6  762.44   618.2  766.69   656.6  786.01   666.2  790.32
#Mann= 3 , 0 , 0
       0      .1       0   195.4    .045       0   234.2     .06       0
Bank Sta=195.4,234.2
XS Rating Curve= 0 ,0
Exp/Cntr=0.3,0.1

Type RM Length L Ch R = 1 ,38236   ,245.3,252.8,261.5
XS GIS Cut Line= 4
     1564704.111      336821.996     1564748.382      336746.475
     1564895.517      336565.486     1565030.934      336506.892
#Sta/Elev= 30
       0   820.1     9.7  811.26    29.2  792.57    38.9  783.56    48.6  775.19
    58.4     768    68.1  762.66    77.8  758.21    87.5  753.97    97.3  750.74
      98750.6379     107  749.33   116.7  749.46   126.4     750     137750.8435
     175  754.59   184.7  755.37   194.4   755.9   204.2  756.28   223.6  756.79
     243  757.05   291.6  757.46   379.8  758.98   399.5  759.49   409.3  760.51
   419.2   763.7     429  768.41   448.7   778.5   458.5  783.38   468.3  787.58
#Mann= 3 , 0 , 0
       0      .1       0      98    .045       0     137     .07       0
Bank Sta=98,137
XS Rating Curve= 0 ,0
Exp/Cntr=0.3,0.1

Type RM Length L Ch R = 1 ,37983.2 ,310.1,333,354.2
XS GIS Cut Line= 4
     1564846.038      336893.611     1564935.882      336859.757
     1565157.236       336724.34     1565450.053      336531.234
#Sta/Elev= 30
       0  804.37     9.6  799.45    57.6  773.27    67.2  768.48    76.8  764.72
    86.4  761.54   105.6  756.49   124.8   752.5   134.4  750.89     147749.4423
   153.7  748.87   172.9  749.68     183750.8874   201.7  752.18   249.8   753.3
   297.8  755.61   345.9  755.94   355.5  756.48   365.2   758.4   384.7  764.43
   394.5  766.81     414  770.83   433.4  778.21   501.6  805.62   521.1   812.8
   540.6  819.09   560.1  823.91   579.6  827.72     677   843.4   706.3  847.56
#Mann= 3 , 0 , 0
       0     .08       0     147    .045       0     183     .06       0
Bank Sta=147,183
XS Rating Curve= 0 ,0
Exp/Cntr=0.3,0.1

Type RM Length L Ch R = 1 ,37650.2 ,429.8,454.1,470.4
XS GIS Cut Line= 4
     1564787.444      336902.725     1564956.715      336915.746
     1565210.621      337031.632     1565314.636      337231.755
#Sta/Elev= 30
       0  824.77     9.4  822.29    37.7  813.27    75.4  802.15    84.9  799.11
    94.3  795.59   103.8  791.15   122.6  781.01   160.3  762.44   169.8   757.9
   179.4   754.9     189  753.29   198.6  752.33   227.5  750.38   246.8  749.96
   304.5  750.49     374747.7147   400.8  747.06     415747.8531   448.9  752.65
   478.3   755.6   488.1  757.71   497.9  761.44   517.5  770.52   537.1  781.18
   566.6  798.91   605.8  823.28   625.4  835.02   635.2  840.16   674.4  858.56
#Mann= 3 , 0 , 0
       0     .08       0     374    .045       0     415     .06       0
Bank Sta=374,415
XS Rating Curve= 0 ,0
Exp/Cntr=0.3,0.1

Type RM Length L Ch R = 1 ,37196.1 ,194.7,188.2,189.2
XS GIS Cut Line= 4
     1564773.121      337021.215     1564796.559      337058.975
     1564860.361      337213.923     1564913.746      337298.559
#Sta/Elev= 24
       0  773.12    35.6  757.68    44.4  754.32    53.8  751.75    63.1  750.36
    72.4  749.35    81.7  748.44      91  747.75   100.3   747.3   109.6  747.06
   118.9     747     124     747   156.2  747.07     161747.5291   165.5  747.96
   174.8  749.73   184.1   751.7   193.4  753.25   202.7  755.01     212  758.46
   221.1  763.58   230.2  769.17   275.7  797.79   312.1   820.9
#Mann= 3 , 0 , 0
       0      .1       0     124    .045       0     161     .08       0
Bank Sta=124,161
XS Rating Curve= 0 ,0
Exp/Cntr=0.3,0.1

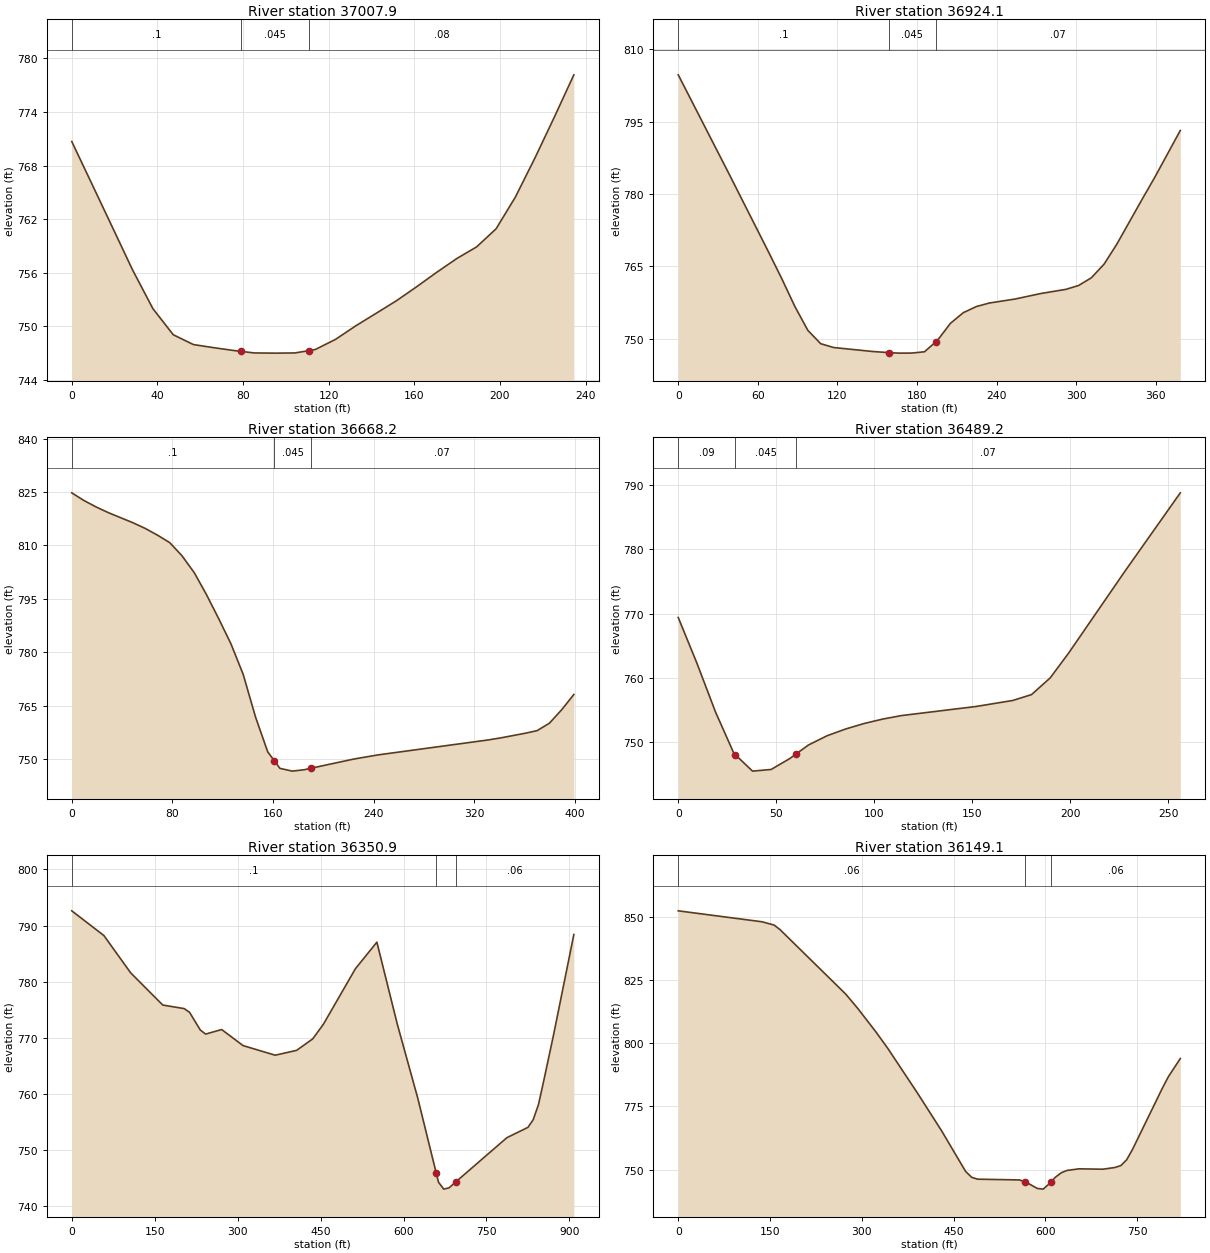
Type RM Length L Ch R = 1 ,37007.9 ,82.3,83.9,84
XS GIS Cut Line= 3
      1564628.59      337103.246     1564689.788      337272.517
     1564724.944      337314.184
#Sta/Elev= 30
       0   770.7     9.5   765.9      19  761.09    28.4  756.32    37.9  751.98
    47.4  749.06    56.8  747.96    66.3  747.61    75.8  747.29      79 747.199
    85.3  747.02    94.7     747    95.8     747   104.2  747.02   110.8  747.28
     111747.2883   113.7   747.4   123.2  748.54   132.6  750.05   142.1  751.45
   151.6  752.86     161  754.42   170.5  756.06     180  757.62   189.1   758.9
   198.2  760.93   207.2  764.48   216.3  768.84   225.4  773.44   234.5  778.17
#Mann= 3 , 0 , 0
       0      .1       0      79    .045       0     111     .08       0
Bank Sta=79,111
XS Rating Curve= 0 ,0
Exp/Cntr=0.3,0.1

Type RM Length L Ch R = 1 ,36924.1 ,270.3,255.8,240.7
XS GIS Cut Line= 3
     1564542.204      337075.338     1564616.871       337318.09
     1564629.892      337441.788
#Sta/Elev= 29
       0  804.74    39.1  783.75    68.4   767.8    78.2  762.36    87.9  756.68
    97.7  751.72   107.4  748.95   117.2  748.16   146.5  747.34     159747.1014
   166.1     747   175.8  747.01   185.6  747.28     194749.3115   195.4  749.65
   205.1  753.17   214.9   755.4   224.7  756.66   234.4  757.39     254  758.23
   273.1  759.36   292.2  760.23   301.8  761.04   311.4  762.64     321  765.48
   330.5  769.58   349.6  778.91   359.2   783.5   378.4   793.2
#Mann= 3 , 0 , 0
       0      .1       0     159    .045       0     194     .07       0
Bank Sta=159,194
XS Rating Curve= 0 ,0
Exp/Cntr=0.3,0.1

Type RM Length L Ch R = 1 ,36668.2 ,177.8,179,180.2
XS GIS Cut Line= 2
     1564217.551      337196.866     1564538.746      337433.975
#Sta/Elev= 30
       0  824.76     9.7   822.6    19.5  820.77    29.2  819.18    48.7  816.36
    58.4  814.77    68.2  812.88    77.9  810.78    87.6  807.12    97.4  802.35
   107.1   796.2   116.8  789.47   126.6  782.36   136.3  773.82   146.1  761.86
   155.8  752.08     161749.5989   165.5  747.45   175.3  746.67     185  747.07
     190 747.468     224  750.04   243.4  751.22   331.1  755.42   340.8  755.98
   360.3  757.28     370  758.03   379.8  760.13   389.5  763.88   399.2  768.18
#Mann= 3 , 0 , 0
       0      .1       0     161    .045       0     190     .07       0
Bank Sta=161,190
XS Rating Curve= 0 ,0
Exp/Cntr=0.3,0.1

Type RM Length L Ch R = 1 ,36489.2 ,138.4,138.3,138.3
XS GIS Cut Line= 2
     1564237.965      337427.465      1564434.58      337591.528
#Sta/Elev= 22
       0   769.4     9.5  762.33      19  754.74    28.4   748.3      29 748.128
    37.9  745.55    47.4  745.81    56.9   747.5      60748.1852    66.4   749.6
    75.9  751.04    85.4  752.09    94.8  752.94   104.3  753.63   113.8  754.17
   151.8  755.58   170.7  756.52   180.2  757.43   189.7  760.01   199.2   763.9
   227.6  776.47   256.1  788.75
#Mann= 3 , 0 , 0
       0     .09       0      29    .045       0      60     .07       0
Bank Sta=29,60
XS Rating Curve= 0 ,0
Exp/Cntr=0.3,0.1

Type RM Length L Ch R = 1 ,36350.9 ,213.5,201.8,190
XS GIS Cut Line= 5
     1563641.163      337285.408     1564166.351      337454.809
     1564166.351      337547.257     1564319.996      337674.861
     1564383.799      337680.069
#Sta/Elev= 30
       0  792.64    58.1  788.24   106.5   781.6   164.6  775.86   203.3  775.23
     213  774.57   232.4  771.42     242  770.69   271.1   771.5   309.8  768.64
   367.9  766.93   406.6  767.79   435.7  769.83     455  772.43   513.1  782.35
   551.8  787.06   588.8  772.43   625.8  759.26     659745.9928   663.3   744.3
   672.8  743.08   682.3  743.31     694744.3269   786.9  752.24     825  754.08
   834.5  755.45     844  758.12   853.2  762.21   871.4  770.59     908  788.42
#Mann= 3 , 0 , 0
       0      .1       0     659    .045       0     694     .06       0
Bank Sta=659,694
XS Rating Curve= 0 ,0
Exp/Cntr=0.3,0.1

Type RM Length L Ch R = 1 ,36149.1 ,338.2,342.6,346.7
XS GIS Cut Line= 4
     1563552.621      337575.338     1563995.778       337730.85
     1564254.892      337776.423     1564330.413      337820.694
#Sta/Elev= 30
       0  852.26     137  847.93   156.6  846.64   166.3  844.84     274  819.28
   293.5  813.65   322.9  804.45   342.4  797.92   391.4  780.06   430.5  765.27
   469.6  749.28   479.4  746.99   489.1  746.24   557.4  745.94   567.1  745.22
   586.6  742.59   596.3  742.31   609.4745.1222   615.8  746.93   625.6  748.75
   635.3   749.7   654.8  750.33   693.8  750.18   713.2  750.85     723  751.59
   732.7  753.93   742.5  758.13   791.1  782.25   800.8  786.72   820.3  793.92
#Mann= 3 , 0 , 0
       0     .06       0   567.1    .045       0   609.4     .06       0
Bank Sta=567.1,609.4
XS Rating Curve= 0 ,0
Exp/Cntr=0.3,0.1

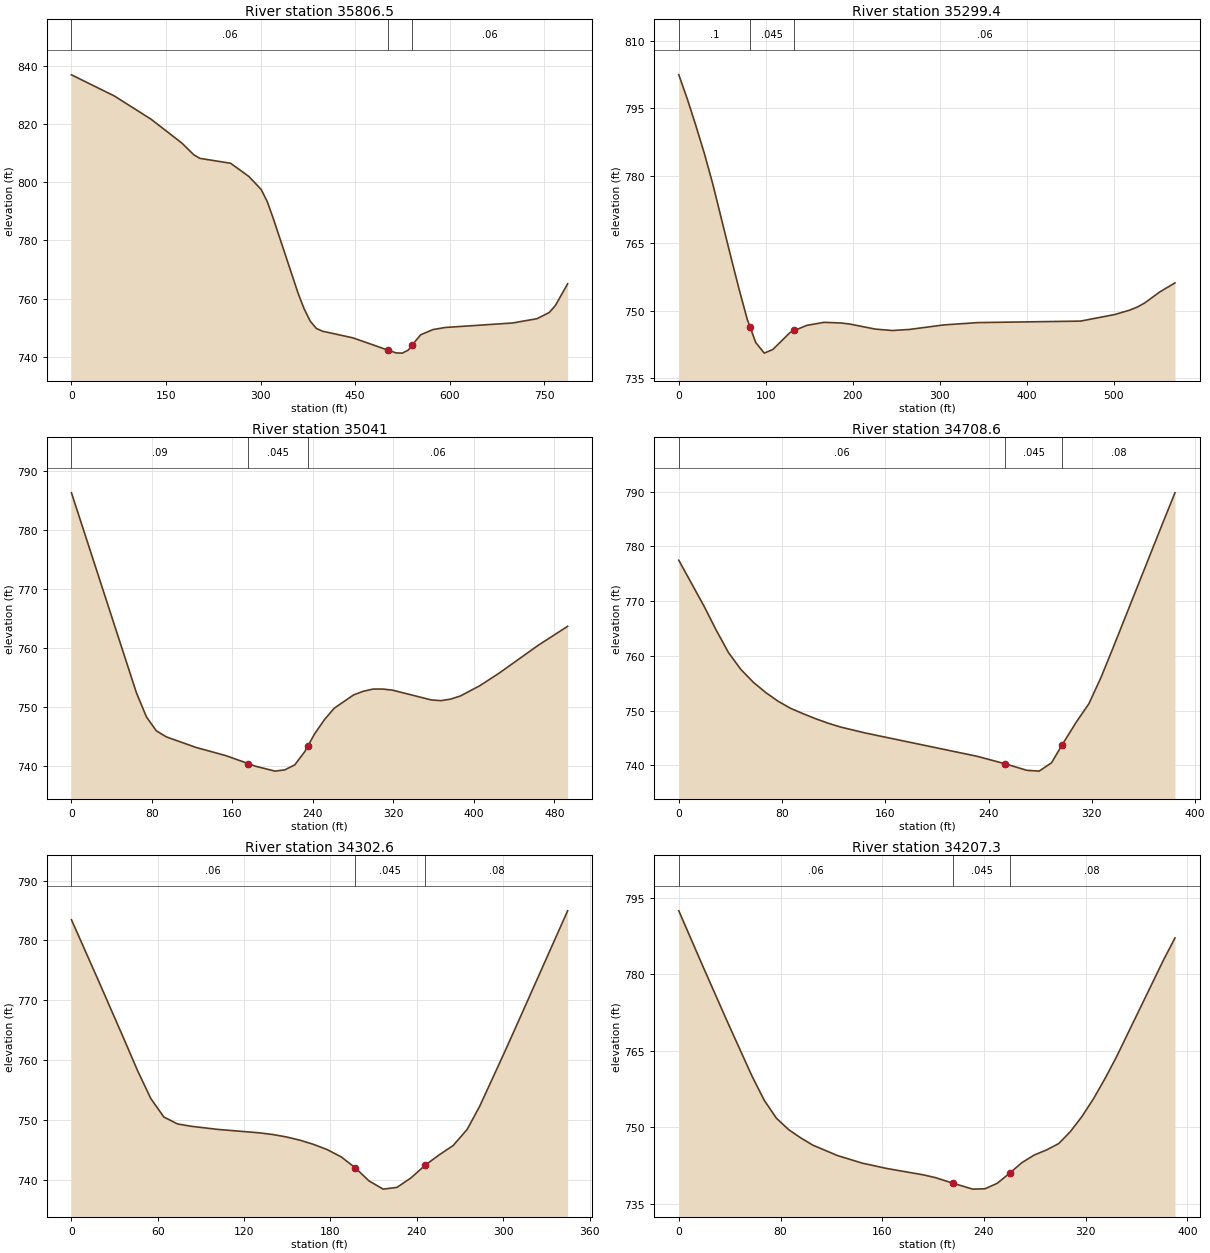
Type RM Length L Ch R = 1 ,35806.5 ,536.7,507.2,477
XS GIS Cut Line= 4
     1563510.954      338198.602     1563894.215      338032.934
     1564058.278      338095.434     1564252.288      338090.225
#Sta/Elev= 30
       0  836.92      68  829.65   126.2  821.67   174.8  813.52   194.2  809.41
   203.9  808.19   252.5  806.51   281.6  801.95     301   797.5   310.7  793.29
   320.4   787.4   359.3  761.98     369  756.52   378.7  752.26   388.4  749.73
   398.1  748.77   446.8  746.46     502742.2623   515.1  741.29   524.8  741.22
   534.6  742.29     540743.8822   554.1  747.54   573.6  749.32   593.1  750.04
   699.8  751.58   738.7  753.06   758.1   755.2   767.8   757.6   787.2  765.05
#Mann= 3 , 0 , 0
       0     .06       0     502    .045       0     540     .06       0
Bank Sta=502,540
XS Rating Curve= 0 ,0
Exp/Cntr=0.3,0.1

Type RM Length L Ch R = 1 ,35299.4 ,240.8,258.3,272.3
XS GIS Cut Line= 3
     1563887.705      338582.413     1564180.674      338176.163
     1564241.871      338143.611
#Sta/Elev= 30
       0  802.45     9.8  797.06    19.6  791.16    29.5  784.88    39.3  777.99
    58.9  762.67    68.8  755.14    78.6  748.11      82746.3128    88.4  742.93
    98.2  740.56     108  741.36   127.7  745.11   132.7745.5947   147.3  746.74
     167  747.41   186.6  747.26   196.4  747.03   225.9   745.9   245.5  745.59
   265.2  745.83   304.4  746.83   343.7  747.35   461.6  747.68   500.9  749.14
   518.2  750.12   526.9   750.8   535.5  751.73   552.9  754.19   570.2  756.17
#Mann= 3 , 0 , 0
       0      .1       0      82    .045       0   132.7     .06       0
Bank Sta=82,132.7
XS Rating Curve= 0 ,0
Exp/Cntr=0.3,0.1

Type RM Length L Ch R = 1 ,35041   ,328.3,332.4,339.6
XS GIS Cut Line= 5
     1564012.705      338678.767      1564066.09      338642.309
     1564226.246      338545.955     1564288.746      338426.163
     1564394.215      338410.538
#Sta/Elev= 30
       0  786.22    64.6  752.34    74.5  748.28    84.3  745.92    94.2  744.89
   123.7   743.1   153.2  741.72   175.6740.3691   182.7  739.92   202.4  739.08
   212.2   739.3     222  740.14   231.9  742.37     235743.3221   241.7  745.38
   251.6  747.82   261.2  749.73   280.5  751.99   290.2  752.61   299.8  752.98
   309.5  752.98   319.1   752.8   357.7  751.14   367.4  751.02     377  751.28
   386.7  751.81     406  753.55   425.4   755.7   464.2  760.41   493.3  763.61
#Mann= 3 , 0 , 0
       0     .09       0   175.6    .045       0     235     .06       0
Bank Sta=175.6,235
XS Rating Curve= 0 ,0
Exp/Cntr=0.3,0.1

Type RM Length L Ch R = 1 ,34708.6 ,409.8,406,402
XS GIS Cut Line= 3
     1564051.767      338833.715     1564369.476      338833.715
      1564434.58      338848.038
#Sta/Elev= 26
       0  777.48    19.3  769.21    28.9  764.76    38.5  760.62    48.1  757.54
    57.8  755.19    67.4  753.31      77  751.73    86.6  750.44    96.3  749.46
   105.9  748.55   115.5  747.74   125.2  747.03   144.4  745.94   231.1  741.68
     253740.2959   269.6  739.12   279.2  738.97   288.8   740.5     297  743.78
   308.1  747.98   317.7  751.27   327.2  756.13   336.8   761.7   374.8   784.2
   384.4   789.8
#Mann= 3 , 0 , 0
       0     .06       0     253    .045       0     297     .08       0
Bank Sta=253,297
XS Rating Curve= 0 ,0
Exp/Cntr=0.3,0.1

Type RM Length L Ch R = 1 ,34302.6 ,97.6,95.3,93
XS GIS Cut Line= 5
     1564110.361      339282.934     1564171.559      339263.403
     1564273.121      339242.569      1564378.59       339224.34
      1564441.09       339193.09
#Sta/Elev= 30
       0  783.45    18.4  773.47    36.7   763.4    45.9  758.25    55.1  753.58
    64.2  750.48    73.7  749.32    83.1  748.93   101.9   748.4   130.2  747.84
   139.6  747.56   149.1  747.16   158.5  746.62   167.9  745.93   177.6  745.04
   187.4  743.82   197.1  742.01   206.8  739.79   216.6  738.42   226.2  738.71
     236  740.31   245.8  742.42   255.5  744.14   265.2   745.7     275  748.41
   283.7  752.28   292.4  756.83   301.2  761.44   309.9   766.1   344.8  784.95
#Mann= 3 , 0 , 0
       0     .06       0   197.1    .045       0   245.8     .08       0
Bank Sta=197.1,245.8
XS Rating Curve= 0 ,0
Exp/Cntr=0.3,0.1

Type RM Length L Ch R = 1 ,34207.3 ,182.1,177.2,140.6
XS GIS Cut Line= 4
     1564107.757       339380.59     1564211.924      339363.663
     1564398.121       339311.58     1564467.132      339251.684
#Sta/Elev= 30
       0  792.43    19.2  781.42    38.4   770.6    57.6  760.04    67.2  755.32
    76.8   751.8    86.4  749.57    95.9  747.95   105.5  746.52   124.9  744.48
   144.2  743.01   163.5  741.96   192.5   740.7   202.2  740.14     216739.0441
   231.2  737.91   240.9  737.98   250.5  739.05   260.2  741.03   269.9   743.1
   279.5  744.58   289.2  745.58   298.9  746.84     308  749.17   317.2  752.16
   326.3  755.65   335.4  759.62   344.6  763.97   381.1   782.7   390.3  787.11
#Mann= 3 , 0 , 0
       0     .06       0     216    .045       0   260.2     .08       0
Bank Sta=216,260.2
XS Rating Curve= 0 ,0
Exp/Cntr=0.3,0.1

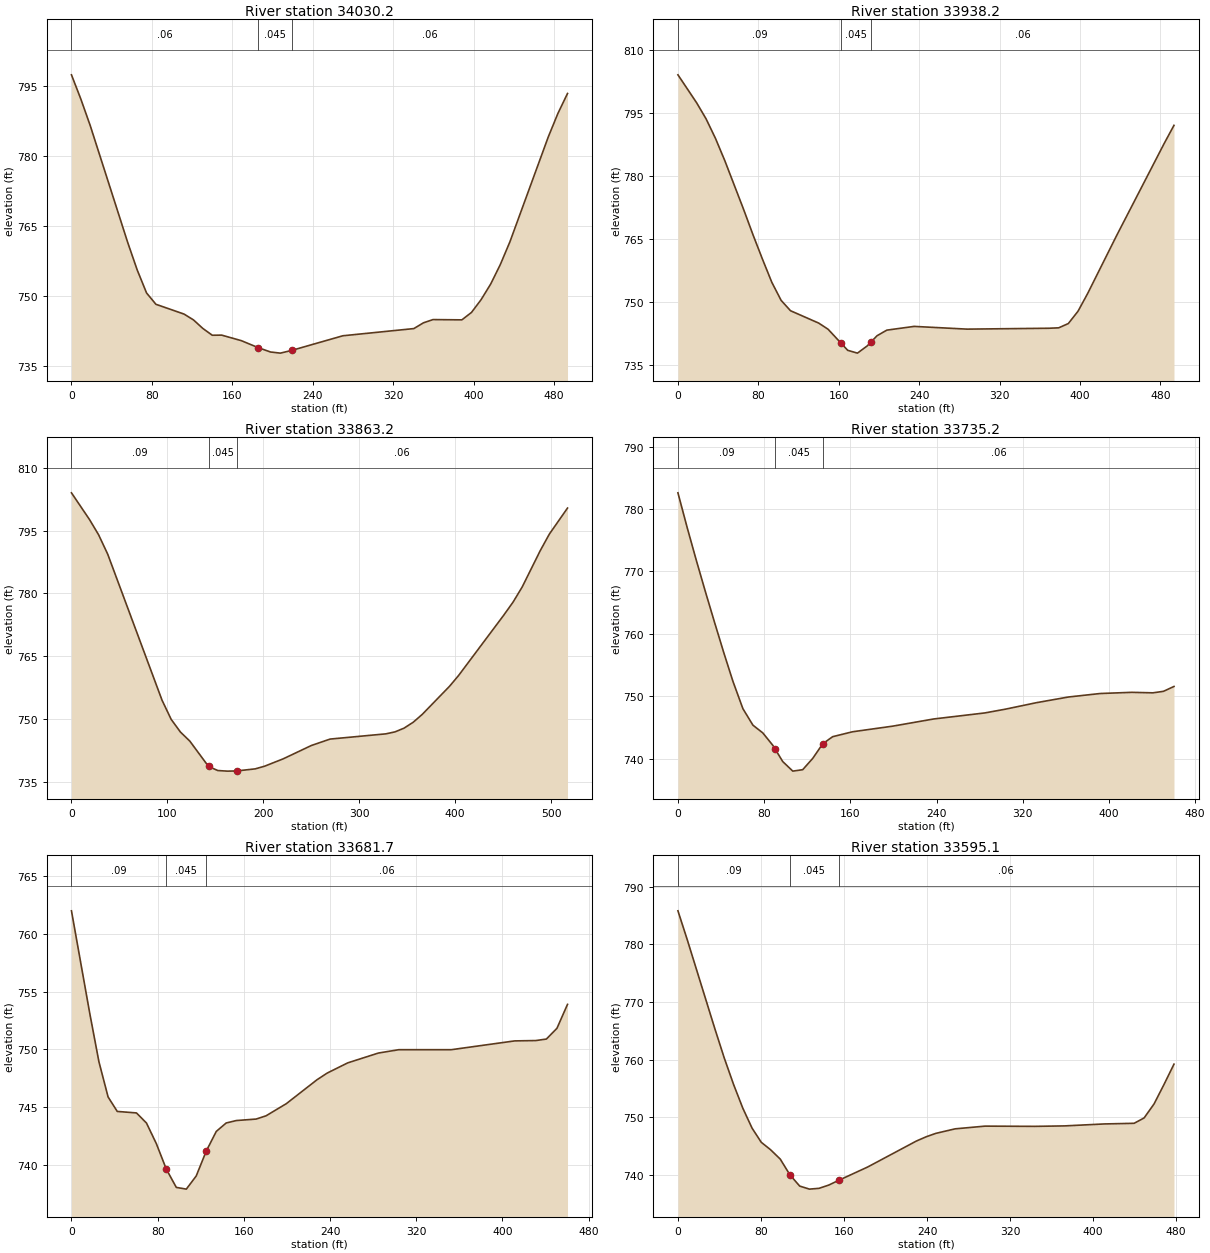
Type RM Length L Ch R = 1 ,34030.2 ,92.1,92,123.4
XS GIS Cut Line= 6
     1564239.267      339659.236     1564314.788       339530.33
     1564374.684      339497.778     1564387.705      339446.996
     1564381.194      339376.684     1564493.174      339272.517
#Sta/Elev= 30
       0  797.39     9.3  792.21    18.7  786.49      56  761.43    65.4  755.57
    74.7  750.64      84  748.21     112  746.11   121.4  744.86   130.7  743.03
   140.1  741.57   149.4   741.6   168.9  740.42     186738.8963   198.1  737.98
   207.8  737.74     219738.3172     270  741.46   340.6     743   350.2  744.24
   359.7  744.93   388.4  744.87     398  746.47   407.5  749.19   417.1  752.56
   426.6   756.7   436.2   761.6   474.4   784.1     484  789.14   493.5  793.39
#Mann= 3 , 0 , 0
       0     .06       0     186    .045       0     219     .06       0
Bank Sta=186,219
XS Rating Curve= 0 ,0
Exp/Cntr=0.3,0.1

Type RM Length L Ch R = 1 ,33938.2 ,75.7,74.9,74.5
XS GIS Cut Line= 6
      1564284.84      339734.757     1564360.361       339605.85
     1564420.257      339573.298     1564433.278      339522.517
     1564426.767      339452.205     1564538.746      339348.038
#Sta/Elev= 30
       0  804.06    18.7  797.37      28  793.59    37.4  788.91    46.7   783.6
    65.4     772    74.7  765.99      84  760.26    93.4  754.69   102.7  750.38
     112  747.93   140.1  744.98   149.4  743.52     162740.2843   168.9  738.51
   178.6  737.84   188.4  739.57     192740.4645   198.1  741.98   207.8  743.31
     235   744.2   287.6  743.55   369.3  743.76   378.8  743.86   388.4  744.88
     398   747.8   407.5  751.97   436.2   765.7     484  787.84   493.5  792.04
#Mann= 3 , 0 , 0
       0     .09       0     162    .045       0     192     .06       0
Bank Sta=162,192
XS Rating Curve= 0 ,0
Exp/Cntr=0.3,0.1

Type RM Length L Ch R = 1 ,33863.2 ,124,128,131.7
XS GIS Cut Line= 4
     1564301.777      339763.027     1564371.663      339686.163
     1564557.349      339578.904     1564648.444      339402.194
#Sta/Elev= 30
       0  804.03    18.9  797.62    28.3  794.01    37.8  789.38    94.4  754.54
   103.9  749.97   113.6  746.93   123.4  744.76   142.9  738.71   152.6  737.74
   162.4   737.6   172.1  737.64   191.6  738.14   201.4  738.78   220.8  740.54
   250.1  743.72   269.6  745.25   327.8   746.5   337.3  746.97   346.7  747.86
   356.2  749.26   365.7  751.15   394.1  757.85   403.5  760.41   450.9  774.91
   460.3  777.93   469.8  781.53   488.7  790.24   498.2  794.19   517.1  800.39
#Mann= 3 , 0 , 0
       0     .09       0   142.9    .045       0   172.1     .06       0
Bank Sta=142.9,172.1
XS Rating Curve= 0 ,0
Exp/Cntr=0.3,0.1

Type RM Length L Ch R = 1 ,33735.2 ,53.5,53.5,53.5
XS GIS Cut Line= 5
     1564357.757      339794.653     1564408.538      339799.861
     1564538.746      339751.684     1564658.538      339721.736
     1564799.163      339678.767
#Sta/Elev= 30
       0  782.61     8.5  777.09      17  771.83    25.5  766.76      34  761.84
    42.5  757.02      51  752.42    60.3  748.01    69.6  745.37    78.8  744.12
    88.1  742.13      90741.5931    97.3  739.53   106.6     738   115.8  738.23
   125.1  740.04   134.4  742.38   143.6  743.52   162.1  744.31   199.4  745.21
   237.4  746.36   284.9  747.33   303.9  747.93     333  748.98   362.4  749.88
   391.8  750.44   421.2  750.63   440.8  750.55   450.6  750.79   460.4  751.57
#Mann= 3 , 0 , 0
       0     .09       0      90    .045       0   134.4     .06       0
Bank Sta=90,134.4
XS Rating Curve= 0 ,0
Exp/Cntr=0.3,0.1

Type RM Length L Ch R = 1 ,33681.7 ,88,86.6,85.3
XS GIS Cut Line= 5
     1564385.101      339841.528     1564435.882      339846.736
      1564566.09      339798.559     1564685.882      339768.611
     1564826.507      339725.642
#Sta/Elev= 30
       0  761.98      17   753.1    25.5  748.92      34  745.88    42.5  744.63
    60.3   744.5    69.6  743.63    78.8  741.84      88739.6439    97.3  738.06
   106.6  737.91   115.8  739.05   125.1   741.2   134.4   742.9   143.6  743.63
   152.9  743.84   171.4  743.97   180.6  744.25   199.4   745.3   227.9  747.37
   237.4  747.95   256.4  748.83   284.9  749.68   303.9  749.97   352.6  749.97
   411.4  750.73     431  750.76   440.8  750.89   450.6  751.82   460.4  753.89
#Mann= 3 , 0 , 0
       0     .09       0      88    .045       0   125.1     .06       0
Bank Sta=88,125.1
XS Rating Curve= 0 ,0
Exp/Cntr=0.3,0.1

Type RM Length L Ch R = 1 ,33595.1 ,196.9,187,177.1
XS GIS Cut Line= 4
     1564451.507      340004.288     1564486.663      339922.257
     1564649.424      339850.642     1564859.059      339828.507
#Sta/Elev= 30
       0  785.83     8.9  780.86    35.7  765.28    44.6  760.29    53.6  755.68
    62.5  751.56    71.4   748.1    80.3  745.63    89.2  744.35    98.6  742.71
     108  739.95   117.3  738.03   126.7   737.5     136  737.64   145.4  738.21
   154.8  739.02   182.8  741.34   229.6  745.84     239  746.58   248.4  747.18
   267.1  747.97   295.8  748.44   343.7   748.4   372.5  748.48   410.8  748.82
   439.5  748.93   449.1  749.86   458.7  752.29   468.3  755.68   477.9   759.2
#Mann= 3 , 0 , 0
       0     .09       0     108    .045       0   154.8     .06       0
Bank Sta=108,154.8
XS Rating Curve= 0 ,0
Exp/Cntr=0.3,0.1

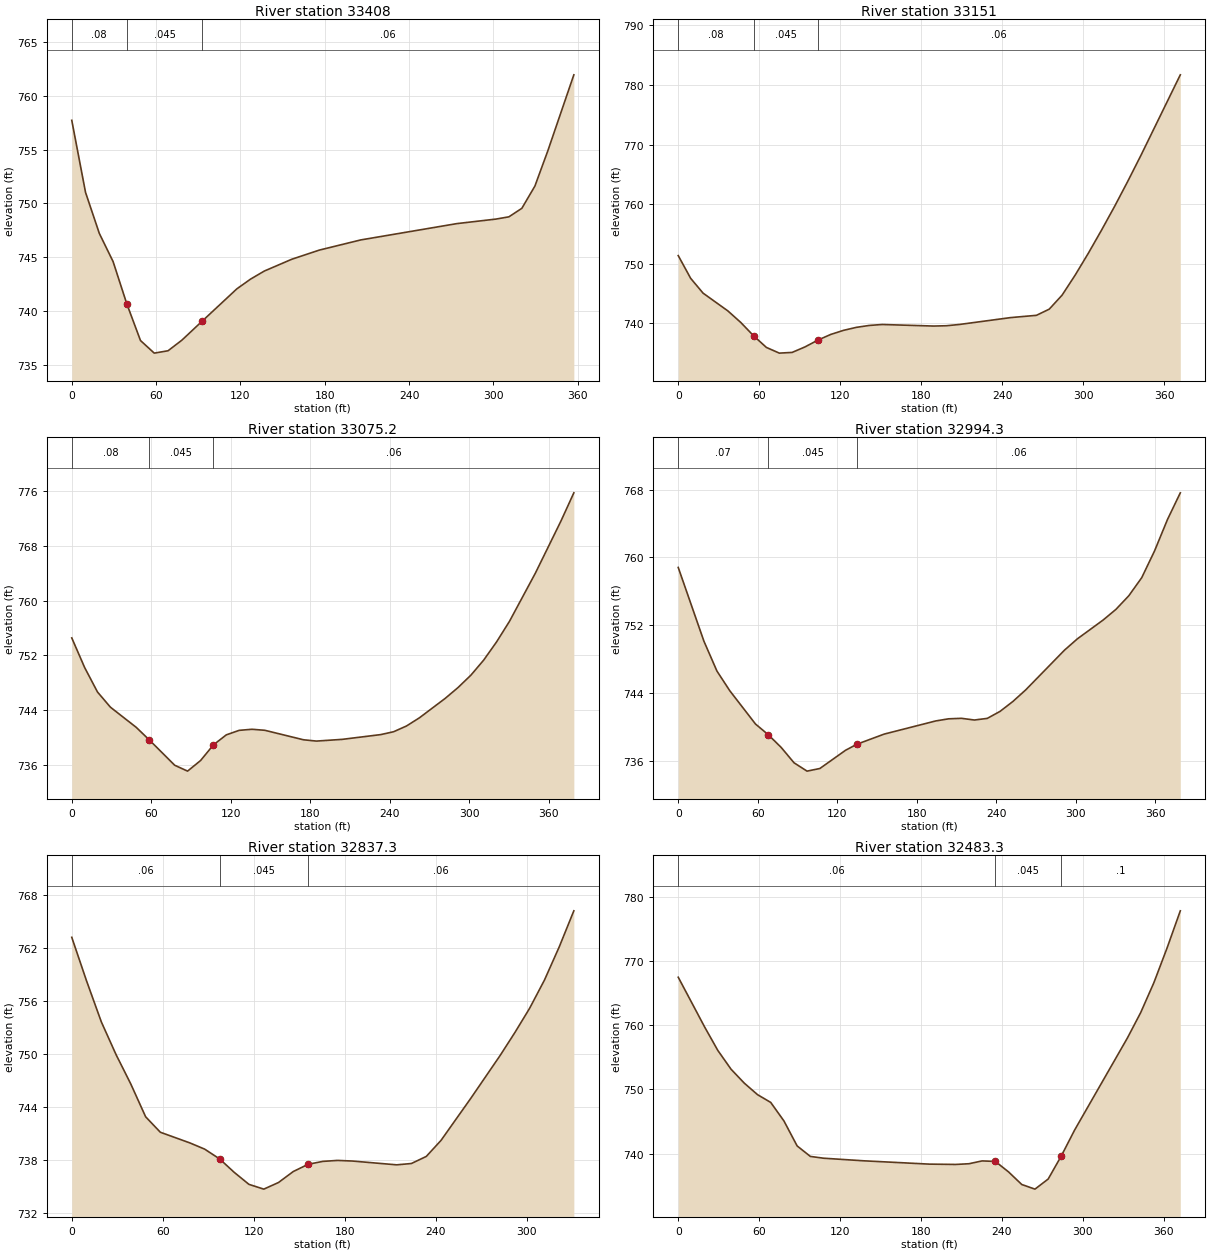
Type RM Length L Ch R = 1 ,33408   ,246,257.1,268.4
XS GIS Cut Line= 3
     1564616.871      340077.205     1564797.861      339871.475
     1564875.986       339842.83
#Sta/Elev= 23
       0  757.72     9.8  751.02    19.6  747.21    29.4  744.59    39.1  740.68
    48.9  737.25    58.7  736.08    68.5   736.3    78.3  737.28      93  739.08
   117.4  742.05   127.2  742.96     137  743.71   156.6  744.81   176.2  745.66
   205.5   746.6     274  748.12   301.8  748.54     311  748.75   320.2  749.54
   329.5  751.61   338.7  754.89   357.2  761.95
#Mann= 3 , 0 , 0
       0     .08       0    39.1    .045       0      93     .06       0
Bank Sta=39.1,93
XS Rating Curve= 0 ,0
Exp/Cntr=0.3,0.1

Type RM Length L Ch R = 1 ,33151   ,75.1,75.7,76.2
XS GIS Cut Line= 4
     1564767.913      340238.663     1564801.767       340224.34
     1565033.538        340137.1     1565092.132      340071.996
#Sta/Elev= 30
       0  751.34     9.2  747.52    18.4  745.03    36.8  742.04    46.3  740.11
    55.8  737.87    65.3  735.91    74.9  734.95    84.4  735.07    93.9  735.99
   103.4  737.13     113  738.09   122.5  738.78     132  739.28   141.5   739.6
   151.1  739.76   189.2   739.5   198.7  739.55   208.2  739.76   246.3  740.92
   265.4   741.3   274.9  742.34   284.4  744.69   294.1  748.06   303.9  751.75
   313.6   755.6   323.3   759.6   333.1  763.83   342.8  768.17     372  781.71
#Mann= 3 , 0 , 0
       0     .08       0    55.8    .045       0   103.4     .06       0
Bank Sta=55.8,103.4
XS Rating Curve= 0 ,0
Exp/Cntr=0.3,0.1

Type RM Length L Ch R = 1 ,33075.2 ,81,80.9,81
XS GIS Cut Line= 2
     1564805.674      340298.559     1565162.444      340170.955
#Sta/Elev= 30
       0  754.54     9.7  750.21    19.4  746.62    29.2  744.39    48.6  741.45
    58.3  739.64    77.7  735.89    87.4  735.03    97.2  736.58   106.9  738.87
   116.6  740.34   126.3     741     136  741.16   145.7  741.01   174.9  739.62
   184.6  739.43     204  739.68   233.2  740.38   242.9   740.8   252.6  741.64
   262.3  742.83   281.8  745.68   291.5  747.27   301.2  749.08   310.9   751.3
   320.6  753.96   330.3  756.96   349.8     764   369.2  771.67   378.9  775.79
#Mann= 3 , 0 , 0
       0     .08       0    58.3    .045       0   106.9     .06       0
Bank Sta=58.3,106.9
XS Rating Curve= 0 ,0
Exp/Cntr=0.3,0.1

Type RM Length L Ch R = 1 ,32994.3 ,157.8,157,156
XS GIS Cut Line= 2
     1564844.736      340364.965     1565201.507      340237.361
#Sta/Elev= 30
       0  758.82    19.4  750.13    29.2  746.62    38.9   744.3    58.3  740.38
      68  739.11    77.7  737.62    87.4  735.81    97.2  734.83   106.9  735.14
   126.3  737.29     135738.0076   155.4  739.19   194.3  740.74     204  740.99
   213.7  741.05   223.5  740.85   233.2  741.04   242.9  741.87   252.6  743.04
   262.3  744.41   291.5  749.08   301.2  750.41   320.6  752.62   330.3  753.88
     340  755.48   349.8  757.62   359.5  760.78   369.2  764.46   378.9  767.61
#Mann= 3 , 0 , 0
       0     .07       0      68    .045       0     135     .06       0
Bank Sta=68,135
XS Rating Curve= 0 ,0
Exp/Cntr=0.3,0.1

Type RM Length L Ch R = 1 ,32837.3 ,345.3,354,362.4
XS GIS Cut Line= 2
     1564930.674      340488.663     1565239.267      340368.871
#Sta/Elev= 30
       0   763.2     9.7  758.29    19.5  753.62    29.2  749.92    38.9   746.6
    48.7  742.88    58.4  741.13    77.9  739.92    87.6  739.22    97.4  738.12
   107.1  736.59   116.8  735.23   126.6  734.69   136.3  735.44     146  736.68
   155.8   737.5   165.5  737.83   175.2  737.94     185  737.87   214.2  737.44
   223.9  737.59   233.7  738.39   243.4   740.2   262.9  744.93   282.4  749.82
   292.1  752.41   301.8  755.15   311.6  758.35   321.3  762.09     331   766.2
#Mann= 3 , 0 , 0
       0     .06       0    97.4    .045       0   155.8     .06       0
Bank Sta=97.4,155.8
XS Rating Curve= 0 ,0
Exp/Cntr=0.3,0.1

Type RM Length L Ch R = 1 ,32483.3 ,350.1,366.4,382.4
XS GIS Cut Line= 2
     1564955.413      340715.225     1565327.809      340715.225
#Sta/Elev= 28
       0  767.45    19.6   759.7    29.4  756.05    39.2  753.13      49  750.97
    58.8  749.18    68.6  747.97    78.4  745.09    88.2   741.2      98  739.57
   107.8  739.29   137.2  738.89   186.2  738.37   205.8  738.32   215.6  738.43
   225.4  738.87   235.2  738.79     245  737.16   254.8   735.2   264.6  734.48
   274.4  736.05   284.2  739.67     294  743.67   333.2  758.01     343  761.94
   352.8   766.6   362.6  772.01   372.4  777.78
#Mann= 3 , 0 , 0
       0     .06       0   235.2    .045       0   284.2      .1       0
Bank Sta=235.2,284.2
XS Rating Curve= 0 ,0
Exp/Cntr=0.3,0.1

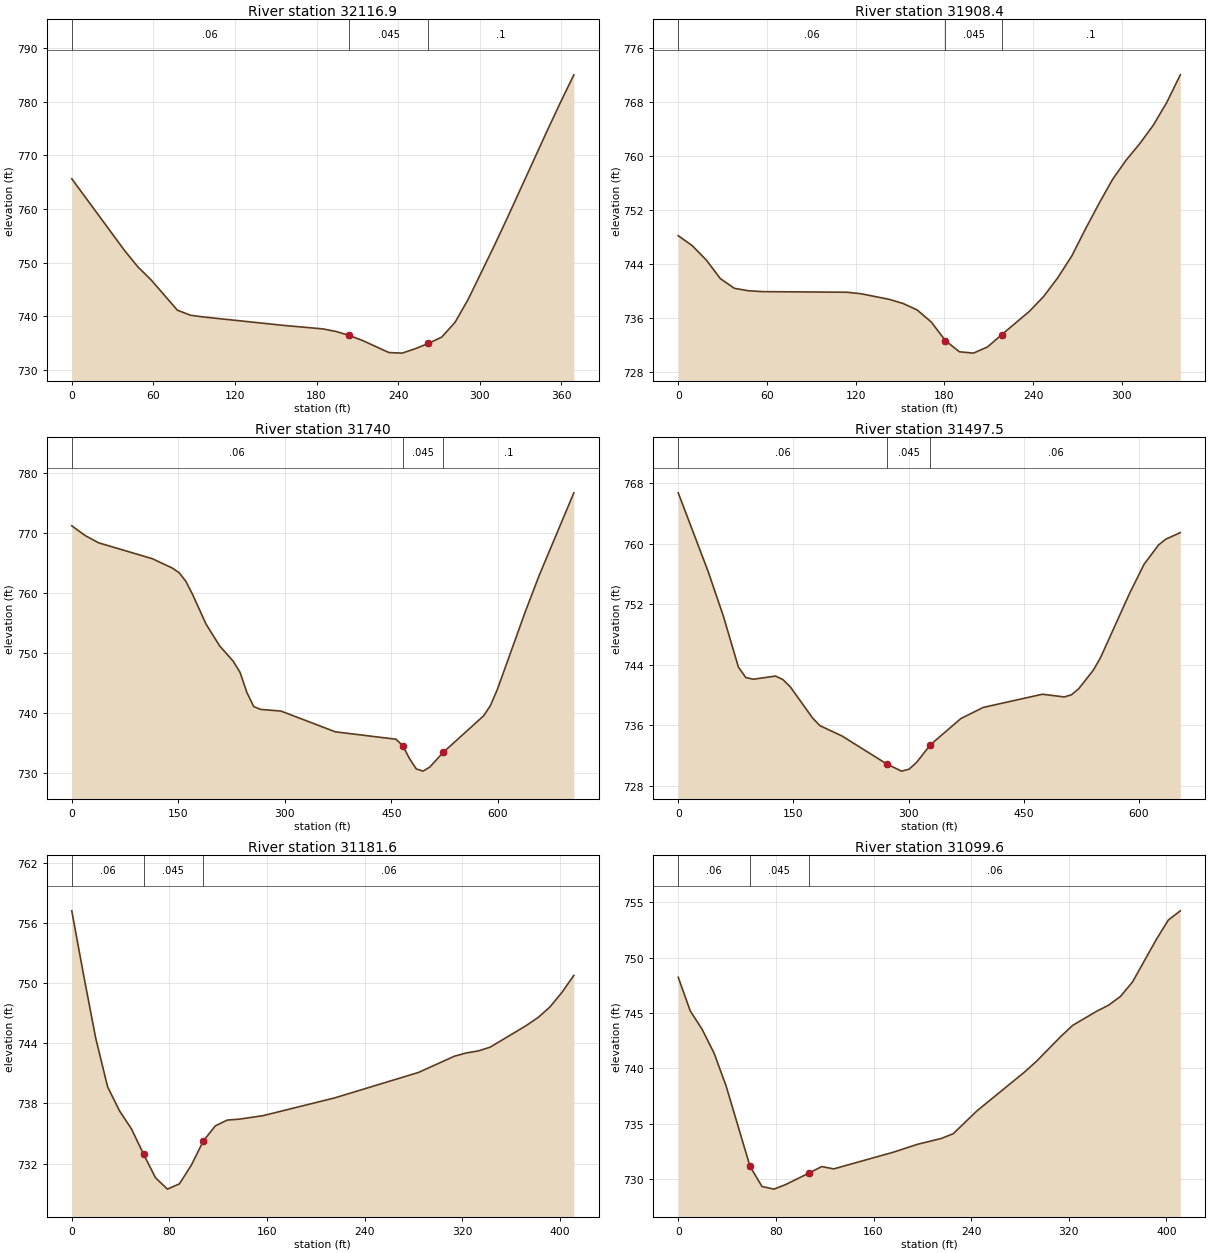
Type RM Length L Ch R = 1 ,32116.9 ,208.7,208.5,208.1
XS GIS Cut Line= 2
     1564908.538      340881.892     1565187.184       341124.08
#Sta/Elev= 24
       0  765.66    38.9  752.25    48.6  749.23    58.3  746.81    77.7  741.14
    87.4   740.2    97.2  739.87   155.4  738.32   184.6  737.66   194.3  737.18
   203.7736.4629   213.7  735.51   233.2  733.25   242.9  733.14   252.6  733.96
   262.3  734.96     272  736.12   281.8  738.87   291.5  743.17   310.9  753.28
   320.6  758.54   349.8  774.73   359.5  779.97   369.2  785.04
#Mann= 3 , 0 , 0
       0     .06       0   203.7    .045       0   262.3      .1       0
Bank Sta=203.7,262.3
XS Rating Curve= 0 ,0
Exp/Cntr=0.3,0.1

Type RM Length L Ch R = 1 ,31908.4 ,178.9,168.4,157.6
XS GIS Cut Line= 3
      1564809.58      341073.298     1565014.007      341243.871
     1565079.111      341277.725
#Sta/Elev= 30
       0  748.19     9.5   746.7      19  744.57    28.5  741.81      38  740.37
    47.5  740.01      57  739.88   114.1  739.79   123.6  739.57   142.6  738.74
   152.1  738.12   161.6  737.16   171.2  735.36   180.7  732.61   190.2  730.95
   199.7  730.75   209.2  731.67   218.7  733.47   237.7  736.99   247.2  739.17
   256.7  741.94   266.2  745.18   275.4  749.16   284.6  752.96   293.8  756.55
   302.9  759.39   312.1  761.83   321.3  764.58   330.4  767.95   339.6  772.07
#Mann= 3 , 0 , 0
       0     .06       0   180.7    .045       0   218.7      .1       0
Bank Sta=180.7,218.7
XS Rating Curve= 0 ,0
Exp/Cntr=0.3,0.1

Type RM Length L Ch R = 1 ,31740   ,247.1,242.6,238.2
XS GIS Cut Line= 5
     1564450.205      341237.361     1564648.121      341223.038
     1564745.778      341315.486     1564994.476      341377.986
     1565106.455       341342.83
#Sta/Elev= 30
       0  771.17    18.9  769.54    37.8  768.33   113.4  765.68   141.7  764.11
   151.2  763.33   160.6  761.91   170.1   759.7     189  754.77     208  751.16
   227.2  748.58   236.9  746.71   246.5  743.36   256.1  741.01   265.7  740.54
   294.5  740.26   370.9   736.8   456.4  735.56   465.9  734.49   475.4  732.32
   484.9  730.61   494.4  730.24   503.9  730.91   522.7733.3539   579.8  739.48
   589.3  741.18   599.1  743.89   638.2  756.78   657.8  762.86   706.7  776.67
#Mann= 3 , 0 , 0
       0     .06       0   465.9    .045       0   522.7      .1       0
Bank Sta=465.9,522.7
XS Rating Curve= 0 ,0
Exp/Cntr=0.3,0.1

Type RM Length L Ch R = 1 ,31497.5 ,342.2,315.9,288.5
XS GIS Cut Line= 4
     1564620.778      341652.725     1564662.444      341586.319
     1565058.278      341577.205     1565188.486      341453.507
#Sta/Elev= 30
       0  766.73    39.2  756.26    58.8  750.42    78.4  743.68      88  742.31
    97.7  742.08   126.7   742.5   136.3  742.04     146  741.07     175  736.95
   184.6  735.94   213.6  734.56   271.5  730.88   290.8  729.93   300.5  730.18
   310.2  731.06   328.5733.4242   368.1  736.88   397.1  738.35   474.3   740.1
   502.7  739.74   512.1  740.02   521.6  740.83   540.5  743.26     550  744.94
   587.8  753.43   606.7  757.28   625.6  759.84     635   760.6   653.9  761.47
#Mann= 3 , 0 , 0
       0     .06       0   271.5    .045       0   328.5     .06       0
Bank Sta=271.5,328.5
XS Rating Curve= 0 ,0
Exp/Cntr=0.3,0.1

Type RM Length L Ch R = 1 ,31181.6 ,82.1,82,81.9
XS GIS Cut Line= 2
     1564986.663       341905.33     1565155.934       341530.33
#Sta/Elev= 27
       0  757.25     9.8  750.77    19.6  744.54    29.4  739.65    39.2  737.25
      49  735.44    58.8  732.94    68.6  730.58    78.4  729.44    88.2  729.97
      98  731.84   107.8  734.25   117.6  735.76   127.4  736.34   137.1  736.43
   156.7  736.78   215.5  738.56   284.1   741.1   313.5  742.72   323.3  743.05
   333.1  743.25   342.9  743.63   372.2  745.77     382  746.58   391.8  747.64
   401.6  749.09   411.4   750.8
#Mann= 3 , 0 , 0
       0     .06       0    58.8    .045       0   107.8     .06       0
Bank Sta=58.8,107.8
XS Rating Curve= 0 ,0
Exp/Cntr=0.3,0.1

Type RM Length L Ch R = 1 ,31099.6 ,225.3,233.3,241.2
XS GIS Cut Line= 2
     1565062.184       341936.58     1565231.455       341561.58
#Sta/Elev= 28
       0  748.23     9.8   745.2    19.6  743.52    29.4  741.36    39.2  738.41
    58.8  731.14    68.6  729.31    78.4  729.07    88.2  729.49   106.8730.5079
   117.6  731.11   127.4   730.9   176.3  732.41   195.9  733.12   215.5  733.65
   225.3  734.08   244.9  736.16   284.1  739.69   293.9  740.67   313.5  742.88
   323.3  743.89   342.9  745.16   352.7  745.71   362.4   746.5   372.2   747.8
   391.8  751.66   401.6  753.41   411.4  754.24
#Mann= 3 , 0 , 0
       0     .06       0    58.8    .045       0   106.8     .06       0
Bank Sta=58.8,106.8
XS Rating Curve= 0 ,0
Exp/Cntr=0.3,0.1