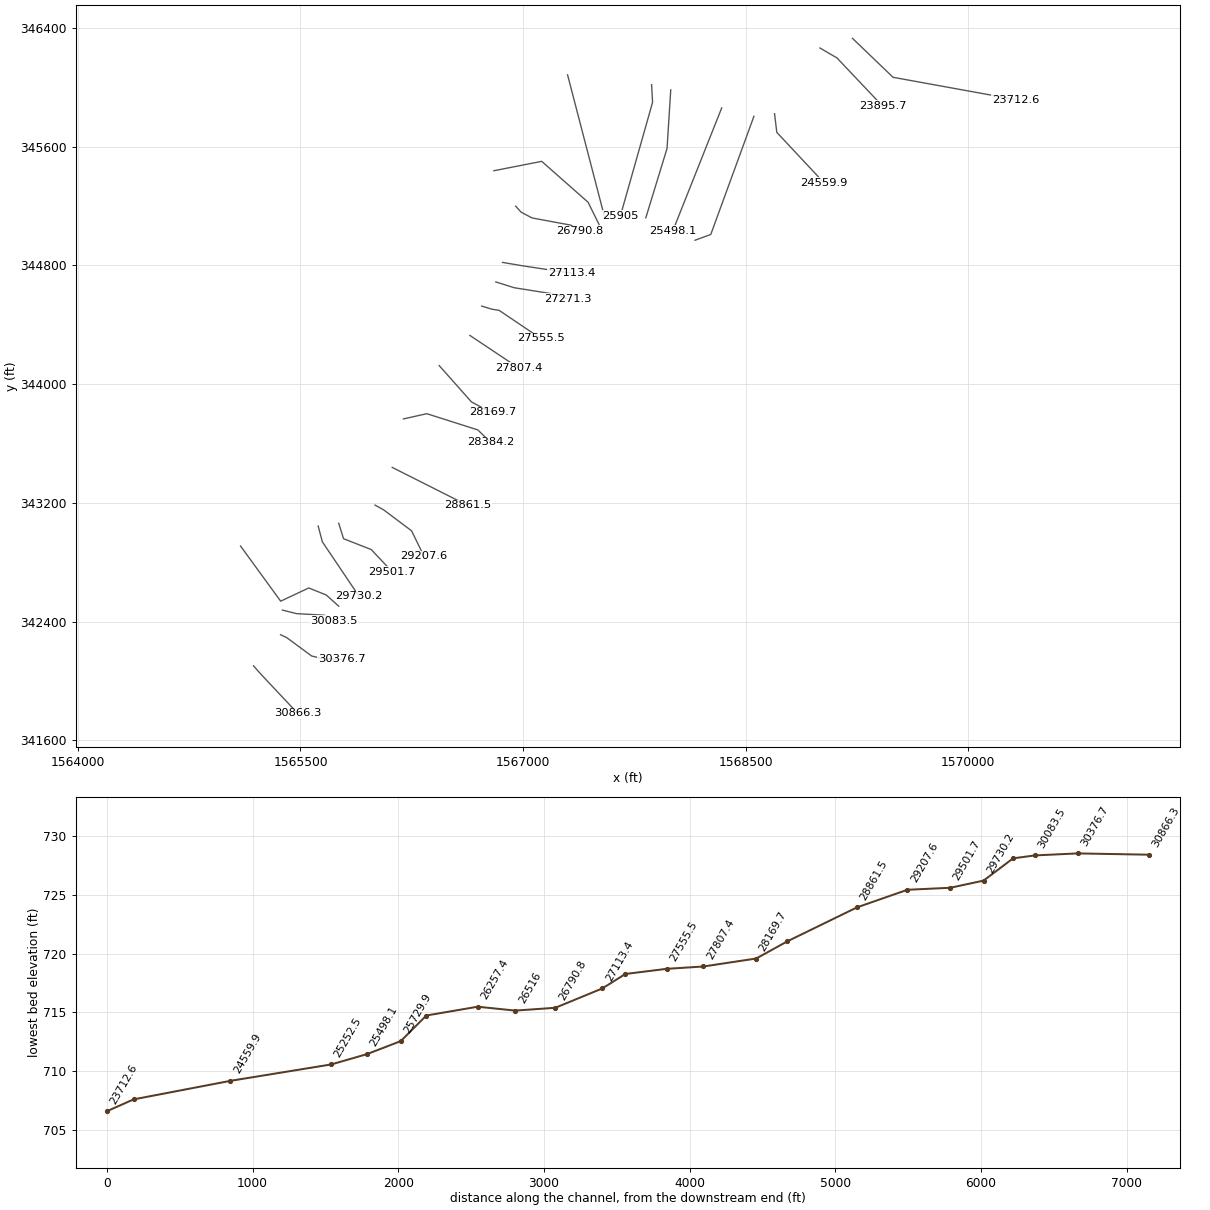
HEC-RAS study SNCHOCRK.prj: SNCHOCRK

--- SNCHOCRK.g01 (geometry) --- (continued)

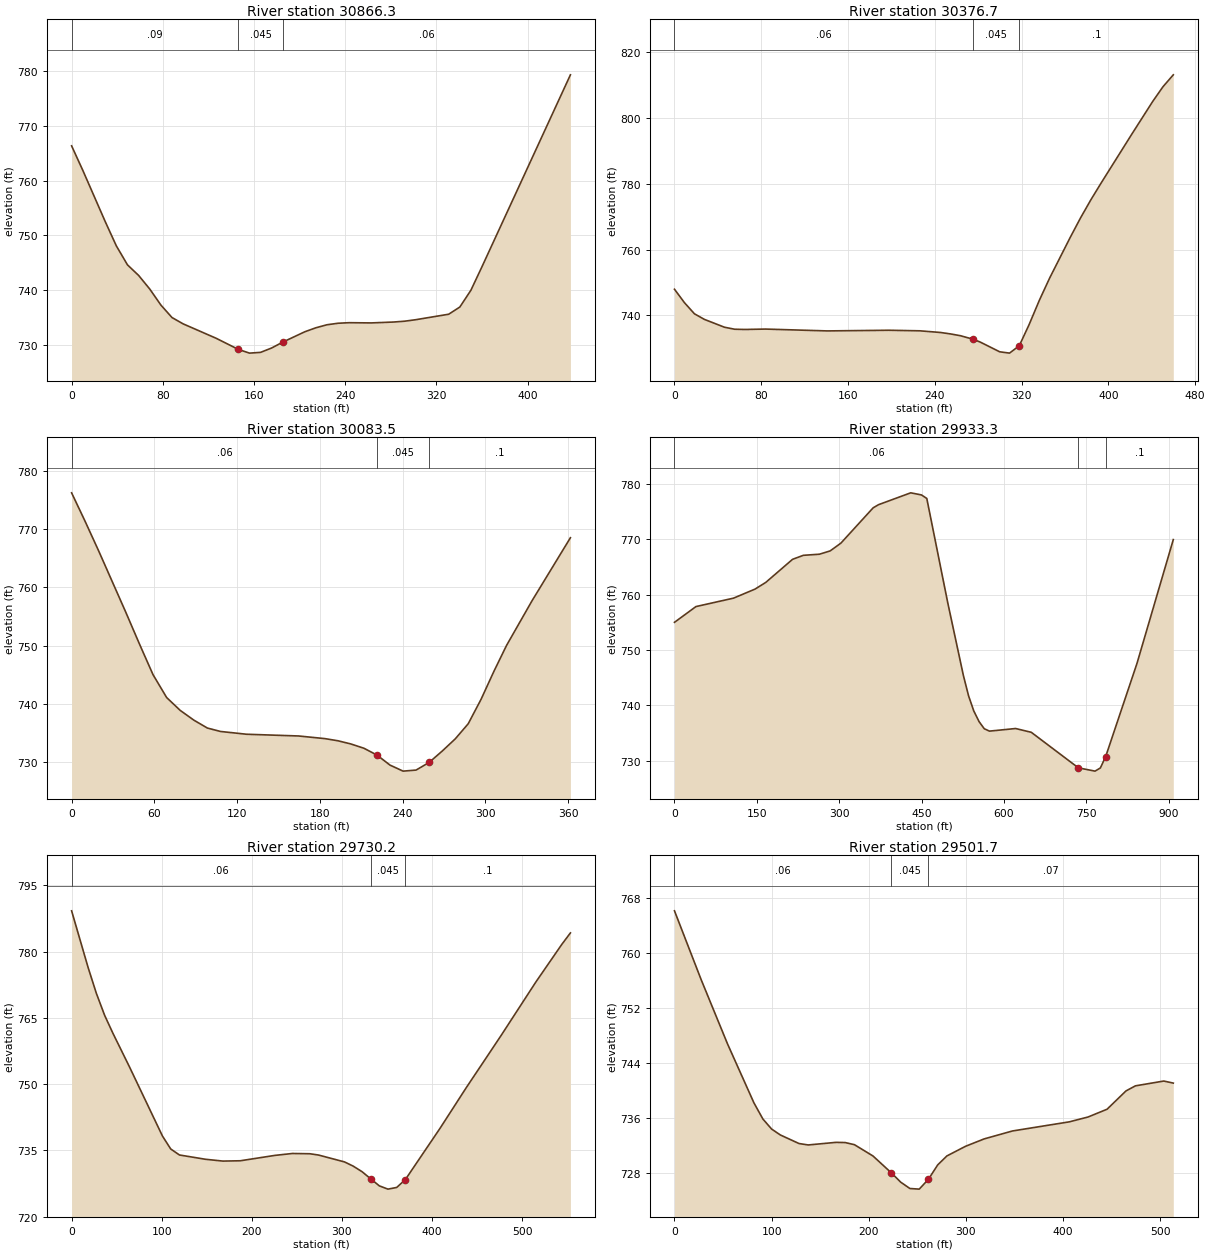
Type RM Length L Ch R = 1 ,30866.3 ,477.8,489.6,501.8
XS GIS Cut Line= 3
     1565183.278      342101.944     1565235.361       342043.35
     1565481.455      341781.632
#Sta/Elev= 30
       0  766.38     9.8  761.91    29.4  752.56    39.2  748.09      49   744.6
    58.8  742.66    68.6  740.16    78.4  737.22    88.1  734.95    97.8   733.8
   126.9  731.15   146.4  729.11   156.1  728.44   165.8  728.58   175.5  729.38
   185.2  730.45   204.6  732.35   214.3  733.08     224  733.63   233.8  733.91
   243.5  734.01   262.9  733.97   282.3  734.13     292  734.28   301.7  734.55
   330.8  735.56   340.6  736.88   350.3  739.95     360  744.25   437.6  779.38
#Mann= 3 , 0 , 0
       0     .09       0   146.4    .045       0   185.2     .06       0
Bank Sta=146.4,185.2
XS Rating Curve= 0 ,0
Exp/Cntr=0.3,0.1

Type RM Length L Ch R = 1 ,30376.7 ,289.2,293.2,296.2
XS GIS Cut Line= 5
     1565365.569       342311.58     1565407.236      342292.048
     1565575.205       342168.35     1565645.517      342151.423
      1565778.33      342144.913
#Sta/Elev= 30
       0  747.97     9.2  743.88    18.4   740.5    27.6   738.8      46  736.43
    55.5  735.81      65  735.74    83.9  735.86   140.8   735.3   197.7   735.5
   226.2  735.33   245.1  734.83   254.6  734.38   263.7  733.84     275732.8035
   281.7  731.94   299.8  728.96   308.9  728.55   317.9   730.8   326.9  737.17
   336.4   744.6   345.9  751.37   364.9  763.74   374.4  769.66   383.9  775.15
   393.4  780.27   421.9  795.23   440.9  805.03   450.4  809.52   459.9  813.13
#Mann= 3 , 0 , 0
       0     .06       0     275    .045       0   317.9      .1       0
Bank Sta=275,317.9
XS Rating Curve= 0 ,0
Exp/Cntr=0.3,0.1

Type RM Length L Ch R = 1 ,30083.5 ,157.4,150.2,143
XS GIS Cut Line= 4
     1565378.142      342477.682     1565473.628       342453.81
      1565662.43       342442.96     1565725.364      342403.897
#Sta/Elev= 30
       0  776.29     9.8  771.38    19.7  766.25    39.4  755.67    49.2  750.26
      59     745    68.9  741.05    78.7  738.84    88.6  737.16    98.4   735.8
   107.9  735.21   126.8  734.73   164.6  734.43   183.5  733.98     193  733.61
   202.4  733.06   211.9  732.32   221.4  731.14   230.8  729.42   240.3  728.38
   249.7  728.56   259.2  729.88   268.6  731.82   278.1  733.93   287.5  736.53
   296.8  740.73   306.1  745.54   315.3  750.02   333.8  757.72   361.6  768.56
#Mann= 3 , 0 , 0
       0     .06       0   221.4    .045       0   259.2      .1       0
Bank Sta=221.4,259.2
XS Rating Curve= 0 ,0
Exp/Cntr=0.3,0.1

Type RM Length L Ch R = 1 ,29933.3 ,216.4,203.1,189.4
XS GIS Cut Line= 5
     1565096.038      342909.236     1565366.366      342537.748
     1565555.674      342626.684     1565672.861      342579.809
     1565757.496      342504.288
#Sta/Elev= 30
       0  754.99    39.1  757.83   107.5  759.35   146.6  760.98   166.2  762.19
     215  766.36   234.6  767.08   263.9  767.28   283.5  767.88     303  769.28
   361.7  775.65   371.5  776.22   430.1  778.36   449.7  777.98   459.4  777.34
   497.5  758.54     526   745.4   535.5   741.7     545  738.98   554.5  737.08
     564  735.78   573.5  735.35   621.1  735.82   649.6  735.14   735.4728.7212
   765.7  728.13   775.4   728.7   785.1  730.76   842.1  747.58   908.2  769.92
#Mann= 3 , 0 , 0
       0     .06       0   735.4    .045       0   785.1      .1       0
Bank Sta=735.4,785.1
XS Rating Curve= 0 ,0
Exp/Cntr=0.3,0.1

Type RM Length L Ch R = 1 ,29730.2 ,214.6,228.5,242.1
XS GIS Cut Line= 3
     1565619.027      343044.088     1565647.239      342937.751
     1565895.083      342569.826
#Sta/Elev= 30
       0  789.24    18.3  776.42    27.5  770.54    36.7  765.56    45.8  761.54
    64.2  753.92   100.8  738.26     110  735.32   119.7  733.96   148.6  732.99
   167.9  732.58   187.2  732.65   225.7  733.87     245   734.3   264.3  734.24
     274  733.95   302.9  732.39   312.5  731.44   322.2   730.2   331.8  728.59
   341.5  726.97   351.1  726.23   360.8  726.61   370.4  728.39     409  740.03
   437.9  749.17   476.5  760.96   515.1  773.08     544  781.63   553.6  784.24
#Mann= 3 , 0 , 0
       0     .06       0   331.8    .045       0   370.4      .1       0
Bank Sta=331.8,370.4
XS Rating Curve= 0 ,0
Exp/Cntr=0.3,0.1

Type RM Length L Ch R = 1 ,29501.7 ,299.5,294.1,288.3
XS GIS Cut Line= 4
     1565757.496      343062.882     1565790.049      342958.715
     1565976.246      342885.798     1566116.871      342737.361
#Sta/Elev= 30
       0   766.2    27.3  756.22    54.6   746.8    81.8   738.2      91  735.85
     100  734.38   109.1  733.51   128.2  732.27   137.7  732.06   166.3  732.44
   175.8  732.41   185.3   732.1   204.4  730.45   223.4  727.98   232.9  726.64
   242.4  725.71     252  725.62   261.5  727.06     271  729.15   280.5  730.46
   299.6  731.86   318.8  732.94     348   734.1   406.5  735.43   425.9  736.14
   445.4  737.27   464.9  739.94   474.6  740.68   503.8  741.38   513.6  741.08
#Mann= 3 , 0 , 0
       0     .06       0   223.4    .045       0   261.5     .07       0
Bank Sta=223.4,261.5
XS Rating Curve= 0 ,0
Exp/Cntr=0.3,0.1

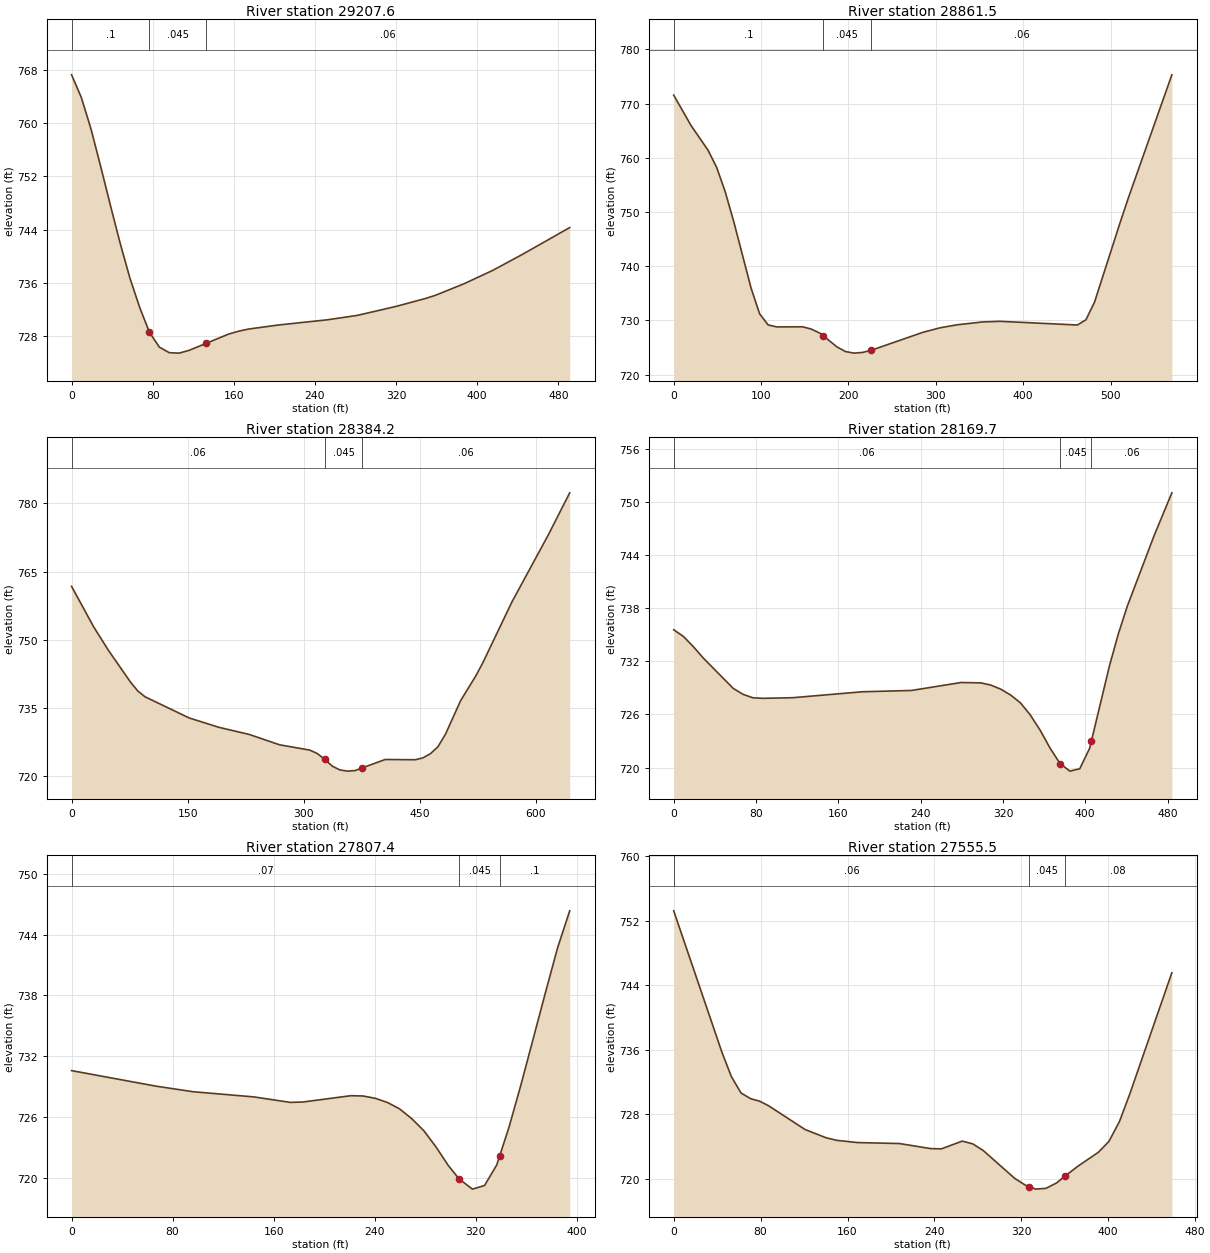
Type RM Length L Ch R = 1 ,29207.6 ,343.7,346.1,348.4
XS GIS Cut Line= 4
     1566002.288      343185.278     1566060.882      343152.725
     1566248.382        343012.1     1566331.715      342841.528
#Sta/Elev= 27
       0  767.23     9.6  763.84    19.2  759.08    28.7  753.47    38.3  747.63
    47.9  741.96    57.4  736.78      67  732.38    76.8  728.57    86.6  726.35
    96.3  725.52   106.1  725.45   115.9  725.87   132.9726.9293   154.9  728.31
   164.7  728.74   174.4  729.06   203.8  729.67   252.6  730.46   281.9  731.12
   320.4  732.48   348.9  733.65   358.4  734.11   386.8  735.85   415.3  737.87
   443.8  740.21   491.2   744.3
#Mann= 3 , 0 , 0
       0      .1       0    76.8    .045       0   132.9     .06       0
Bank Sta=76.8,132.9
XS Rating Curve= 0 ,0
Exp/Cntr=0.3,0.1

Type RM Length L Ch R = 1 ,28861.5 ,466.8,477.3,491.5
XS GIS Cut Line= 2
     1566118.174      343439.184     1566627.288      343182.673
#Sta/Elev= 30
       0  771.57    19.7     766    39.3   761.4    49.2  758.22      59   753.7
    68.8  748.17    88.5  735.98    98.3  731.21   108.1  729.15     118  728.79
   147.4  728.81   157.3   728.4   167.1  727.65   171.3727.1357   186.8   725.1
   196.6  724.24   206.4  723.95   216.2  724.08   226.1  724.48     285  727.78
   304.7  728.62   324.4  729.18   353.8  729.71   373.5  729.82     462  729.14
   471.8  730.11   481.6  733.36   511.1  748.16   520.9  752.87   570.1  775.32
#Mann= 3 , 0 , 0
       0      .1       0   171.3    .045       0   226.1     .06       0
Bank Sta=171.3,226.1
XS Rating Curve= 0 ,0
Exp/Cntr=0.3,0.1

Type RM Length L Ch R = 1 ,28384.2 ,223.7,214.5,200.4
XS GIS Cut Line= 4
     1566193.694      343766.007     1566351.246      343801.163
     1566694.996      343691.788     1566782.236      343607.153
#Sta/Elev= 30
       0  761.73    28.5  752.84    47.5  747.68      76   740.7    85.5  738.72
      95  737.42   151.9  732.77   190.7  730.69   229.7  729.13   268.7  726.86
   307.7  725.69   317.4  724.95   327.2  723.64   336.9  722.16   346.7  721.32
   356.4  721.06   366.2  721.18   375.9  721.79   405.2  723.62   444.2  723.57
   453.9  723.97   463.7   724.9   473.4  726.42   483.2   729.2   502.7  736.57
   522.2  741.98   531.5  744.94   568.9  758.27   615.7  772.96   643.7  782.33
#Mann= 3 , 0 , 0
       0     .06       0   327.2    .045       0   375.9     .06       0
Bank Sta=327.2,375.9
XS Rating Curve= 0 ,0
Exp/Cntr=0.3,0.1

Type RM Length L Ch R = 1 ,28169.7 ,364.1,362.3,359.9
XS GIS Cut Line= 4
      1566434.58      344125.382     1566652.028       343880.59
     1566736.663      343835.017     1566792.653       343811.58
#Sta/Elev= 30
       0  735.59     9.6  734.82    19.3  733.65    28.9  732.37    57.8  728.96
    67.4  728.28      77  727.89    86.7  727.83   115.6   727.9     183  728.57
   231.1  728.72   279.3  729.62   298.5  729.58   308.2  729.33   317.8  728.87
   327.4  728.21     337  727.32   346.6  725.95   356.3   724.2   365.9  722.18
   375.5  720.45   385.1  719.59   394.7  719.86   404.3  722.18     406722.9963
   423.6  731.53   432.2  735.13   440.9  738.26   466.9  746.23   484.2  751.09
#Mann= 3 , 0 , 0
       0     .06       0   375.5    .045       0     406     .06       0
Bank Sta=375.5,406
XS Rating Curve= 0 ,0
Exp/Cntr=0.3,0.1

Type RM Length L Ch R = 1 ,27807.4 ,251.8,251.9,251.7
XS GIS Cut Line= 2
     1566641.611      344328.507     1566969.736      344109.757
#Sta/Elev= 25
       0  730.59    67.3  729.05    96.2  728.51   144.3     728   173.1  727.46
   182.8  727.49   221.2  728.12   230.8  728.09   240.5  727.86   250.1  727.45
   259.7  726.82   269.3  725.86   278.9  724.67   288.6  723.06   298.2  721.25
     307719.8934   317.4  718.91     327  719.27   336.6  721.29     339722.2079
   346.3     725   355.9  729.24   375.1  738.24   384.7  742.65   394.4  746.34
#Mann= 3 , 0 , 0
       0     .07       0     307    .045       0     339      .1       0
Bank Sta=307,339
XS Rating Curve= 0 ,0
Exp/Cntr=0.3,0.1

Type RM Length L Ch R = 1 ,27555.5 ,274.2,284.2,294
XS GIS Cut Line= 4
     1566721.038      344526.423     1566788.746       344505.59
     1566838.226      344497.778     1567118.174      344308.975
#Sta/Elev= 30
       0   753.2    44.3  735.71    53.1  732.65      62  730.62    70.8  729.92
    79.2   729.6    87.5  729.03   120.9   726.1   140.2  725.08   149.9  724.76
   169.2  724.48   207.8  724.36   236.7  723.73   246.4   723.7   265.6  724.66
   275.3  724.32   284.9   723.5   313.9  720.05   323.5  719.22     327719.0347
   333.2  718.71   342.8  718.81   352.5  719.48     360720.2925   371.8  721.52
   391.1  723.29   400.7  724.63   410.4   727.1     420  730.55   458.6  745.53
#Mann= 3 , 0 , 0
       0     .06       0     327    .045       0     360     .08       0
Bank Sta=327,360
XS Rating Curve= 0 ,0
Exp/Cntr=0.3,0.1

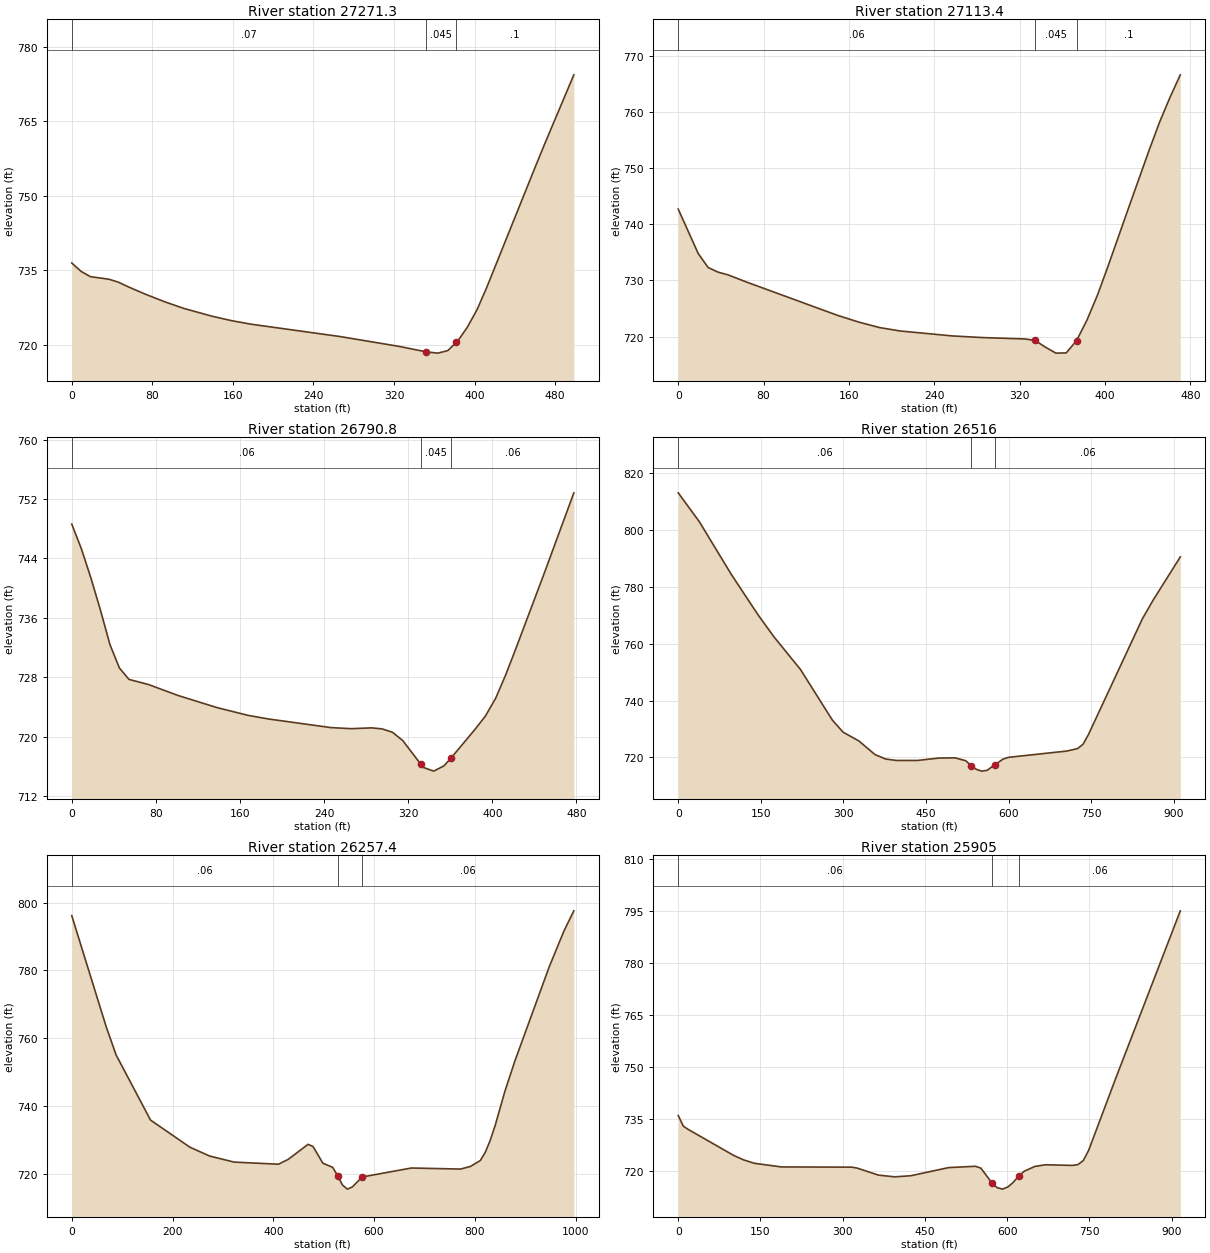
Type RM Length L Ch R = 1 ,27271.3 ,157.8,157.9,158
XS GIS Cut Line= 4
      1566816.09      344689.184     1566939.788      344650.121
     1567209.319      344607.153     1567300.465      344577.205
#Sta/Elev= 25
       0  736.44     9.3  734.74    18.5  733.69    37.1  733.16    46.3  732.57
    55.6  731.68    74.1  730.07    92.7  728.59   111.2  727.29   139.5   725.7
     159   724.8   178.5  724.09   266.2  721.62   324.7  719.64     352718.5262
   363.7  718.27   373.4  718.78     382720.4467   383.2  720.68   392.9  723.51
   402.6  727.09   412.2  731.56   460.2  755.77   469.8  760.52   498.6  774.38
#Mann= 3 , 0 , 0
       0     .07       0     352    .045       0     382      .1       0
Bank Sta=352,382
XS Rating Curve= 0 ,0
Exp/Cntr=0.3,0.1

Type RM Length L Ch R = 1 ,27113.4 ,323.4,322.7,321.9
XS GIS Cut Line= 3
     1566861.663      344820.694     1566999.684      344797.257
     1567326.507      344747.778
#Sta/Elev= 26
       0  742.73    18.7  734.82      28  732.32    37.3  731.49    46.7     731
    65.3  729.63   149.7  723.75   169.2  722.58   188.6   721.6     208  720.99
   256.7  720.11   285.8  719.81   324.7  719.57   334.4  719.31   344.2  718.09
   353.9  717.04   363.6  717.08   373.3  719.28     383  722.92   392.8  727.36
   402.5   732.4   421.9  742.88   441.4  753.31   451.1  758.26   460.8  762.65
   470.5  766.69
#Mann= 3 , 0 , 0
       0     .06       0   334.4    .045       0   373.3      .1       0
Bank Sta=334.4,373.3
XS Rating Curve= 0 ,0
Exp/Cntr=0.3,0.1

Type RM Length L Ch R = 1 ,26790.8 ,286.9,274.8,261
XS GIS Cut Line= 5
     1566950.205        345199.6     1566986.663      345159.236
     1567060.882      345120.173     1567321.299      345071.996
     1567383.799      345031.632
#Sta/Elev= 30
       0  748.62     9.1  745.32    18.1  741.42    27.2  737.09    36.3  732.42
    45.3  729.27    54.4  727.73      73  727.04     101  725.57   138.3  723.93
   167.7  722.89   187.3   722.4   246.2  721.25   265.8   721.1   285.4  721.21
   295.2  721.07     305  720.62   314.8   719.5     332716.3137   334.4  715.89
   344.2  715.39     354   716.1     361 717.196   383.5  721.01   393.3  722.78
   403.1  725.18   412.4  728.24   421.7  731.63   449.6   742.1   477.5  752.83
#Mann= 3 , 0 , 0
       0     .06       0     332    .045       0     361     .06       0
Bank Sta=332,361
XS Rating Curve= 0 ,0
Exp/Cntr=0.3,0.1

Type RM Length L Ch R = 1 ,26516   ,272.2,258.7,246.6
XS GIS Cut Line= 4
     1566803.344      345438.475     1567125.552      345501.684
     1567438.052      345226.076     1567511.837      345076.337
#Sta/Elev= 30
       0  813.17    38.6  802.92    96.6  784.38   144.9  770.22   173.8  762.47
   222.1  750.94   280.1  733.09   299.4  728.88   328.4  725.74   357.4  720.98
   376.8  719.41   396.2  718.91   434.9  718.92   473.7  719.75   502.8  719.83
   522.2  718.82     532717.1019   541.5  715.77   551.2  715.15   560.9  715.42
     575717.3668     590  719.38   599.7     720   706.3  722.23   725.6   723.1
   735.3  724.62     745  727.98   843.2  768.84   862.9  775.45     912  790.61
#Mann= 3 , 0 , 0
       0     .06       0     532    .045       0     575     .06       0
Bank Sta=532,575
XS Rating Curve= 0 ,0
Exp/Cntr=0.3,0.1

Type RM Length L Ch R = 1 ,26257.4 ,362.5,352.4,340
XS GIS Cut Line= 2
     1567299.872      346084.308     1567550.899      345119.739
#Sta/Elev= 30
       0  796.15    68.4  763.36    87.9  755.11   156.3  735.86   234.5  727.85
   273.6  725.24   322.5  723.45   410.4  722.83     430  724.29     469  728.69
   478.8  728.08   498.4  723.14   517.9  721.91   527.7  719.48   537.4  716.68
   547.2  715.48     557  716.13   576.5  719.06   674.2  721.71     772   721.4
   791.5  722.18     811  723.91   820.8  726.31   830.6  729.85   840.4   734.2
   859.9  744.38   879.4  753.18   947.8  781.05   977.2  791.68   996.7  797.58
#Mann= 3 , 0 , 0
       0     .06       0   527.7    .045       0   576.5     .06       0
Bank Sta=527.7,576.5
XS Rating Curve= 0 ,0
Exp/Cntr=0.3,0.1

Type RM Length L Ch R = 1 ,25905   ,176.8,175.1,174.6
XS GIS Cut Line= 3
     1567866.003      346018.611     1567872.514      345899.253
       1567655.5      345133.194
#Sta/Elev= 30
       0  735.99     9.2  732.94    18.4  731.96   101.2  724.46   119.5  723.16
   139.2  722.18   188.3  721.14   316.1  721.08     326  720.82   365.3  718.77
   394.8  718.28   424.3   718.6   493.1  720.95   542.2  721.33     552  720.79
   571.7  716.61   581.5  715.16   591.4  714.73   601.2  715.35     611   716.7
   620.8  718.44   630.7  719.87   650.3  721.28     670  721.77   719.2  721.58
     729  721.82   738.8  722.99   748.6  725.97   797.8  746.69   915.7  795.13
#Mann= 3 , 0 , 0
       0     .06       0   571.7    .045       0   620.8     .06       0
Bank Sta=571.7,620.8
XS Rating Curve= 0 ,0
Exp/Cntr=0.3,0.1

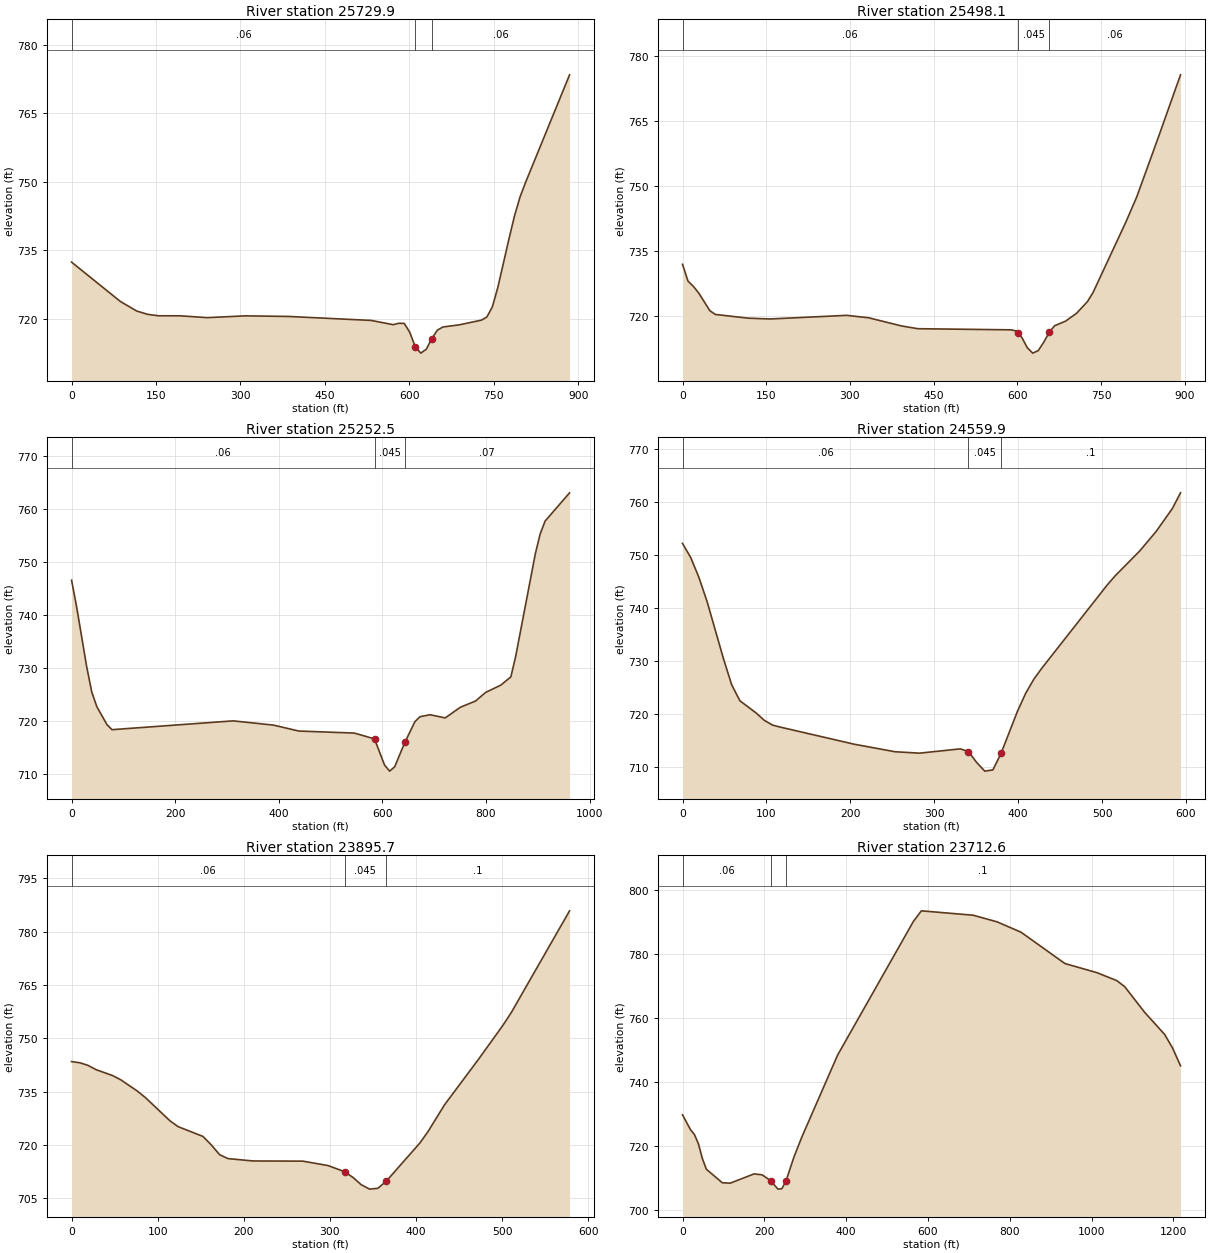
Type RM Length L Ch R = 1 ,25729.9 ,233.1,231.8,229.3
XS GIS Cut Line= 3
     1567995.096      345983.608      1567970.21      345589.157
     1567827.041      345121.108
#Sta/Elev= 30
       0  732.45    86.8  723.84   115.7  721.76     135  721.04   154.2  720.72
   192.8  720.71     241  720.31   308.5   720.7   385.6  720.57   532.3   719.7
   571.4  718.77   581.2  719.08     591  719.05   600.8  717.12   610.6  713.93
   620.4  712.55   630.2  713.41     640  715.73   649.8  717.56   659.5  718.26
   688.9  718.74   728.1  719.76   737.8  720.45   747.6  722.69   757.4  726.98
     777   737.5   786.8  742.52   796.6  746.66   806.4  749.84   884.7  773.41
#Mann= 3 , 0 , 0
       0     .06       0   610.6    .045       0     640     .06       0
Bank Sta=610.6,640
XS Rating Curve= 0 ,0
Exp/Cntr=0.3,0.1

Type RM Length L Ch R = 1 ,25498.1 ,244.8,245.6,245.9
XS GIS Cut Line= 2
      1568338.66      345861.927     1568008.799      345032.934
#Sta/Elev= 30
       0  731.92     9.8  728.05    19.6  726.82    29.4  725.23      49  721.22
    58.8  720.36   117.6   719.5   156.9  719.31   294.1  720.15   333.4  719.59
   392.2  717.71   421.6  717.07   588.3  716.81   598.1  716.54     601 716.102
   607.9  715.06   617.7   712.7   627.5  711.44   637.3  712.02   647.1  713.94
   656.9  716.22   666.7  717.76   686.3  718.82   705.9  720.62   725.5  723.33
   735.3  725.36   794.2  741.62   813.8  747.46     853  761.38   892.2   775.6
#Mann= 3 , 0 , 0
       0     .06       0     601    .045       0   656.9     .06       0
Bank Sta=601,656.9
XS Rating Curve= 0 ,0
Exp/Cntr=0.3,0.1

Type RM Length L Ch R = 1 ,25252.5 ,666.6,692.6,718.5
XS GIS Cut Line= 3
     1568555.674      345805.503     1568264.875      345009.062
     1568158.538         344970.
#Sta/Elev= 30
       0  746.57     9.8  741.54    29.2  730.25      39  725.48    48.7  722.74
    68.2  719.35      78  718.38   311.9  720.04   389.8  719.24   438.6  718.12
   545.8  717.74   584.7  716.64   604.2  711.69     614  710.56   623.7  711.39
   643.2  715.97   662.7  719.89   672.4  720.82   691.9   721.2   721.2   720.6
   750.4  722.61   779.6  723.78   799.1   725.4   828.4  726.78   847.9  728.34
   857.3  732.27   895.1  751.55   904.5  755.32     914  757.73   961.2  763.06
#Mann= 3 , 0 , 0
       0     .06       0   584.7    .045       0   643.2     .07       0
Bank Sta=584.7,643.2
XS Rating Curve= 0 ,0
Exp/Cntr=0.3,0.1

Type RM Length L Ch R = 1 ,24559.9 ,663.7,664.3,664.1
XS GIS Cut Line= 3
     1568694.562      345822.864     1568709.753      345696.996
     1569028.764      345356.284
#Sta/Elev= 30
       0  752.14     9.8  749.46    19.5  745.74    29.3  741.16    48.8  730.39
    58.5   725.5    68.3  722.45    87.8  720.13    97.5  718.74   107.3  717.85
     117  717.45   204.6  714.24   253.2  712.82   282.4  712.55     331  713.36
   340.7  712.86   350.4  710.83   360.2  709.16   369.9  709.39   379.6   712.5
     399  720.38   408.8  723.79   418.5  726.46   428.2  728.58     506  744.26
   515.7  746.03   544.9  750.71   564.4  754.38   583.8  758.72   593.5  761.68
#Mann= 3 , 0 , 0
       0     .06       0   340.7    .045       0   379.6      .1       0
Bank Sta=340.7,379.6
XS Rating Curve= 0 ,0
Exp/Cntr=0.3,0.1

Type RM Length L Ch R = 1 ,23895.7 ,182,183,184
XS GIS Cut Line= 3
     1569000.552      346265.573     1569115.569      346198.298
     1569421.559      345874.948
#Sta/Elev= 30
       0  743.45     9.5  743.13      19   742.4    28.6  741.17    47.6  739.53
    57.1  738.34    76.1  735.21    85.7  733.34   114.2  726.82   123.7  725.16
   152.6   722.4   162.3  720.02     172  717.26   181.6  716.17   210.7   715.5
   268.7  715.45   297.8  714.21   317.1  712.49   326.8  710.87   336.5  708.81
   346.2  707.58   355.8  707.82   365.5  709.81   404.2  720.46   413.9  723.73
   433.3  731.34     472  743.89     501  753.66   510.7  757.24   578.4  785.86
#Mann= 3 , 0 , 0
       0     .06       0   317.1    .045       0   365.5      .1       0
Bank Sta=317.1,365.5
XS Rating Curve= 0 ,0
Exp/Cntr=0.3,0.1

Type RM Length L Ch R = 1 ,23712.6 ,433.7,458.4,482
XS GIS Cut Line= 3
     1569219.736      346330.677     1569493.174       346068.09
     1570317.826       345918.35
#Sta/Elev= 30
       0  729.74    19.4  725.16    29.2  723.59    38.9  720.71    48.6  716.09
    58.3  712.78    97.2  708.56   116.6  708.43     175  711.32   194.4  711.03
   215.3709.2327   233.3  706.57   242.8   706.7   252.7  709.02   272.2  716.52
   291.6   722.8   379.1  748.39   564.3  790.08   583.8  793.39   710.5  792.02
   768.9  789.95   827.4  786.72   934.6  776.95  1012.6  774.11  1061.3  771.63
  1080.8  769.74  1129.5  761.73  1178.3  754.85  1197.8   750.6  1217.2  745.05
#Mann= 3 , 0 , 0
       0     .06       0   215.3    .045       0   252.7      .1       0
Bank Sta=215.3,252.7
XS Rating Curve= 0 ,0
Exp/Cntr=0.3,0.1