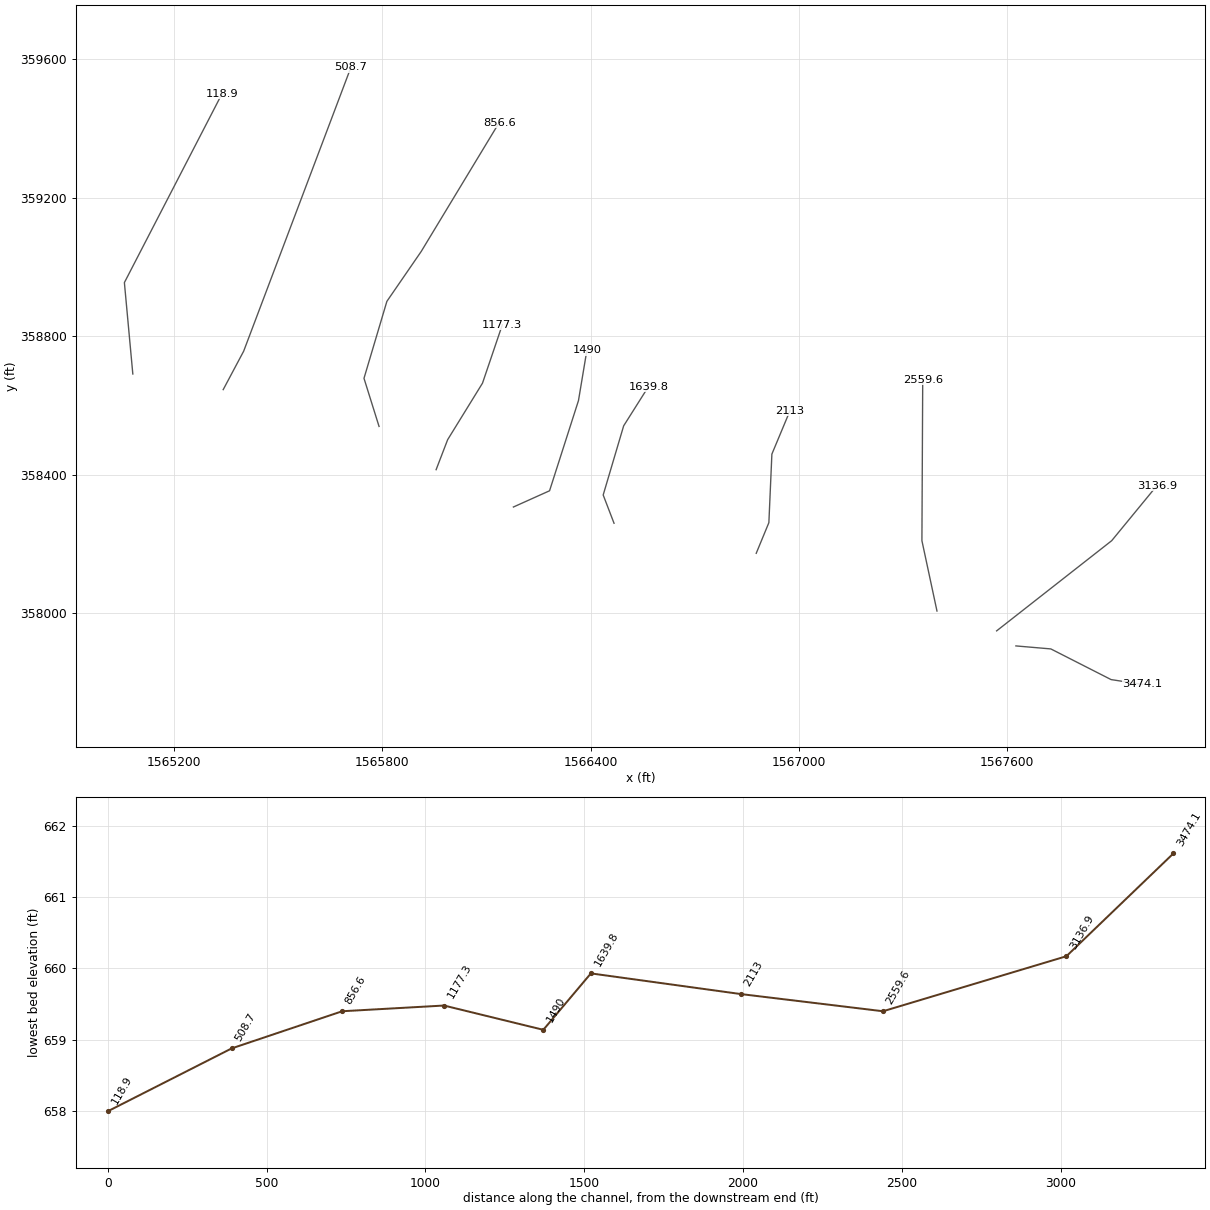
HEC-RAS study SNCHOCRK.prj: SNCHOCRK

--- SNCHOCRK.g01 (geometry) --- (continued)

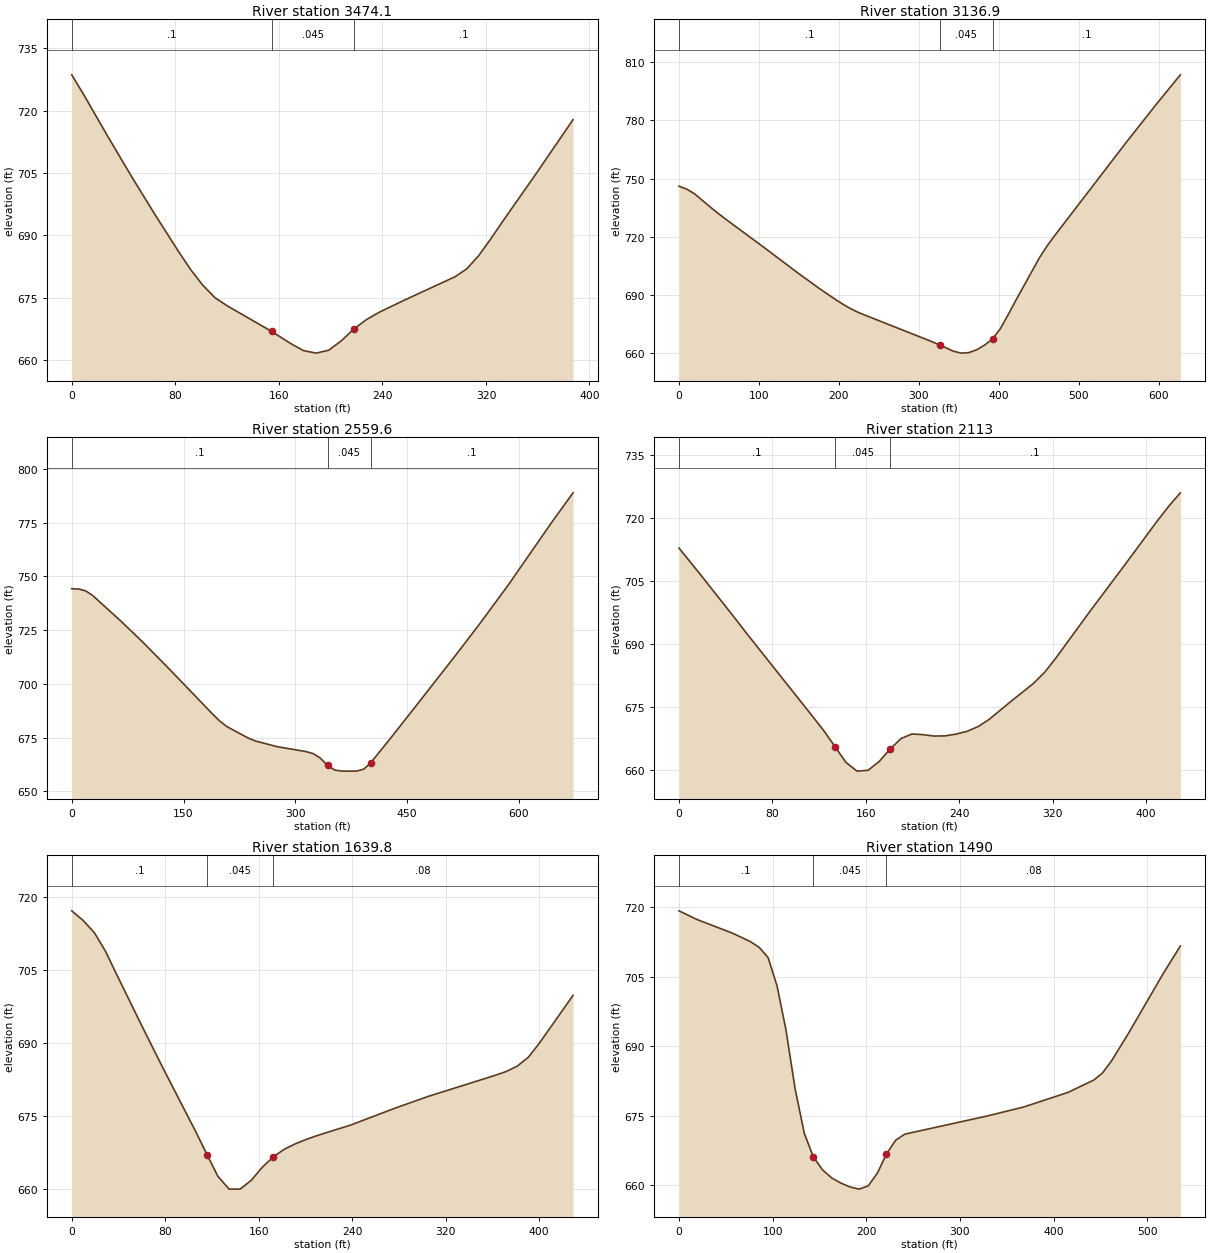
Type RM Length L Ch R = 1 ,3474.1  ,311.3,337.2,362.8
XS GIS Cut Line= 4
     1567625.682       357905.72     1567726.377       357897.04
     1567899.988      357808.498     1567990.266      357794.609
#Sta/Elev= 27
       0  728.63     9.2  723.89    27.6  713.94    45.9  704.31    64.3  694.99
    82.7  685.99    91.9  681.73   101.1  678.02   110.8  674.92   120.6  672.91
   154.4666.8474   169.3  663.89     179  662.23   188.8  661.61   198.5   662.3
   208.3  664.58     218  667.42   227.7  669.68   237.5  671.44     257  674.37
     296  679.98   305.1  681.87   314.2     685   323.4  688.96   332.5  693.12
   359.9  705.33   387.3  717.84
#Mann= 3 , 0 , 0
       0      .1       0   154.4    .045       0     218      .1       0
Bank Sta=154.4,218
XS Rating Curve= 0 ,0
Exp/Cntr=0.3,0.1

Type RM Length L Ch R = 1 ,3136.9  ,556.5,577.3,597.5
XS GIS Cut Line= 3
     1567570.127      357949.123     1567901.724       358209.54
     1568032.084      358368.517
#Sta/Elev= 30
       0  746.08     9.8  744.55    19.6  742.12    39.2  735.32      49  732.08
    58.8  728.99   107.9  714.09   147.1  701.91   176.5  693.15   196.1  687.68
   205.9  685.13   215.7  682.83   225.5  680.89   313.8   666.5   326.7664.2842
   343.2  661.17     353  660.17   362.8  660.45   372.6  661.92   382.4  664.34
   392.2  667.44     402  672.78   411.8  679.95   421.6  687.51     451  709.33
   460.8   715.5   470.6  720.99   558.7  768.22   597.8   788.6   627.2  803.41
#Mann= 3 , 0 , 0
       0      .1       0   326.7    .045       0   392.2      .1       0
Bank Sta=326.7,392.2
XS Rating Curve= 0 ,0
Exp/Cntr=0.3,0.1

Type RM Length L Ch R = 1 ,2559.6  ,447.3,446.6,445.5
XS GIS Cut Line= 3
     1567398.252      358006.415     1567354.849       358209.54
     1567357.171      358674.506
#Sta/Elev= 30
       0  744.28     9.4  744.16    18.9  743.27    28.3   741.1    66.1  729.19
    94.4  719.77   132.2  706.47   188.8  686.03   198.3  682.81   207.7  680.23
   236.8  674.79   246.5  673.44   275.5  670.79   314.3  668.51     324  667.55
   333.6  665.46   343.3  662.04     353  659.86   362.7  659.42   372.4   659.4
   382.1   659.4   391.8   660.3   401.4  663.33   430.5  675.89   469.3  692.99
   517.7  714.47   546.8  727.66   585.5  745.88   643.6  774.95   672.7  788.94
#Mann= 3 , 0 , 0
       0      .1       0   343.3    .045       0   401.4      .1       0
Bank Sta=343.3,401.4
XS Rating Curve= 0 ,0
Exp/Cntr=0.3,0.1

Type RM Length L Ch R = 1 ,2113    ,478.6,473.2,467.5
XS GIS Cut Line= 4
     1566877.418      358173.081     1566913.877      358261.623
     1566922.557       358459.54     1566974.641       358584.54
#Sta/Elev= 30
       0  712.74    19.2  706.13    47.9  696.04    57.4   692.6   114.6  672.59
   124.1  669.22   133.5  665.49   142.9  661.73   152.4  659.64   161.8  659.83
   171.2  661.88   180.7  664.87   190.1  667.39   199.5  668.49     209  668.32
   218.4  667.99   227.8  668.03   237.3  668.46   246.7  669.12   256.1  670.24
   265.6  671.97   284.4  676.28   303.5  680.52   313.2   683.2   322.9  686.64
   351.9  697.69   380.9  708.43   409.9  719.34   419.6  722.79   429.3   725.9
#Mann= 3 , 0 , 0
       0      .1       0   133.5    .045       0   180.7      .1       0
Bank Sta=133.5,180.7
XS Rating Curve= 0 ,0
Exp/Cntr=0.3,0.1

Type RM Length L Ch R = 1 ,1639.8  ,150.3,149.8,149.3
XS GIS Cut Line= 4
     1566467.696      358259.887     1566436.446      358341.484
     1566495.474      358541.137     1566566.654      358653.984
#Sta/Elev= 29
       0   717.1     9.7  715.14    19.4   712.6    29.1  708.71    38.8  703.85
    58.2  694.35      68  689.63    77.7  684.98   106.3  671.66   115.8  666.99
   125.2  662.52   134.7  659.93   144.2  659.94   153.6  661.74   163.1  664.43
   172.5666.5574     182  668.14   191.5  669.25   200.9  670.16   210.4  670.96
   238.8   673.1   276.6  676.55   305.1  678.98   362.3   683.3   371.8  684.09
   381.3   685.2   390.9  687.06   400.4  689.98     429  699.73
#Mann= 3 , 0 , 0
       0      .1       0   115.8    .045       0   172.5     .08       0
Bank Sta=115.8,172.5
XS Rating Curve= 0 ,0
Exp/Cntr=0.3,0.1

Type RM Length L Ch R = 1 ,1490    ,317.7,312.7,306.7
XS GIS Cut Line= 4
     1566177.766      358306.762     1566281.932      358353.637
     1566365.266      358614.054     1566389.571      358759.887
#Sta/Elev= 30
       0  719.27      19  717.41    57.1  714.44    76.2  712.62    85.7  711.37
    95.2  709.14   104.7  703.04   114.2  693.55     124   680.8   133.8  671.19
   143.5  666.08   153.3   663.3     163  661.57   172.8  660.45   182.6  659.61
   192.4  659.14   202.1  659.84   211.9  662.62   221.6  666.72   231.4  669.71
   241.2  671.02   329.1  674.94   368.1  676.88   415.4  680.03   443.1  682.71
   452.3  684.23   461.6  686.73   480.1   692.8     517  705.65   535.5  711.67
#Mann= 3 , 0 , 0
       0      .1       0   143.5    .045       0   221.6     .08       0
Bank Sta=143.5,221.6
XS Rating Curve= 0 ,0
Exp/Cntr=0.3,0.1

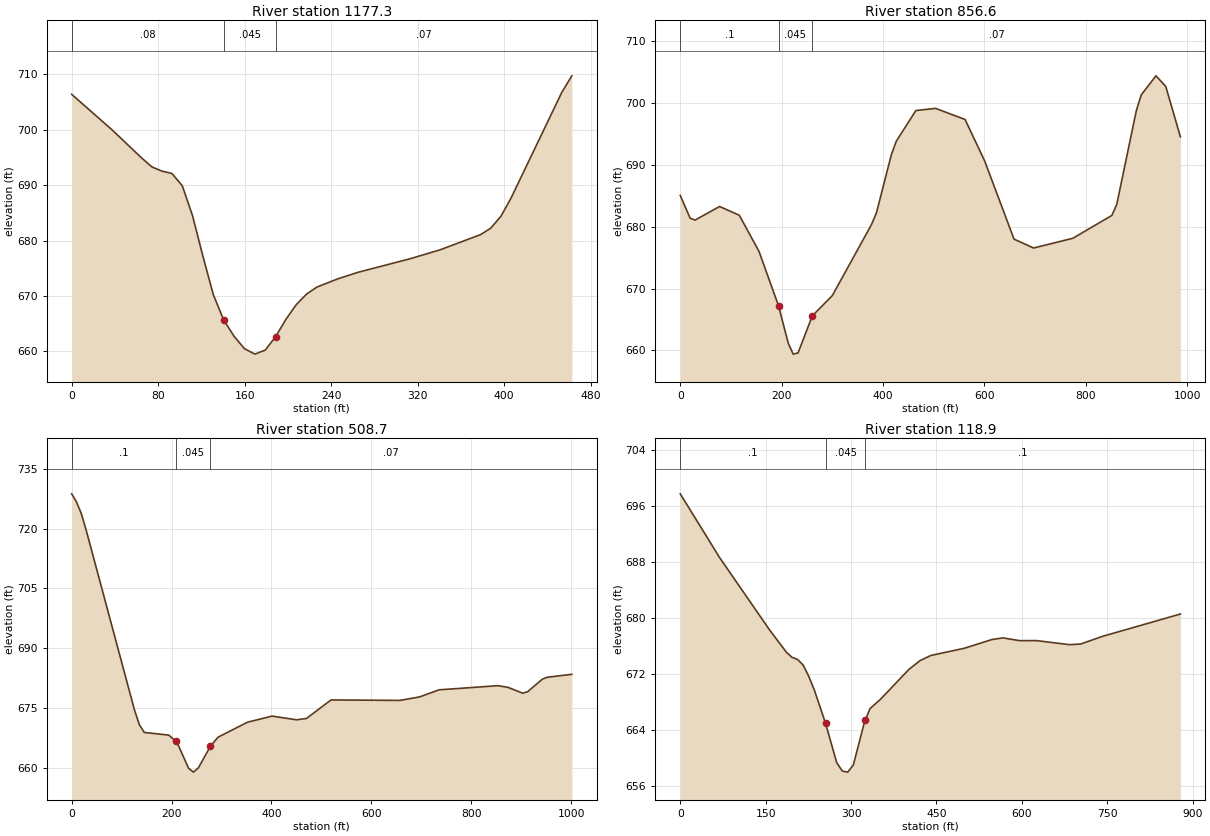
Type RM Length L Ch R = 1 ,1177.3  ,314.3,320.6,326.3
XS GIS Cut Line= 4
     1565955.067      358414.541     1565988.266      358501.076
     1566088.715       358664.34     1566145.915      358833.043
#Sta/Elev= 30
       0   706.4    37.1  700.03    64.9  694.87    74.2  693.29    83.4  692.54
    92.7   692.1   102.3  689.89   111.8  684.46   121.4  677.13     131  670.21
   140.6  665.64   150.2   662.7   159.8  660.46   169.4  659.48     179  660.21
   188.5   662.6   198.1  665.75   207.7  668.42   217.3  670.34   226.9   671.6
     246  673.07   265.2  674.28   312.5  676.68   340.6  678.31   378.1  681.06
   387.5  682.22   396.9  684.36   406.3  687.66   453.1   706.7   462.5  709.74
#Mann= 3 , 0 , 0
       0     .08       0   140.6    .045       0   188.5     .07       0
Bank Sta=140.6,188.5
XS Rating Curve= 0 ,0
Exp/Cntr=0.3,0.1

Type RM Length L Ch R = 1 ,856.6   ,349.5,347.9,346.1
XS GIS Cut Line= 5
     1565790.613      358539.401      1565747.21       358678.29
     1565813.182      358900.512     1565912.141      359044.609
     1566136.678      359416.484
#Sta/Elev= 30
       0  685.05    19.4  681.38    29.1  681.06    77.6  683.26   116.4  681.85
   155.2  676.03   193.8  667.23   213.1  661.15   222.8   659.4   232.4   659.6
   260.4665.5733     300  668.87   377.3  680.36     387  682.24   416.2  691.58
   425.9  693.78   464.7  698.77   503.6  699.12   561.8  697.32   600.4  690.63
   658.3  677.99   696.9  676.55   774.2  678.12   851.4  681.82     861  683.61
   899.6  698.77   909.3   701.3   938.3  704.38   957.6  702.67   986.5  694.52
#Mann= 3 , 0 , 0
       0      .1       0   193.8    .045       0   260.4     .07       0
Bank Sta=193.8,260.4
XS Rating Curve= 0 ,0
Exp/Cntr=0.3,0.1

Type RM Length L Ch R = 1 ,508.7   ,392.5,389.9,387.3
XS GIS Cut Line= 3
     1565341.539      358645.651     1565400.566      358756.762
     1565709.594      359576.206
#Sta/Elev= 30
       0  728.73     9.7  726.69    19.4  723.73      29  719.64   125.8  674.47
   135.7  670.74   145.5  668.84   194.7  668.17     208666.6536   214.4  665.38
   234.1  659.86   243.9  658.88   253.7  659.95     278665.3936   293.1  667.65
   352.1  671.41   401.3  672.94   450.5  672.01   470.2  672.35   519.4     677
   657.2  676.88   696.6  677.75   735.9  679.54     854  680.58   873.7  680.16
   903.2   678.7     913  679.05   942.6  682.21   952.4  682.69  1001.6  683.43
#Mann= 3 , 0 , 0
       0      .1       0     208    .045       0     278     .07       0
Bank Sta=208,278
XS Rating Curve= 0 ,0
Exp/Cntr=0.3,0.1

Type RM Length L Ch R = 1 ,118.9   ,115.5,118.9,122.2
XS GIS Cut Line= 3
     1565081.122       358690.79     1565056.816      358954.679
     1565338.066      359499.817
#Sta/Elev= 30
       0  697.78    68.7  688.72     157  678.31   186.5  675.13   196.3  674.41
   206.1   674.1   215.9   673.3   225.8  671.67   235.6  669.71   255.2  664.98
   274.7  659.38   284.5  658.16   294.2     658     304  659.03   323.4  665.12
   325.2665.4781   333.2  667.07   352.6  668.49   401.3  672.66   420.8  673.92
   440.3  674.68   498.7   675.7   547.4  676.95   566.8  677.19   596.1  676.79
   625.3   676.8   683.7  676.22   703.2  676.31   742.1  677.42   878.4   680.6
#Mann= 3 , 0 , 0
       0      .1       0   255.2    .045       0   325.2      .1       0
Bank Sta=255.2,325.2
XS Rating Curve= 0 ,0
Exp/Cntr=0.3,0.1

Chan Stop Cuts=-1
Use User Specified Reach Order=0
Composite Channel Slope=5

--- SNCHOCRK.g02 (geometry) ---

Geom Title=USGS 10m DEM_copy
Program Version=4.10

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
River Reach=SNCHOCRK        ,Main

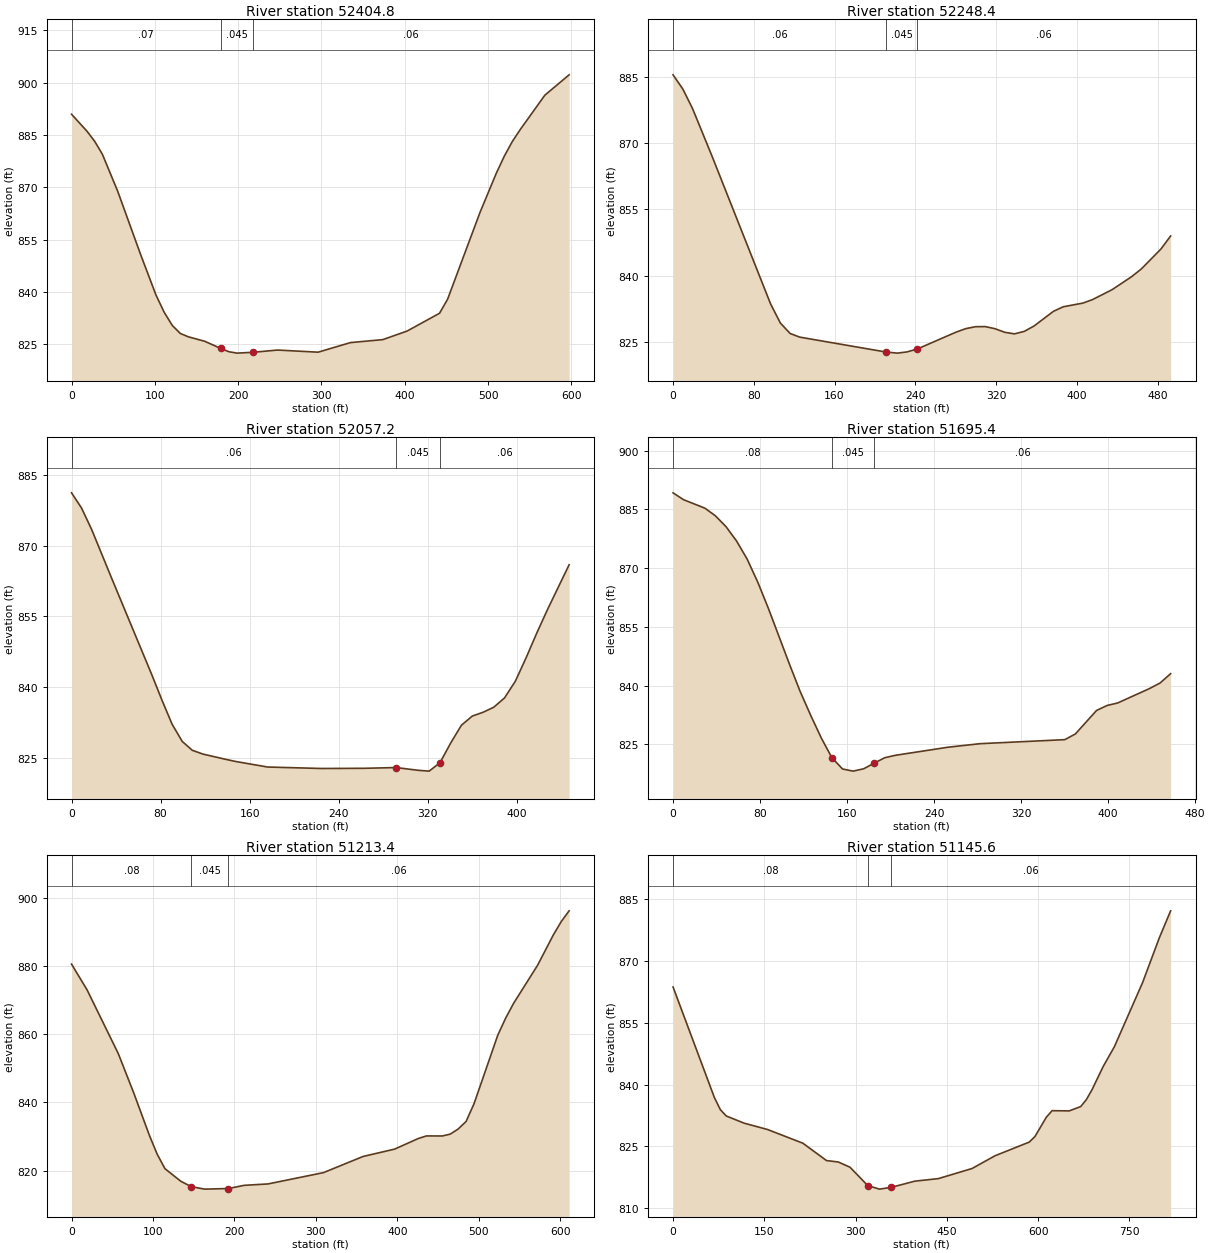
Type RM Length L Ch R = 1 ,52404.8 ,135.6,156.4,165.7
XS GIS Cut Line= 3
     1570080.522      327703.832      1570148.23      327628.311
     1570603.959      327432.999
#Sta/Elev= 30
       0  890.92    18.4   886.1    27.7  883.19    36.9  879.51    55.3  868.92
      83  850.66   101.4  839.07   111.2  834.17   120.9   830.4   130.6  828.09
   140.3  827.13   159.8  825.86   179.2  823.79   188.9  822.86   198.6  822.46
   218.1   822.7   247.3  823.34   295.9  822.73   334.8  825.48   373.6  826.33
   402.8  828.79   441.7  833.89   451.4  837.94   490.3  862.82   509.8  874.01
   519.5  878.95   529.2  883.17   538.9  886.66   568.1  896.39   597.2  902.22
#Mann= 3 , 0 , 0
       0     .07       0   179.2    .045       0   218.1     .06       0
Bank Sta=179.2,218.1
XS Rating Curve= 0 ,0
Exp/Cntr=0.3,0.1

Type RM Length L Ch R = 1 ,52248.4 ,157.1,191.2,187.7
XS GIS Cut Line= 2
     1570136.605      327750.107     1570607.525      327604.707
#Sta/Elev= 30
       0  885.39     9.7  882.17    19.3  877.77    38.7  866.96    96.6  833.63
   106.3   829.3     116  826.93   125.6  826.11     211 822.746   222.3   822.5
   231.9  822.78     242 823.436   280.2  827.23   289.9  828.03   299.6  828.47
   309.2   828.5   318.9  828.02   328.6  827.21   338.2  826.85   347.9  827.41
   357.6  828.63   376.9  831.96   386.6  832.98   405.9   833.8   415.5  834.59
   434.9  836.84   454.2  839.77   463.9  841.53   483.2     846   492.9  848.97
#Mann= 3 , 0 , 0
       0     .06       0     211    .045       0     242     .06       0
Bank Sta=211,242
XS Rating Curve= 0 ,0
Exp/Cntr=0.3,0.1

Type RM Length L Ch R = 1 ,52057.2 ,367.1,361.8,345.9
XS GIS Cut Line= 3
     1570197.709      327854.874     1570296.667      327810.603
     1570619.584      327709.041
#Sta/Elev= 30
       0  881.19       9  877.95    18.1  873.39    36.1  863.02    72.3  842.46
    81.3  837.14    90.3  832.09    99.4  828.43   108.4  826.55   118.1  825.73
   137.4  824.68   147.1  824.18   176.1  822.99   224.5  822.68   263.2  822.72
   291.5  822.88   311.5  822.29   321.2  822.12   330.9  823.89   340.5  828.07
   350.2  831.87   359.9   833.8   369.6  834.61   379.2  835.68   388.9  837.66
   398.6   841.2   408.2  846.14   417.9  851.45   427.6  856.47   446.9  865.92
#Mann= 3 , 0 , 0
       0     .06       0   291.5    .045       0   330.9     .06       0
Bank Sta=291.5,330.9
XS Rating Curve= 0 ,0
Exp/Cntr=0.3,0.1

Type RM Length L Ch R = 1 ,51695.4 ,456.6,482,458.6
XS GIS Cut Line= 2
     1570195.105      328018.936     1570635.209      327893.936
#Sta/Elev= 30
       0  889.22     9.7  887.46    29.2  885.31    38.9  883.36    48.7  880.58
    58.4  876.91    68.1  872.31    77.9   866.4    87.6  859.74   107.1   845.4
   116.8  838.52   126.6  832.35   136.3   826.6     146  821.57   155.8  818.68
   165.5  818.13   175.2  818.72     185  820.18   194.7  821.56   204.4  822.17
   253.1  824.25   282.3  825.14   360.2  826.17   369.9  827.62   389.4  833.63
   399.1   834.9   408.8  835.54     438  839.21   447.8  840.64   457.5  843.02
#Mann= 3 , 0 , 0
       0     .08       0     146    .045       0     185     .06       0
Bank Sta=146,185
XS Rating Curve= 0 ,0
Exp/Cntr=0.3,0.1

Type RM Length L Ch R = 1 ,51213.4 ,92.1,67.8,41.5
XS GIS Cut Line= 4
     1570239.376      328261.124     1570327.917      328334.041
      1570679.48      328219.457     1570781.042      328143.936
#Sta/Elev= 30
       0  880.55    19.1  872.99    57.4  854.32    76.5  842.72    95.6  830.36
   105.1  824.87   114.7   820.6   134.2   816.9     147  815.33   163.4   814.6
   192.6  814.77     212  815.71   241.2  816.12   309.3  819.43     358  824.17
   396.9  826.34   426.1  829.47   435.8  830.19   455.3  830.18     465  830.72
   474.7  832.21   484.5  834.44   494.2   839.6   523.4  859.72   533.1  864.73
   542.9  869.09   572.1  880.14   591.6  889.09   601.3  893.01     611  896.17
#Mann= 3 , 0 , 0
       0     .08       0     147    .045       0   192.6     .06       0
Bank Sta=147,192.6
XS Rating Curve= 0 ,0
Exp/Cntr=0.3,0.1

Type RM Length L Ch R = 1 ,51145.6 ,63.9,63.5,65.1
XS GIS Cut Line= 6
     1570210.187      328649.904      1570247.08      328539.227
     1570490.135      328289.661     1570516.177      328285.321
     1570693.043      328261.449     1570815.656      328343.915
#Sta/Elev= 30
       0  863.66      68  836.83    77.8   833.9    87.5  832.38   116.7  830.65
   155.4   829.1   213.4  825.78   252.1  821.58   271.5  821.23   290.8  819.96
   319.9  815.52   339.2  814.65   358.6  815.08   397.3  816.58     436   817.2
   491.4  819.65     529  822.73   585.4  826.06   594.8  827.42   613.5   832.1
   622.9  833.67   651.1  833.62   669.9  834.67   679.1  836.33   688.4  838.72
   706.8  844.37   725.3  849.19   771.5  864.69   799.2  875.61   817.7  882.13
#Mann= 3 , 0 , 0
       0     .08       0   319.9    .045       0   358.6     .06       0
Bank Sta=319.9,358.6
XS Rating Curve= 0 ,0
Exp/Cntr=0.3,0.1

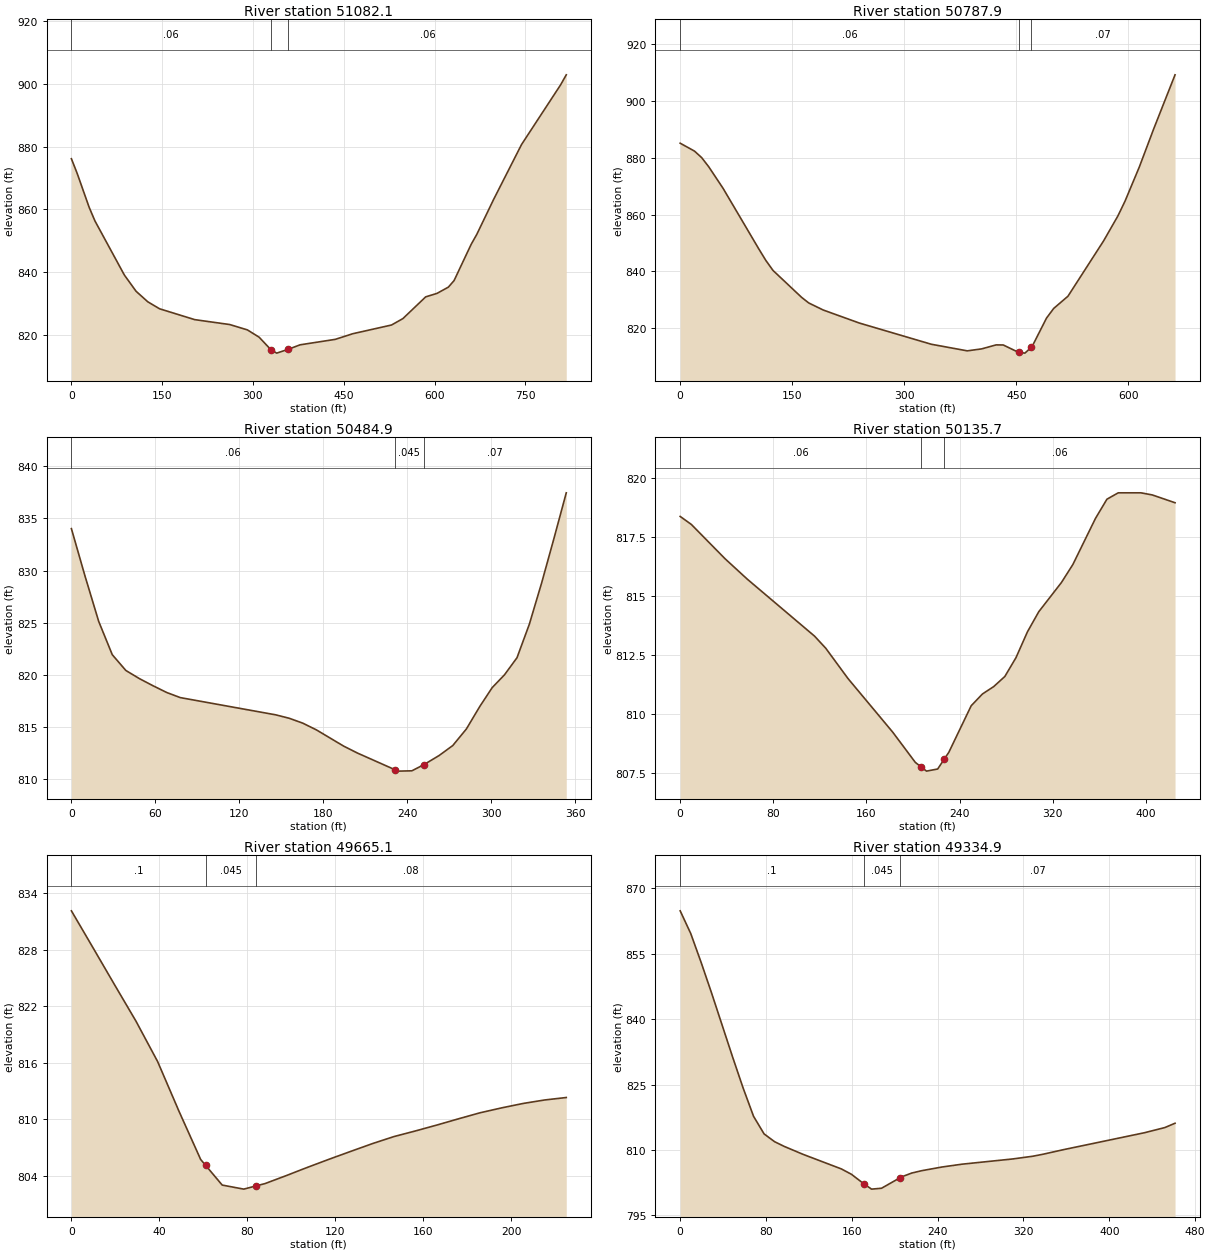
Type RM Length L Ch R = 1 ,51082.1 ,169.6,294.3,322.8
XS GIS Cut Line= 6
     1570250.335      328698.732     1570287.227      328588.055
     1570530.283      328338.489     1570556.325      328334.149
     1570733.191      328310.278     1570855.804      328392.743
#Sta/Elev= 30
       0  876.15     9.7  871.39    29.2  860.72    38.9  856.31    87.5  839.06
   106.9  833.87   126.3  830.51   145.7  828.29   203.8  824.83   261.8  823.26
   290.8  821.56   310.2  819.23   329.6  815.26   339.2  814.15   358.6  815.39
   377.9   816.8     436  818.54     465  820.34     529  823.12   547.8  825.17
   585.4  832.09   604.2  833.21   622.9   835.2   632.3  837.28   660.5  848.82
   669.9  852.04   697.6  863.14   743.8  880.68   808.4  899.73   817.7  902.91
#Mann= 3 , 0 , 0
       0     .06       0   329.6    .045       0   358.6     .06       0
Bank Sta=329.6,358.6
XS Rating Curve= 0 ,0
Exp/Cntr=0.3,0.1

Type RM Length L Ch R = 1 ,50787.9 ,348.4,302.9,309.4
XS GIS Cut Line= 4
     1570259.341      328777.834     1570329.654      328652.834
     1570670.799      328548.667     1570832.258      328530.438
#Sta/Elev= 30
       0  885.03    19.1  882.27    28.7  879.99    38.2  876.77    57.4   869.2
   105.2  847.95   114.7  843.88   124.3  840.36   162.7  830.88   172.3  828.92
   191.6  826.46   239.8   821.9   336.2  814.45   384.4  812.13   403.7  812.82
     423  814.22   432.6  814.19     453 811.605   461.6  811.33     470 813.351
   471.2  813.64   490.5  823.62   500.1  827.01   519.2   831.3     567  850.76
   586.1   859.5   595.7  864.72   614.8   876.7   633.9  889.97   662.6  909.04
#Mann= 3 , 0 , 0
       0     .06       0     453    .045       0     470     .07       0
Bank Sta=453,470
XS Rating Curve= 0 ,0
Exp/Cntr=0.3,0.1

Type RM Length L Ch R = 1 ,50484.9 ,316.4,349.2,378.3
XS GIS Cut Line= 3
      1570398.99      328839.791     1570690.873      328845.217
     1570746.212       328818.09
#Sta/Elev= 30
       0  834.01     9.7  829.48    19.5  825.13    29.2  821.94    38.9  820.43
    48.7  819.64    58.4  818.96    68.1  818.32    77.8  817.83     146  816.18
   155.7  815.85   165.4  815.38   175.2  814.73   194.6  813.18   204.4  812.52
     231 810.936   233.6  810.79   243.3  810.82     252 811.421   262.7  812.28
   272.5  813.24   282.2  814.82   291.9     817   300.7  818.79   309.5  820.02
   318.4  821.65   327.2  824.85     336  828.81   344.8  833.07   353.6  837.44
#Mann= 3 , 0 , 0
       0     .06       0     231    .045       0     252     .07       0
Bank Sta=231,252
XS Rating Curve= 0 ,0
Exp/Cntr=0.3,0.1

Type RM Length L Ch R = 1 ,50135.7 ,463.5,470.6,422.6
XS GIS Cut Line= 3
     1570476.029      328977.595     1570682.193      329179.418
     1570817.826      329195.694
#Sta/Elev= 29
       0  818.39     9.6  818.05    38.5   816.6    57.7  815.73   115.4  813.32
     125  812.81   144.2  811.52   182.6  809.25     202  807.97     207 807.777
   211.6   807.6   221.2  807.69     227 808.119   230.8   808.4     250  810.37
   259.7  810.87   269.3  811.18   278.9  811.61   288.5  812.41   298.3   813.5
     308  814.35   327.5  815.59   337.3  816.35   356.8  818.31   366.6  819.12
   376.3  819.39   395.8  819.39   405.6   819.3   425.1  818.97
#Mann= 3 , 0 , 0
       0     .06       0     207    .045       0     227     .06       0
Bank Sta=207,227
XS Rating Curve= 0 ,0
Exp/Cntr=0.3,0.1

Type RM Length L Ch R = 1 ,49665.1 ,335.1,330.2,350.1
XS GIS Cut Line= 4
     1570357.757      329414.878     1570408.755      329444.175
     1570496.646      329446.345      1570559.58      329399.687
#Sta/Elev= 28
       0  832.14     9.8  828.23    19.6   824.3    29.4  820.41    34.9  818.01
    39.2  816.14      49  810.82    58.8  805.73      61 805.119    68.6  803.01
    78.4  802.58      84 802.921    88.1  803.17    97.9  804.03   104.9  804.67
   107.7  804.92   117.4  805.77   127.2   806.6     137  807.42   146.7  808.16
   156.5  808.76   166.3  809.39   176.1  810.05   185.9  810.69   195.7  811.21
   205.5  811.68   215.3  812.05   225.1  812.31
#Mann= 3 , 0 , 0
       0      .1       0      61    .045       0      84     .08       0
Bank Sta=61,84
XS Rating Curve= 0 ,0
Exp/Cntr=0.3,0.1

Type RM Length L Ch R = 1 ,49334.9 ,146.5,113.7,77.5
XS GIS Cut Line= 5
     1570287.227      329788.142     1570342.566      329719.783
     1570393.564      329733.889     1570504.241      329784.887
     1570702.809      329787.057
#Sta/Elev= 29
       0  864.87     9.8  859.69    19.5  853.06    29.3     846    48.9  831.32
    58.6  824.28    68.4  817.74    78.2  813.71      88  811.92    96.8  810.86
   114.4  809.03   150.2  805.68   159.6  804.45     171   802.3   178.4  801.04
   187.7  801.24     205 803.659   206.5  803.86   215.9  804.73   225.2  805.27
     244  806.11   262.7  806.76     310  807.96   328.9  808.59   338.4  809.05
   357.3  810.09   432.9  813.98   451.8  815.16   461.3  816.15
#Mann= 3 , 0 , 0
       0      .1       0     171    .045       0     205     .07       0
Bank Sta=171,205
XS Rating Curve= 0 ,0
Exp/Cntr=0.3,0.1

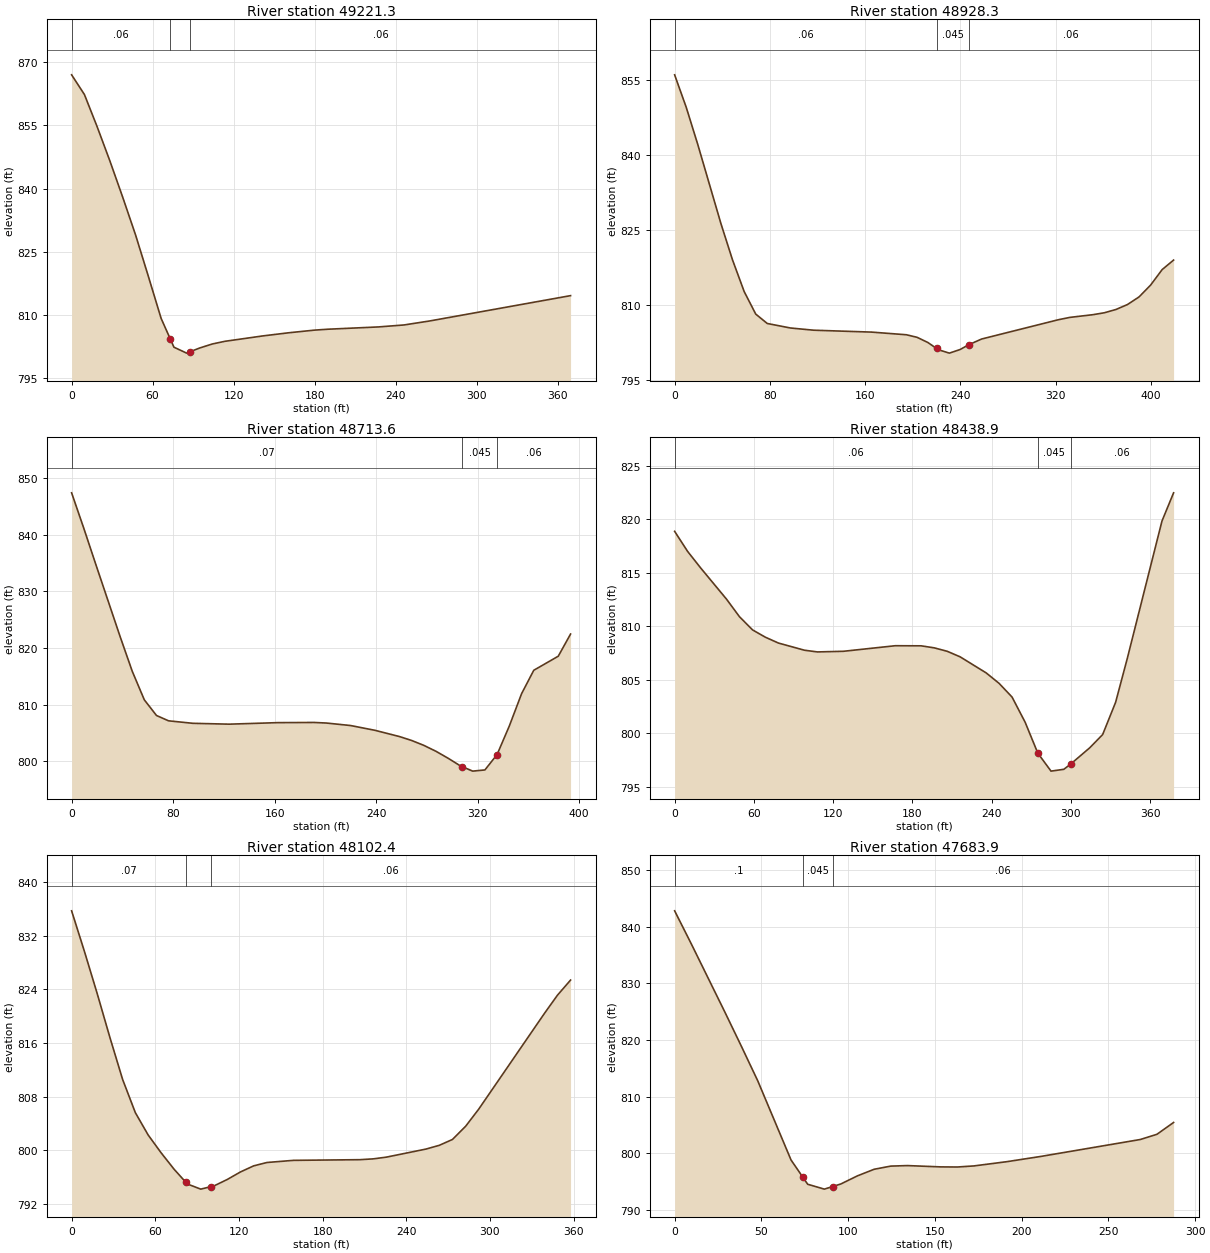
Type RM Length L Ch R = 1 ,49221.3 ,289,293,279.2
XS GIS Cut Line= 4
      1570324.12      329873.863     1570385.969      329849.991
     1570494.476      329816.354     1570683.278      329797.908
#Sta/Elev= 23
       0     867     9.5  862.32    18.9  854.69    28.4  846.52    37.9   837.9
    47.4  828.96    56.8  819.21    66.3  809.17      73 804.346    75.8  802.33
    85.2  800.92      88 801.274    94.7  802.12   104.2  803.09   113.6  803.73
     142  805.02     161  805.76   179.9  806.38   189.4  806.59   227.3  807.14
   246.3  807.61   265.3  808.56   369.6  814.57
#Mann= 3 , 0 , 0
       0     .06       0      73    .045       0      88     .06       0
Bank Sta=73,88
XS Rating Curve= 0 ,0
Exp/Cntr=0.3,0.1

Type RM Length L Ch R = 1 ,48928.3 ,174.5,214.7,266.2
XS GIS Cut Line= 4
     1570325.407      330067.815     1570515.294      330110.133
     1570609.696      330056.964     1570725.798      330053.709
#Sta/Elev= 30
       0  856.03     9.7  849.57    19.4  842.14    38.9  826.29    48.6  819.06
    58.4  812.73    68.1  808.23    77.8  806.35    97.3  805.45   116.7  805.01
   165.4  804.63   194.6   804.1   203.6  803.59   212.6  802.56     220  801.36
   221.6   801.1   230.7  800.43   239.7  801.15     247 802.107   257.8  803.25
   322.2   807.1   331.9  807.57   351.3  808.11     361   808.5   370.6  809.15
   380.3  810.14     390  811.66   399.7  814.02   409.4  817.12     419  819.02
#Mann= 3 , 0 , 0
       0     .06       0     220    .045       0     247     .06       0
Bank Sta=220,247
XS Rating Curve= 0 ,0
Exp/Cntr=0.3,0.1

Type RM Length L Ch R = 1 ,48713.6 ,281.2,274.7,269.3
XS GIS Cut Line= 3
     1570304.588      330158.151     1570519.432      330238.446
     1570661.576      330319.826
#Sta/Elev= 30
       0  847.37     9.6  841.12    19.1  834.73    38.2  822.04    47.8   815.9
    57.3  810.87    66.9  808.11    76.4  807.17    95.6  806.73   124.2  806.58
   162.5  806.85   191.1  806.88   200.7  806.78   219.8  806.34     239   805.5
   258.3   804.4   267.9  803.71   277.5  802.85   287.2  801.79   296.8  800.56
   306.4  799.22     308 799.068   316.1   798.3   325.7  798.51   335.3  801.22
     345  806.29   354.6  811.95   364.2  816.08   383.5  818.56   393.2  822.47
#Mann= 3 , 0 , 0
       0     .07       0     308    .045       0   335.3     .06       0
Bank Sta=308,335.3
XS Rating Curve= 0 ,0
Exp/Cntr=0.3,0.1

Type RM Length L Ch R = 1 ,48438.9 ,341.9,336.4,347.6
XS GIS Cut Line= 4
     1570209.102      330421.823     1570455.413      330520.564
     1570518.347      330547.691      1570555.24      330571.562
#Sta/Elev= 30
       0  818.86     9.8  816.99    19.7  815.44    39.3  812.52    49.1  810.88
      59  809.65    68.8  808.96    78.6  808.42    98.3  807.75   108.1  807.59
   127.8  807.65   167.1  808.17   186.7  808.16   196.6  807.97   206.4  807.65
   216.2  807.13   235.9  805.63   245.7  804.65   255.5  803.37   265.4  801.02
     275  798.13     285  796.45   294.7  796.62     300 797.123   314.3  798.63
   324.1  799.87   333.9  802.88   342.7  806.96     369  819.82   377.8  822.46
#Mann= 3 , 0 , 0
       0     .06       0     275    .045       0     300     .06       0
Bank Sta=275,300
XS Rating Curve= 0 ,0
Exp/Cntr=0.3,0.1

Type RM Length L Ch R = 1 ,48102.4 ,433.5,418.5,383.6
XS GIS Cut Line= 4
     1570184.146      330754.939     1570248.165      330754.939
     1570404.415      330863.446     1570485.795      330927.465
#Sta/Elev= 30
       0  835.75     9.2  829.68    18.3  823.42    27.4  816.87    36.6  810.54
    45.7  805.59    54.9  802.25      64  799.64    73.5  797.13      82 795.162
      83  794.93    92.6  794.16     100 794.534   102.1  794.64   111.6   795.6
   121.1  796.73   130.6  797.64   140.1  798.14   159.1  798.46   206.7  798.56
   216.2  798.68   225.7  798.94   254.2  800.15   263.7  800.71   273.1  801.58
   282.5  803.54   291.9   806.1     339   820.4   348.4  823.14   357.8   825.4
#Mann= 3 , 0 , 0
       0     .07       0      82    .045       0     100     .06       0
Bank Sta=82,100
XS Rating Curve= 0 ,0
Exp/Cntr=0.3,0.1

Type RM Length L Ch R = 1 ,47683.9 ,182.5,221.3,246.1
XS GIS Cut Line= 2
      1570101.68       331168.35     1570389.224      331165.095
#Sta/Elev= 23
       0  842.82     9.6  836.98    28.8  825.02    38.3  818.99    47.9  812.78
    67.1  798.78      74 795.697    76.7  794.49    86.3  793.63      91  794.08
    95.8  794.54   105.4  795.98     115  797.14   124.6   797.7   134.2  797.79
   153.4  797.56     163  797.54   172.5  797.73   191.7  798.49   210.9   799.4
   268.4   802.4     278  803.32   287.6  805.41
#Mann= 3 , 0 , 0
       0      .1       0      74    .045       0      91     .06       0
Bank Sta=74,91
XS Rating Curve= 0 ,0
Exp/Cntr=0.3,0.1

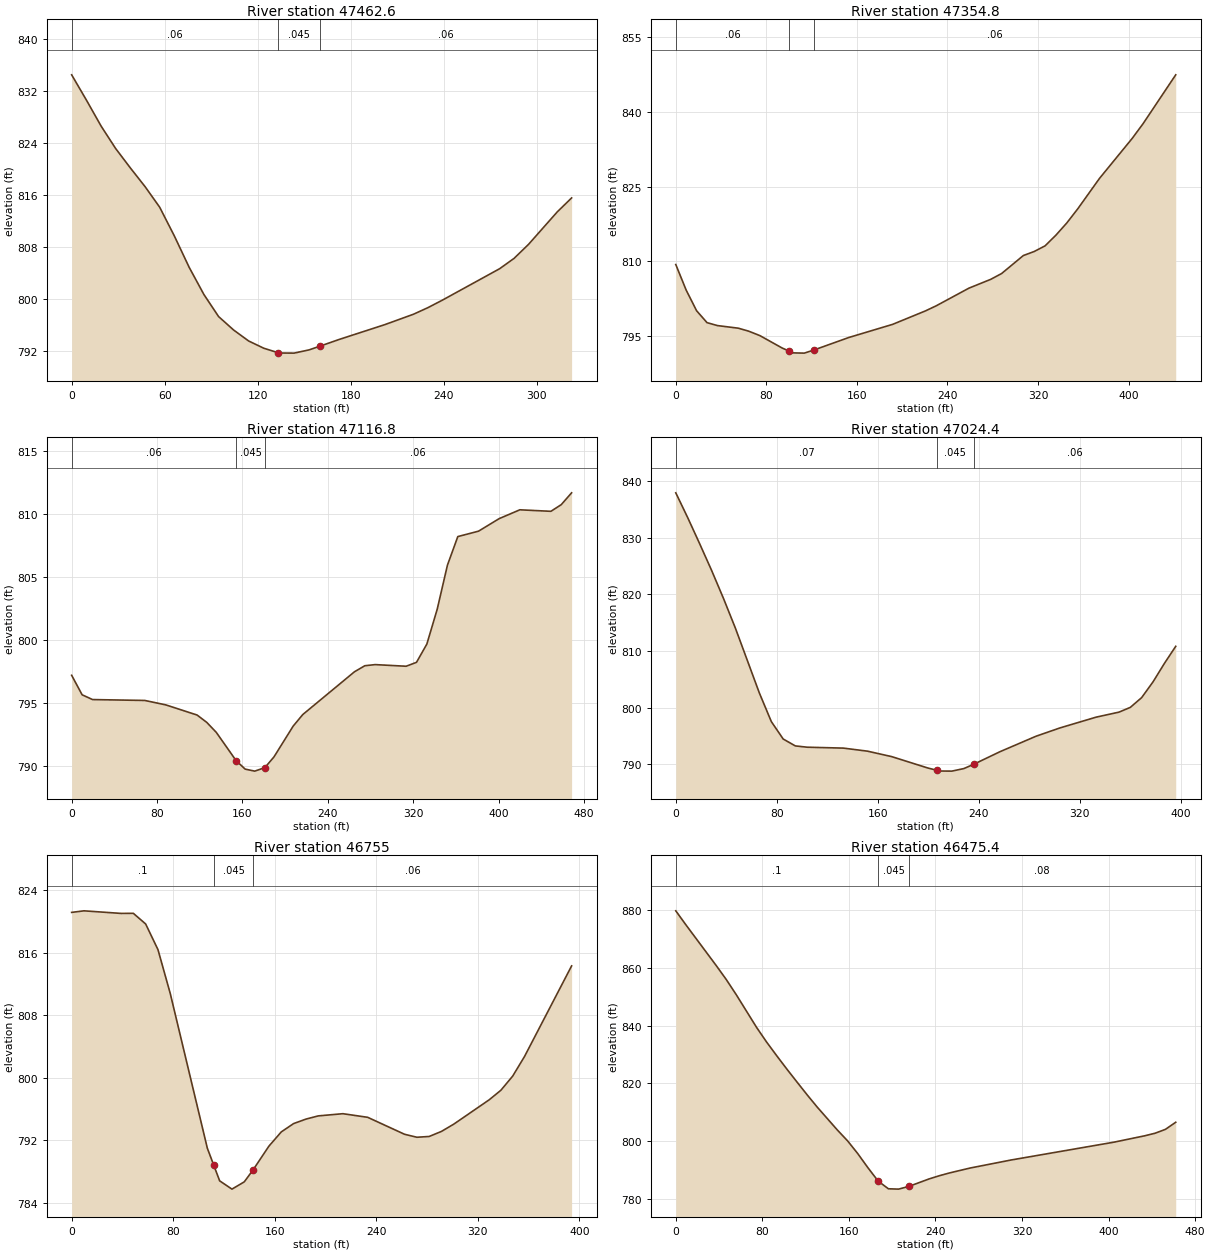
Type RM Length L Ch R = 1 ,47462.6 ,116.7,107.8,110.1
XS GIS Cut Line= 4
     1570110.361      331302.899     1570183.061      331363.663
     1570279.632      331410.321     1570400.075      331416.831
#Sta/Elev= 29
       0  834.56     9.5  830.68      19  826.67    28.4  823.21    37.9  820.22
    47.4  817.34    56.8  814.18    66.3  809.74    75.8  804.94    85.3  800.76
    94.8  797.35   104.5  795.28   114.2  793.59     124  792.47     133   791.8
   133.8  791.74   143.5  791.72   153.2  792.22     160 792.775   172.8  793.84
     202   796.1   220.6  797.71   229.8  798.71   239.1  799.86   276.2  804.72
   285.5  806.31   294.8  808.46   313.3  813.45   322.6  815.61
#Mann= 3 , 0 , 0
       0     .06       0     133    .045       0     160     .06       0
Bank Sta=133,160
XS Rating Curve= 0 ,0
Exp/Cntr=0.3,0.1

Type RM Length L Ch R = 1 ,47354.8 ,194.5,238,280.1
XS GIS Cut Line= 4
     1570114.701      331419.001     1570160.274      331464.574
      1570253.59      331518.828     1570510.954      331597.763
#Sta/Elev= 30
       0  809.38     9.2  804.24    18.4  800.11    27.6  797.73    36.8  797.14
    55.2  796.62    64.4  796.02    74.3  795.13    93.9  792.65     100  792.04
   103.7  791.67   113.5  791.62     122 792.245   152.8  794.75   191.6  797.39
   220.5  800.08   230.1  801.11   258.9  804.64   278.2  806.41   287.8  807.57
     307  811.18   316.6  811.99   326.2  813.12   335.8  815.27   345.4  817.71
   355.1  820.55   374.3  826.65   403.1  834.64   412.8  837.62   441.6   847.4
#Mann= 3 , 0 , 0
       0     .06       0     100    .045       0     122     .06       0
Bank Sta=100,122
XS Rating Curve= 0 ,0
Exp/Cntr=0.3,0.1

Type RM Length L Ch R = 1 ,47116.8 ,110.8,92.4,77.3
XS GIS Cut Line= 4
     1570048.512      331534.019     1570098.425      331640.356
     1570114.701      331738.012     1570251.623      331949.326
#Sta/Elev= 30
       0  797.18     9.8  795.63    19.6  795.25    68.5  795.18    88.1  794.83
   117.5  794.02   126.5  793.44   135.5  792.64     154   790.4   162.5  789.72
   171.5  789.56     181  789.84   189.5  790.69   207.5  793.14   216.5  794.06
   264.9  797.46   274.6  797.94   284.3  798.03   313.3   797.9     323  798.21
   332.7  799.66   342.4  802.43     352  805.94   361.7  808.21   381.1  808.64
   400.5  809.64   419.8  810.34   448.9  810.22   458.6  810.75   468.3  811.69
#Mann= 3 , 0 , 0
       0     .06       0     154    .045       0     181     .06       0
Bank Sta=154,181
XS Rating Curve= 0 ,0
Exp/Cntr=0.3,0.1

Type RM Length L Ch R = 1 ,47024.4 ,217.5,269.4,270.5
XS GIS Cut Line= 4
     1569935.867       331545.68     1569960.824       331627.06
     1570095.373      331835.393     1570097.543      331898.327
#Sta/Elev= 30
       0  837.97     9.5  833.56    18.9  828.98    28.4  824.24    37.8  819.29
    47.3     814    66.2  802.58    75.7  797.51    85.1  794.43    94.7  793.21
   104.2  792.98   132.8  792.82   151.9  792.28     171  791.32   199.6  789.31
     207 788.889   209.1  788.77   218.7  788.75   228.2   789.2     236 789.955
   256.8  792.18   285.4  794.92   304.5   796.4   333.1   798.3   351.1  799.18
   360.1  800.02   369.1  801.75   378.1  804.53   387.1  807.79   396.1  810.82
#Mann= 3 , 0 , 0
       0     .07       0     207    .045       0     236     .06       0
Bank Sta=207,236
XS Rating Curve= 0 ,0
Exp/Cntr=0.3,0.1

Type RM Length L Ch R = 1 ,46755   ,292.7,279.6,262.9
XS GIS Cut Line= 3
     1569795.893      331615.124      1569938.92      331880.156
     1569971.472      331966.962
#Sta/Elev= 30
       0  821.14     9.7  821.34    38.9  821.01    48.6  821.02    58.3  819.66
      68  816.38    77.7  810.76   106.9     791     112 788.808   116.6  786.83
   126.3  785.77     136   786.7     143 788.244   155.4  791.26   165.2  793.09
   174.9  794.15   184.6  794.72   194.3  795.13   213.7  795.41   233.2  794.95
   262.3  792.78     272   792.4   281.7   792.5   291.4  793.15   301.2  794.09
     329  797.19   338.2  798.41   347.5  800.22   356.8  802.72   393.9   814.3
#Mann= 3 , 0 , 0
       0      .1       0     112    .045       0     143     .06       0
Bank Sta=112,143
XS Rating Curve= 0 ,0
Exp/Cntr=0.3,0.1

Type RM Length L Ch R = 1 ,46475.4 ,187.9,214.5,238.5
XS GIS Cut Line= 4
     1569570.199      331729.056     1569615.808      331881.115
     1569733.842      331989.748      1569857.54      332061.363
#Sta/Elev= 30
       0  879.72     9.3   874.9    37.4  860.76    46.7  855.92      56  850.62
    74.7  839.35      84  834.26    93.4   829.5   102.7  824.91   112.1  820.42
   121.4  816.02   130.7  811.78   149.4  803.81   158.8  800.07   168.2  795.66
   177.6  790.77   187.1  786.13   196.5  783.48   205.9  783.36   215.4   784.3
   234.2   786.9   243.7  788.01   253.1  788.97     272  790.66   309.7  793.43
   404.9  799.61   433.5  801.83     443  802.71   452.6  804.06   462.1  806.51
#Mann= 3 , 0 , 0
       0      .1       0   187.1    .045       0   215.4     .08       0
Bank Sta=187.1,215.4
XS Rating Curve= 0 ,0
Exp/Cntr=0.3,0.1