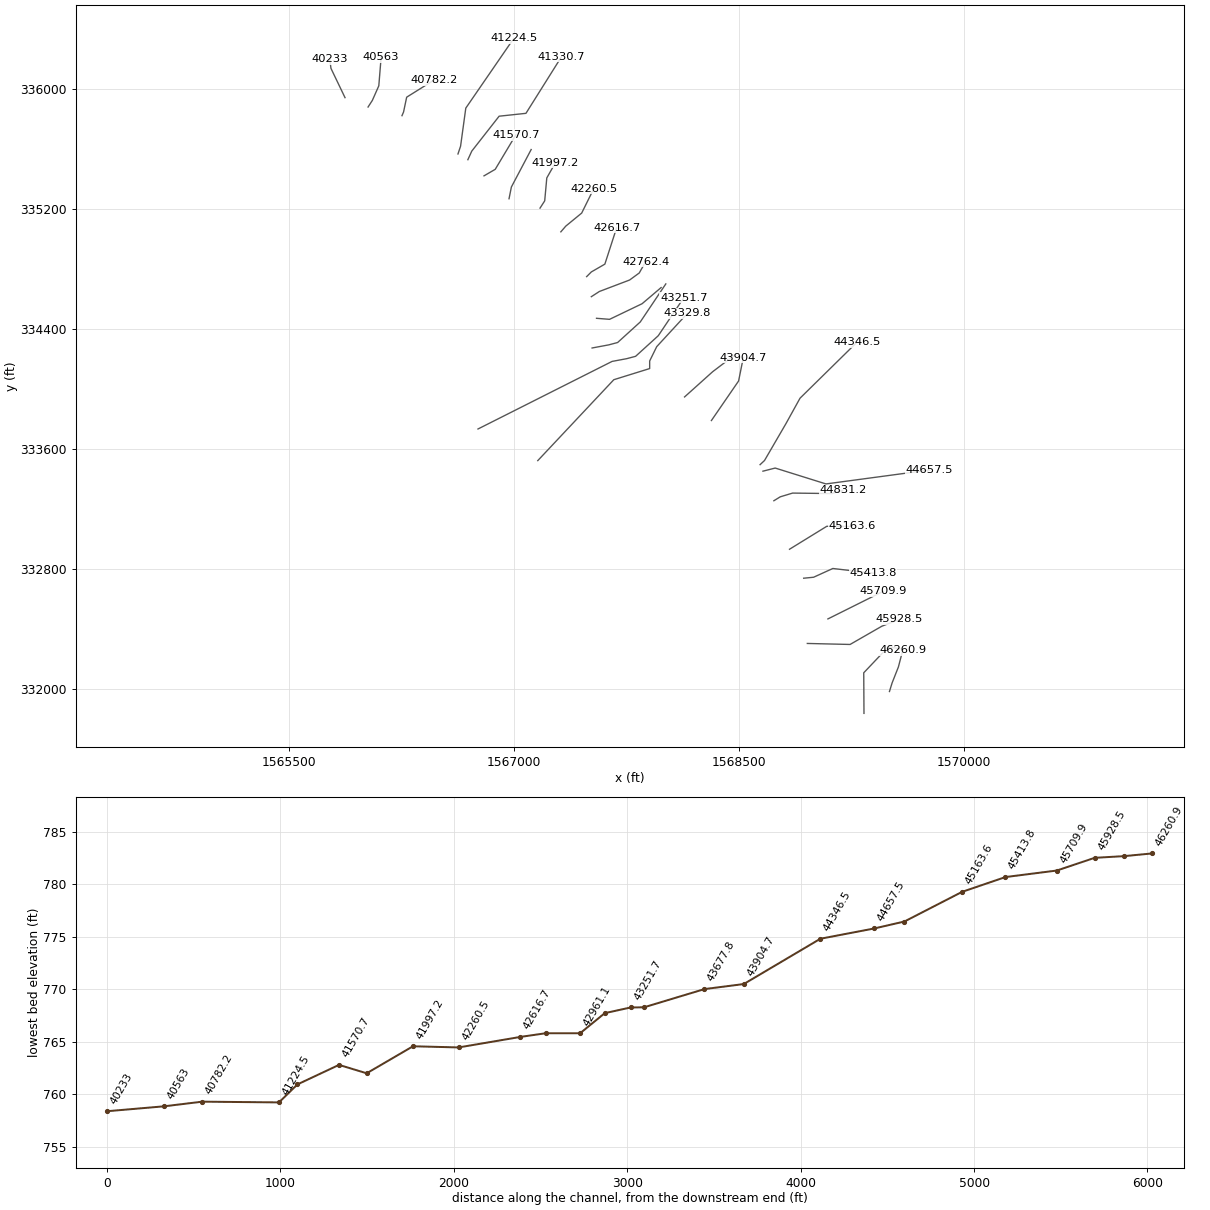
HEC-RAS study SNCHOCRK.prj: SNCHOCRK

--- SNCHOCRK.g02 (geometry) --- (continued)

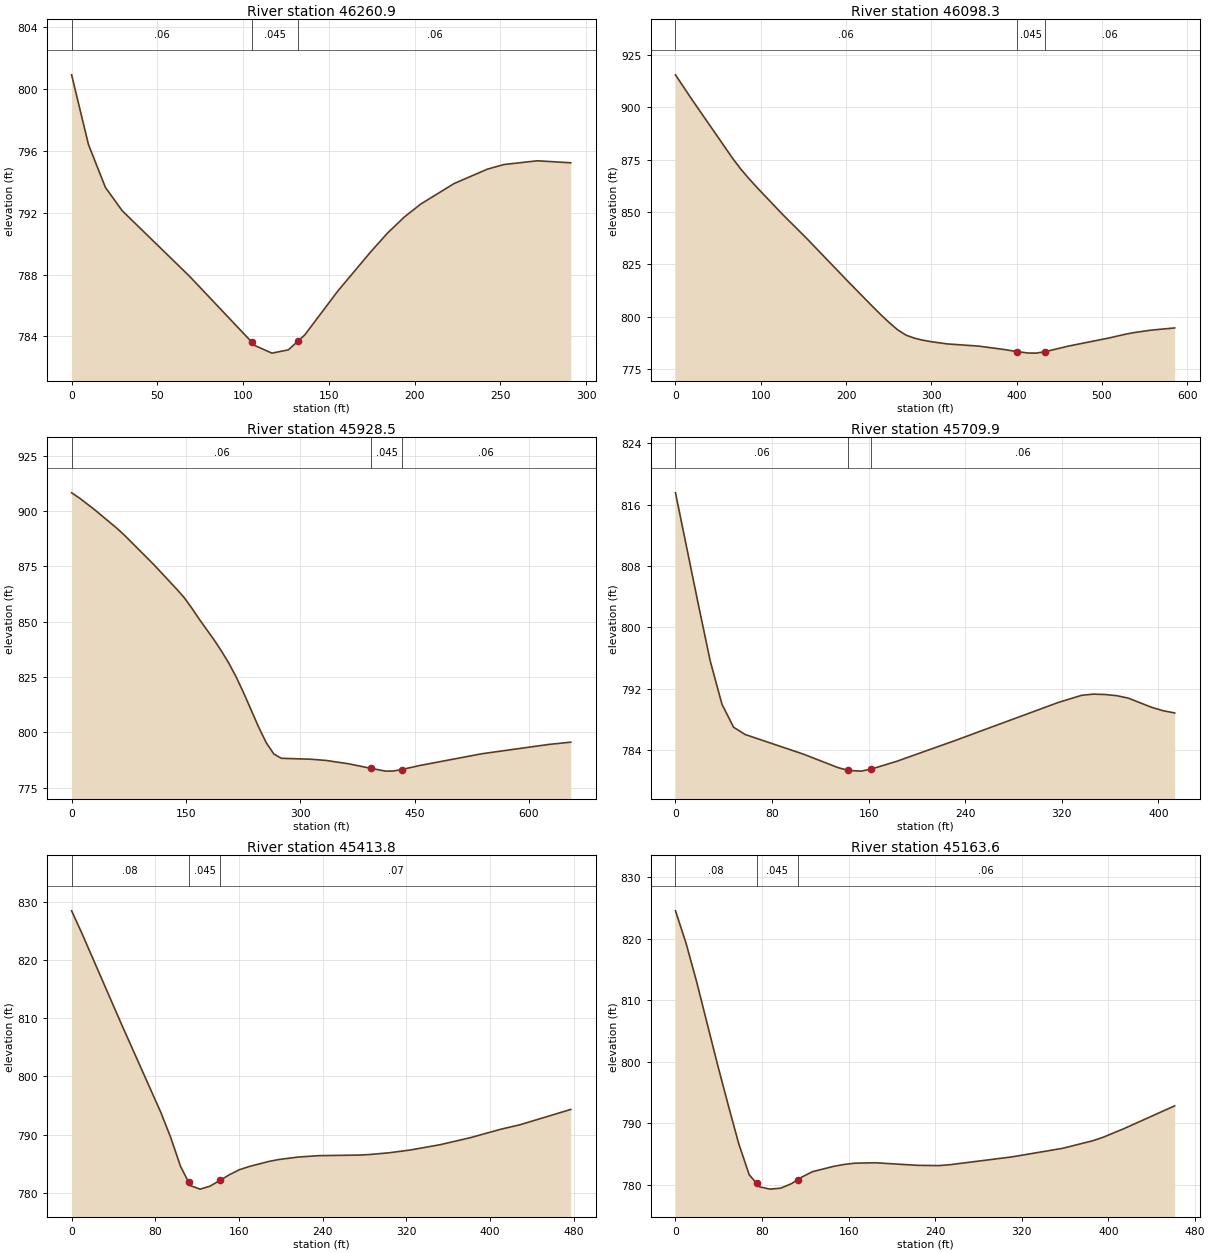
Type RM Length L Ch R = 1 ,46260.9 ,189.4,162.7,142.3
XS GIS Cut Line= 4
     1569502.722      331984.323     1569520.083      332040.746
     1569562.401      332148.168     1569591.698      332261.015
#Sta/Elev= 21
       0  800.92     9.8  796.42    19.7  793.64    29.5  792.13    68.7   787.9
     105 783.641   107.1   783.4   116.8  782.92   126.4  783.13     132 783.696
     136   784.1   155.2  786.93   174.5  789.48   184.2  790.68   193.9  791.71
   203.6  792.56   223.1  793.89   242.5  794.82   252.2  795.12   271.6  795.36
   291.1  795.23
#Mann= 3 , 0 , 0
       0     .06       0     105    .045       0     132     .06       0
Bank Sta=105,132
XS Rating Curve= 0 ,0
Exp/Cntr=0.3,0.1

Type RM Length L Ch R = 1 ,46098.3 ,183.6,169.8,154.8
XS GIS Cut Line= 4
     1569332.865      331838.525     1569331.281      332109.106
     1569495.127      332281.632     1569571.082      332269.696
#Sta/Elev= 30
       0  915.48    19.3  903.68    67.6  875.29    77.3  870.13      87  865.56
    96.6  861.28   125.6  848.87   154.6   837.1   202.9  816.64   231.9  804.61
   241.6   800.7   251.3  796.99   260.9  793.69   270.6   791.2   280.1  789.82
   289.6  788.88   299.1  788.17   318.2  787.08   356.2  785.98   385.5  784.38
     400 783.426   413.3  782.72   422.9  782.66     433 783.293   460.9  786.02
   508.5  789.89   527.7  791.68   537.4  792.44   556.6  793.57   585.4  794.69
#Mann= 3 , 0 , 0
       0     .06       0     400    .045       0     433     .06       0
Bank Sta=400,433
XS Rating Curve= 0 ,0
Exp/Cntr=0.3,0.1

Type RM Length L Ch R = 1 ,45928.5 ,221.8,218.6,215.3
XS GIS Cut Line= 4
     1568955.261      332304.671     1569240.135      332297.908
     1569451.724      332419.435     1569568.911      332465.008
#Sta/Elev= 30
       0  908.24     9.8     906    29.5  900.81      59  892.34    68.8  889.26
   108.1  875.71   137.6  864.81   147.4  861.02   157.2  856.37     167  851.36
   186.7  841.88   196.5  836.77   206.4  831.18   216.2   824.8     226  817.58
   245.6  802.17   255.5   795.2   265.3  790.22   275.1   788.3   314.2  787.87
   333.8  787.32     363  785.84     393 783.725   411.8   782.5   421.6  782.53
     433 783.217   457.2  785.08   538.6  790.38   625.7  794.55   654.7  795.59
#Mann= 3 , 0 , 0
       0     .06       0     393    .045       0     433     .06       0
Bank Sta=393,433
XS Rating Curve= 0 ,0
Exp/Cntr=0.3,0.1

Type RM Length L Ch R = 1 ,45709.9 ,297.8,296.1,294.2
XS GIS Cut Line= 2
     1569092.566      332468.264     1569462.575      332652.725
#Sta/Elev= 22
       0  817.54    19.2  802.79    28.8  795.62    38.5     790    48.1  787.01
    57.7  786.06   105.8  783.51   134.6  781.75     143 781.383   153.8  781.29
     162 781.555   182.9  782.55   230.8  785.23   317.3  790.25   336.5  791.17
   346.1  791.32   355.8  791.27   365.4  791.12     375   790.8   394.2  789.61
   403.8  789.16   413.4  788.87
#Mann= 3 , 0 , 0
       0     .06       0     143    .045       0     162     .06       0
Bank Sta=143,162
XS Rating Curve= 0 ,0
Exp/Cntr=0.3,0.1

Type RM Length L Ch R = 1 ,45413.8 ,243.9,250.2,256.4
XS GIS Cut Line= 4
     1568930.891      332739.531      1568997.08      332746.041
     1569125.321       332804.36     1569393.333      332772.893
#Sta/Elev= 27
       0  828.41     9.5  824.69    47.5  809.03    85.3  793.83    94.7  789.55
   104.1  784.59     112 781.808   113.5  781.28   122.9  780.67   132.2  781.17
     142 782.183     151  783.16   160.4     784   169.8  784.55   188.6  785.42
     198  785.75     217  786.18   236.3  786.41   274.8  786.51   284.5   786.6
   303.8  786.91     323  787.36     352  788.28   380.9  789.48   409.8  790.92
     429  791.73   477.2  794.34
#Mann= 3 , 0 , 0
       0     .08       0     112    .045       0     142     .07       0
Bank Sta=112,142
XS Rating Curve= 0 ,0
Exp/Cntr=0.3,0.1

Type RM Length L Ch R = 1 ,45163.6 ,336.6,332.4,319.2
XS GIS Cut Line= 3
      1568836.49      332932.673      1569084.97      333085.668
     1569254.241      333084.583
#Sta/Elev= 28
       0  824.55     9.7  819.32    19.4  813.09    38.9  799.49    48.6  793.01
    58.4  786.67    68.1   781.6      75 780.192    77.8  779.62    87.5  779.26
    97.3  779.42     107  780.14     113 780.808   116.7  781.22   126.4  782.09
   145.9  782.96   155.6  783.27   165.4  783.48   184.8  783.55   223.7  783.13
   243.2  783.09   252.9  783.22   310.6   784.5   357.6   785.9   385.8  787.15
   395.2  787.71   414.1  789.09   461.1  792.81
#Mann= 3 , 0 , 0
       0     .08       0      75    .045       0     113     .06       0
Bank Sta=75,113
XS Rating Curve= 0 ,0
Exp/Cntr=0.3,0.1

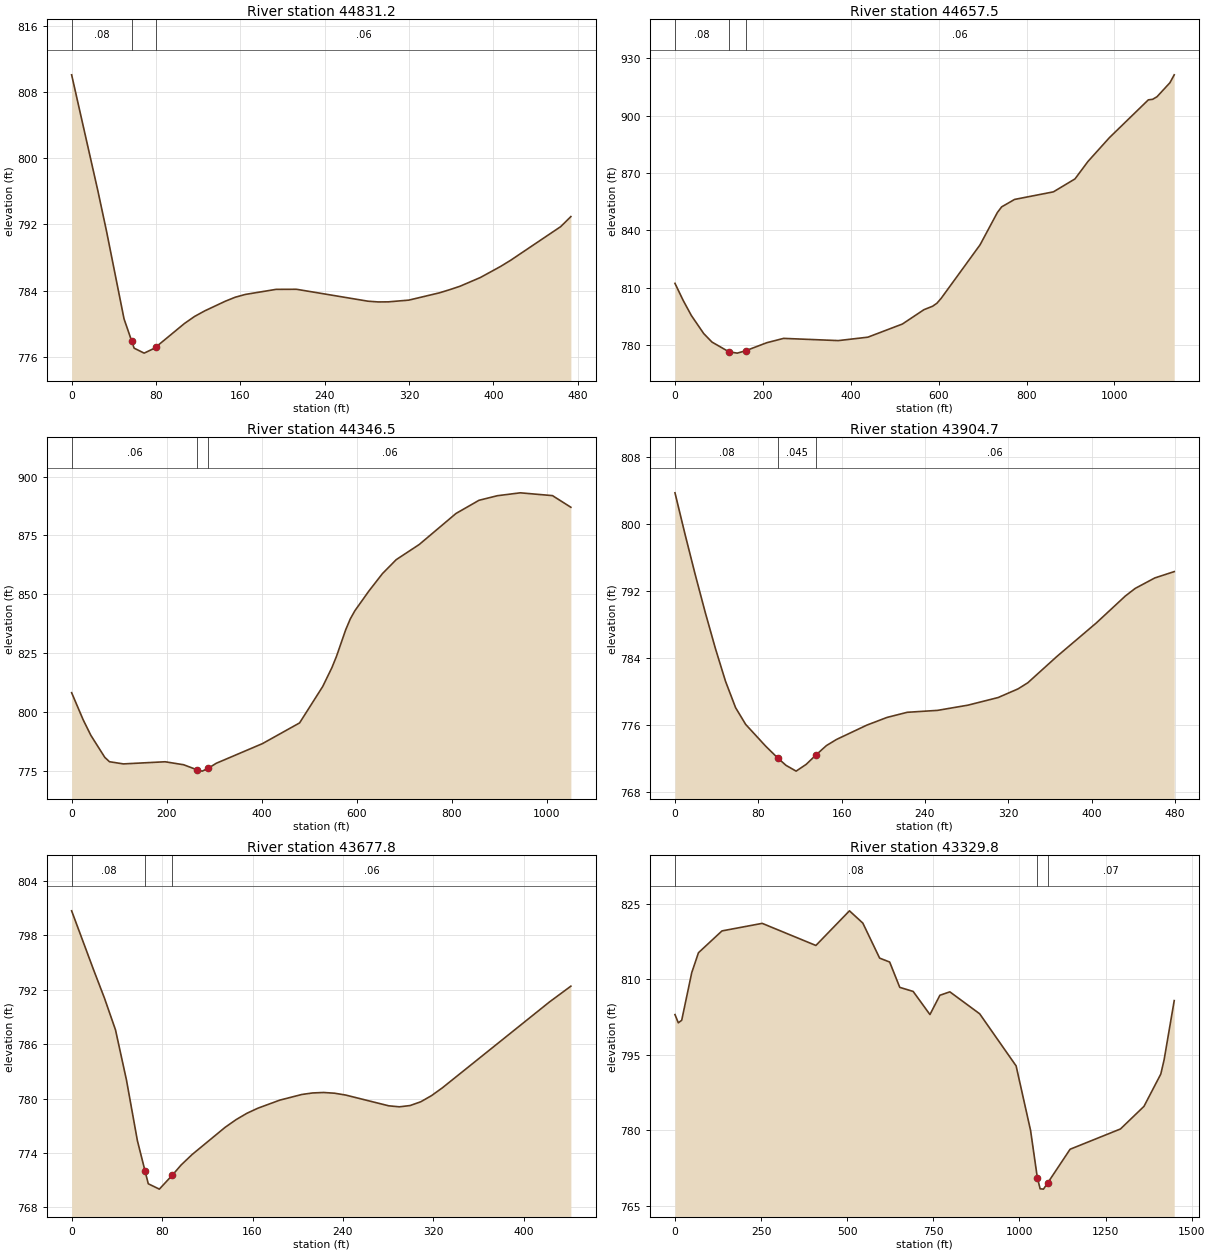
Type RM Length L Ch R = 1 ,44831.2 ,212.3,173.7,143.6
XS GIS Cut Line= 5
     1568732.323      333256.024     1568774.641      333282.066
     1568857.106      333307.022     1569118.608      333303.767
     1569191.307      333326.554
#Sta/Elev= 29
       0  810.09    24.8  796.12    33.1  791.19    49.7  780.59      57 777.891
    59.3  777.04    68.8  776.44    78.4  777.02      80 777.183   107.1  780.03
   116.7  780.88   126.3  781.55   145.5   782.7   155.2   783.2   164.9  783.54
     194  784.15   213.3  784.16   281.1  782.72   290.8  782.63   300.5  782.64
   319.9  782.85   348.9  783.73   358.6  784.11   368.3  784.52   387.7  785.58
   406.9  786.92   416.4  787.66     464  791.74   473.6  792.95
#Mann= 3 , 0 , 0
       0     .08       0      57    .045       0      80     .06       0
Bank Sta=57,80
XS Rating Curve= 0 ,0
Exp/Cntr=0.3,0.1

Type RM Length L Ch R = 1 ,44657.5 ,238,311,380
XS GIS Cut Line= 4
     1568659.406      333453.073     1568741.003      333473.906
     1569079.545      333368.003     1569770.365      333460.921
#Sta/Elev= 30
       0  812.26    18.7  803.32    37.4   795.4    65.5  785.98    84.2  781.56
   122.6  776.49   141.7  775.78   160.9  777.02   208.8  781.22   247.2  783.49
   371.8  782.33   438.9  784.12   517.5     791   566.6  798.51   586.2   800.3
     596  801.86   605.8  804.46   694.2  832.41   733.5  849.27   743.3  852.25
   772.7  856.14   861.1  860.11   910.2  866.88   939.6  875.96   988.7  888.49
  1077.1  908.21  1086.9   908.5  1096.7  909.82  1126.2  917.16    1136   921.3
#Mann= 3 , 0 , 0
       0     .08       0   122.6    .045       0   160.9     .06       0
Bank Sta=122.6,160.9
XS Rating Curve= 0 ,0
Exp/Cntr=0.3,0.1

Type RM Length L Ch R = 1 ,44346.5 ,447.7,441.8,435.6
XS GIS Cut Line= 5
     1568640.309      333496.475     1568669.823      333524.253
     1568812.184      333769.045     1568906.614      333939.628
      1569285.99      334312.484
#Sta/Elev= 30
       0  808.15    24.3  796.63    40.5  790.01    69.8  780.66    79.6   778.8
   108.9  777.87   196.8  778.78   235.8  777.51     264 775.357   274.9   774.8
     287 775.953   304.2  778.12   401.7  786.51   479.7   795.3   528.4  810.79
   547.7   818.8   557.4  823.62   576.7  834.88   586.4  839.52     596  842.98
   625.1  851.26   654.1  858.79   683.1  864.73   731.4  871.15   808.8  884.35
   857.2  889.96   895.9  891.91   944.2  893.14  1011.9  891.95  1050.6     887
#Mann= 3 , 0 , 0
       0     .06       0     264    .045       0     287     .06       0
Bank Sta=264,287
XS Rating Curve= 0 ,0
Exp/Cntr=0.3,0.1

Type RM Length L Ch R = 1 ,43904.7 ,236.4,226.8,217
XS GIS Cut Line= 3
     1568315.859      333790.688     1568497.065       334054.36
     1568528.532       334210.61
#Sta/Elev= 30
       0   803.7     9.7  798.73    19.4  793.96    29.1  789.41    38.8  785.13
    48.5  781.22    58.2  778.06    67.9  776.06    87.3  773.44      99 772.019
   106.6  771.18   116.3  770.49     126   771.3     135 772.376   145.4  773.54
   155.1  774.27   184.2  775.98   203.6   776.9     223  777.51   252.1  777.74
   281.2  778.36   310.2  779.27   329.3   780.3   338.7  781.03   366.8  784.19
   404.3  788.15   432.4  791.39   441.8  792.29   460.6  793.54   479.3   794.3
#Mann= 3 , 0 , 0
       0     .08       0      99    .045       0     135     .06       0
Bank Sta=99,135
XS Rating Curve= 0 ,0
Exp/Cntr=0.3,0.1

Type RM Length L Ch R = 1 ,43677.8 ,312.4,348,367.4
XS GIS Cut Line= 3
     1568136.837      333947.864     1568324.337      334116.267
     1568475.378       334230.85
#Sta/Elev= 30
       0  800.71    19.4  794.21    29.1  791.06    38.8  787.58    48.5  782.05
    58.2  775.34      65 771.983    67.8   770.6    77.6  770.01      89  771.54
    96.9  772.68   106.6  773.83   135.7  776.82   145.4  777.67   155.1  778.38
   164.8  778.94   184.2  779.83   203.6  780.45   213.2  780.62   222.9  780.67
   232.6  780.59   242.3  780.39   280.5   779.2   289.9  779.09   299.4  779.23
   308.9  779.65   318.4  780.33   327.9  781.18   422.6  790.65   441.6   792.4
#Mann= 3 , 0 , 0
       0     .08       0      65    .045       0      89     .06       0
Bank Sta=65,89
XS Rating Curve= 0 ,0
Exp/Cntr=0.3,0.1

Type RM Length L Ch R = 1 ,43329.8 ,113.3,78.2,59
XS GIS Cut Line= 6
     1567158.386      333523.421     1567665.278      334062.842
     1567904.198        334137.1     1567904.198      334187.448
     1567951.073      334282.934     1568155.934      334505.156
#Sta/Elev= 30
       0  802.94     9.7  801.31    19.5  801.81    48.7  811.28    68.2  815.23
   136.4  819.56   253.2  821.06   409.1  816.67   506.5  823.55   545.4  821.11
   594.1  814.16   623.3  813.38   652.6  808.35   691.5  807.54   740.2  802.95
   769.1  806.78     798  807.46   884.6   803.1   990.4  792.75  1032.4  779.92
    1052 770.555  1060.1  768.35  1069.8  768.28    1082 769.504  1147.1   776.2
  1293.4  780.23  1361.6  784.72  1410.4  791.13  1420.1  793.99  1449.4  805.72
#Mann= 3 , 0 , 0
       0     .08       0    1052    .045       0    1082     .07       0
Bank Sta=1052,1082
XS Rating Curve= 0 ,0
Exp/Cntr=0.3,0.1

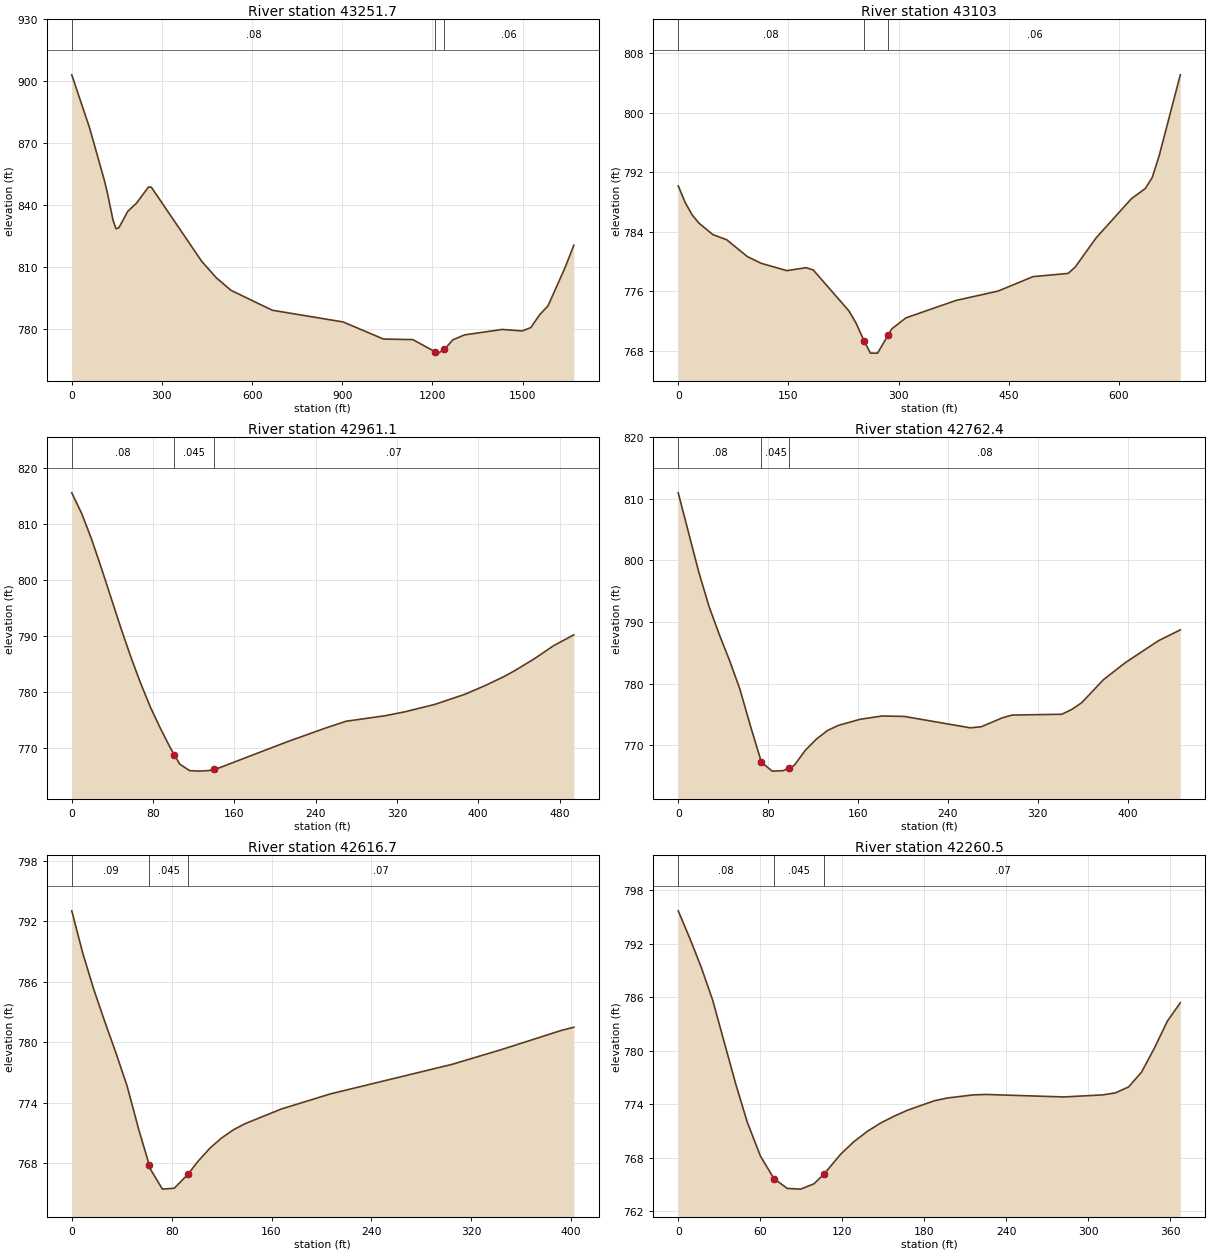
Type RM Length L Ch R = 1 ,43251.7 ,148.7,148.7,148.7
XS GIS Cut Line= 6
     1566759.949      333734.359     1567653.691      334184.748
      1567751.42      334203.073     1567810.448      334218.698
      1567961.49       334355.85     1568131.628      334609.323
#Sta/Elev= 30
       0  903.05    58.9  877.55   107.9  852.24   117.7  846.47   137.4  832.59
   147.2   828.5     157  829.03   186.4  836.95   215.9  840.98   255.1   848.7
   264.9   848.6   431.7  812.86   480.8  804.77   529.8  798.68   667.2  789.03
   902.7  783.37    1037  775.09  1135.1   774.8    1210 768.814  1219.6  768.26
    1240 770.123  1268.2  774.72    1307  777.09  1432.1  779.73  1498.9  779.02
  1527.5  780.62  1556.1  786.72  1584.8  791.19    1642  809.89  1670.6  820.54
#Mann= 3 , 0 , 0
       0     .08       0    1210    .045       0    1240     .06       0
Bank Sta=1210,1240
XS Rating Curve= 0 ,0
Exp/Cntr=0.3,0.1

Type RM Length L Ch R = 1 ,43103   ,170.2,141.9,127.1
XS GIS Cut Line= 5
     1567520.517      334274.253     1567631.628      334295.087
     1567690.656      334310.712     1567841.698      334447.864
     1568011.837      334701.337
#Sta/Elev= 30
       0  790.17     9.4  787.95    18.8  786.29    28.3  785.16    47.1  783.63
    65.9  782.94    94.2  780.67     113  779.77   147.9  778.79   174.1  779.19
   183.8  778.88   232.4  773.38   242.1  771.74     253 769.361   261.6  767.72
   271.3  767.72     286 770.181   290.7  770.98   310.1  772.46   378.1  774.79
   435.4  776.05   483.1  777.99   530.8  778.42   540.3  779.27   568.9   783.2
   616.6  788.42   635.7  789.81   645.2  791.29   654.8  794.28   683.4  805.07
#Mann= 3 , 0 , 0
       0     .08       0     253    .045       0     286     .06       0
Bank Sta=253,286
XS Rating Curve= 0 ,0
Exp/Cntr=0.3,0.1

Type RM Length L Ch R = 1 ,42961.1 ,182.1,198.7,194.5
XS GIS Cut Line= 4
     1567550.031       334472.17     1567636.837      334465.225
     1567853.851      334569.392     1567980.587      334677.031
#Sta/Elev= 30
       0  815.58     9.7  811.91    19.4  807.34      29   802.2    48.4  791.37
    58.1  786.24    67.7  781.56    77.4  777.25    87.1  773.51    96.7  770.07
     101 768.722   106.3  767.06     116   765.9   125.6  765.81   135.2  765.92
     140 766.148   144.9  766.38   212.3  771.08   250.8  773.58     270  774.73
   308.5  775.72   327.8  776.42   357.2  777.74   386.5  779.53     406  781.04
   425.6  782.74   435.4  783.72     455  785.88   474.5  788.28   494.1  790.19
#Mann= 3 , 0 , 0
       0     .08       0     101    .045       0     140     .07       0
Bank Sta=101,140
XS Rating Curve= 0 ,0
Exp/Cntr=0.3,0.1

Type RM Length L Ch R = 1 ,42762.4 ,138.6,145.7,153.8
XS GIS Cut Line= 5
     1567515.309      334616.267     1567569.128      334650.989
     1567770.517      334727.378     1567834.753      334774.253
     1567878.156      334850.642
#Sta/Elev= 30
       0  810.98    18.3  798.11    27.4  792.54    36.6  787.95    45.8  783.71
    54.9   779.1      64  773.31      74  767.27    83.6  765.81    93.4  765.88
      99 766.366   103.2  766.73     113  769.17   122.8  770.98   132.6  772.38
   142.4  773.23     162  774.23   181.5  774.76   201.1  774.69   259.9  772.84
   269.6  773.01   288.3  774.45   297.1  774.91   341.3  775.04   350.1  775.81
     359  776.91   378.5  780.67     398  783.43   427.3  786.97   446.8  788.74
#Mann= 3 , 0 , 0
       0     .08       0      74    .045       0      99     .08       0
Bank Sta=74,99
XS Rating Curve= 0 ,0
Exp/Cntr=0.3,0.1

Type RM Length L Ch R = 1 ,42616.7 ,350.2,356.3,364.5
XS GIS Cut Line= 4
     1567484.059      334749.948     1567515.309      334781.198
     1567605.587      334833.281     1567683.712        335074.6
#Sta/Elev= 23
       0  793.03     8.8  788.84    17.7  785.22    26.5  782.04    35.4  778.94
    44.2  775.72    53.7  771.34      62 767.879    63.1  767.42    72.6  765.46
    82.1  765.55      93 766.924     101   768.2   110.5   769.5     120  770.53
   129.5  771.34   138.9  771.95   167.9   773.4     207  774.89   304.5  777.82
   343.5  779.26   392.3  781.19   402.1   781.5
#Mann= 3 , 0 , 0
       0     .09       0      62    .045       0      93     .07       0
Bank Sta=62,93
XS Rating Curve= 0 ,0
Exp/Cntr=0.3,0.1

Type RM Length L Ch R = 1 ,42260.5 ,234.4,263.3,303.7
XS GIS Cut Line= 4
     1567312.184      335048.559      1567345.17      335086.753
     1567451.073      335173.559     1567530.934      335335.017
#Sta/Elev= 30
       0  795.68     8.4  792.62    16.8  789.37    25.2  785.66    42.1  776.25
    50.5  771.99    60.2  768.16      70  765.65    79.8  764.54    89.6  764.46
    99.4  765.06     107   766.2   118.9  768.38   128.7   769.8   138.5  770.95
   148.3  771.89   158.1  772.65   167.8  773.31   187.4  774.37   196.9  774.68
   215.8  775.03   225.3  775.08   282.2   774.8   310.6  775.03   320.1  775.26
   329.6  775.92   339.1  777.58   348.6   780.3     358   783.3   367.5  785.37
#Mann= 3 , 0 , 0
       0     .08       0      70    .045       0     107     .07       0
Bank Sta=70,107
XS Rating Curve= 0 ,0
Exp/Cntr=0.3,0.1

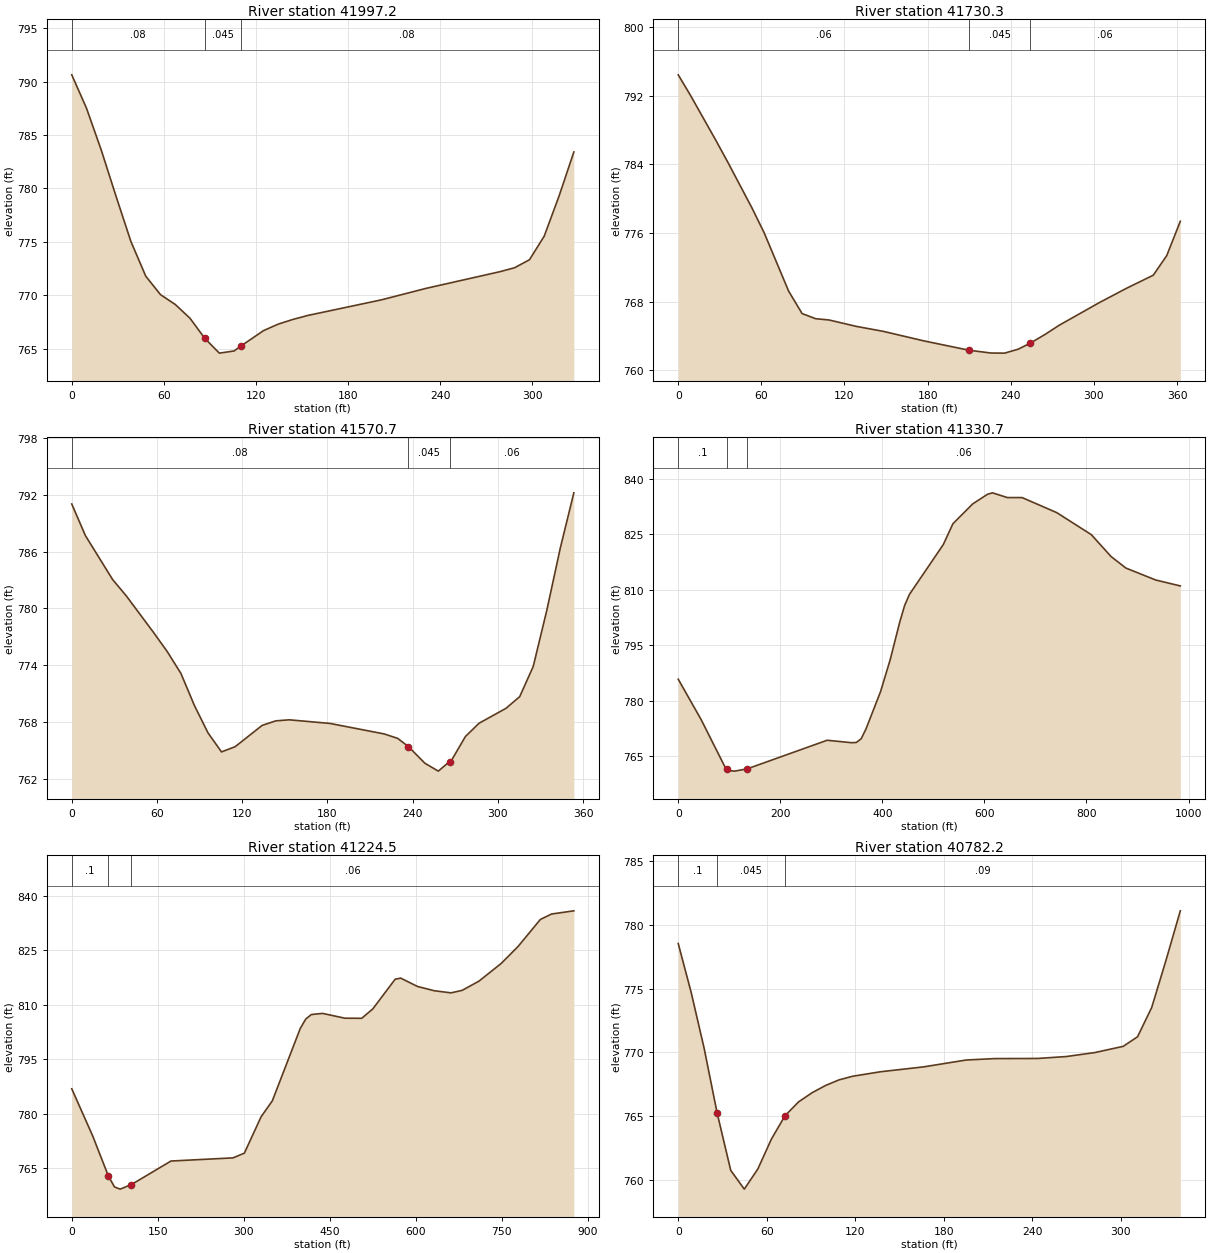
Type RM Length L Ch R = 1 ,41997.2 ,271,266.9,250.6
XS GIS Cut Line= 4
     1567173.295      335206.545     1567204.545      335255.156
     1567218.434      335407.934     1567275.726      335508.628
#Sta/Elev= 25
       0  790.65     9.6  787.52    19.3  783.56    28.9  779.24    38.5  775.04
    48.2  771.78    57.8  770.05    67.4  769.13      77  767.84    86.6  765.96
    96.1  764.57   105.7  764.77     110 765.218   124.9  766.68   134.5  767.29
   144.1  767.73   153.7   768.1   201.6  769.56   230.5  770.63   278.8   772.2
   288.4  772.57   298.1  773.32   307.7  775.53   317.4   779.3     327  783.42
#Mann= 3 , 0 , 0
       0     .08       0    86.6    .045       0     110     .08       0
Bank Sta=86.6,110
XS Rating Curve= 0 ,0
Exp/Cntr=0.3,0.1

Type RM Length L Ch R = 1 ,41730.3 ,170.4,159.6,151.6
XS GIS Cut Line= 3
     1566966.698      335269.045     1566982.323       335347.17
     1567114.267       335597.17
#Sta/Elev= 25
       0  794.42     8.8  792.04    26.6  786.95    35.4  784.36    53.1  778.95
      62  776.03    79.7  769.22    89.4  766.61    99.2  766.01   108.9  765.86
   128.4  765.12   147.9  764.54   177.2  763.43     210 762.334   225.9  762.01
   235.6     762   245.4  762.46     254 763.152   264.9  764.19   274.9  765.24
   303.9  767.88   323.4  769.54   342.9  771.08   352.6  773.36   362.4  777.36
#Mann= 3 , 0 , 0
       0     .06       0     210    .045       0     254     .06       0
Bank Sta=210,254
XS Rating Curve= 0 ,0
Exp/Cntr=0.3,0.1

Type RM Length L Ch R = 1 ,41570.7 ,244.7,240,223.2
XS GIS Cut Line= 3
     1566800.031      335421.823     1566874.684      335465.225
     1567011.837      335694.392
#Sta/Elev= 30
       0  791.02     9.6  787.68    28.8  783.03    38.4  781.31    57.6  777.44
    67.2  775.43    76.8  773.13    86.4  769.71    95.9  766.84   105.4  764.83
     115  765.38     134  767.63   143.6  768.11   153.1  768.22   181.7  767.84
   219.9  766.73   229.4  766.26     237 765.389   248.5  763.64     258   762.8
     266 763.817   267.6  764.02   277.1  766.46   286.7  767.86   305.7  769.44
   315.3  770.67   324.8  773.85   334.4  779.81   343.9  786.39   353.4   792.2
#Mann= 3 , 0 , 0
       0     .08       0     237    .045       0     266     .06       0
Bank Sta=237,266
XS Rating Curve= 0 ,0
Exp/Cntr=0.3,0.1

Type RM Length L Ch R = 1 ,41330.7 ,83.6,106.2,132.8
XS GIS Cut Line= 5
     1566692.392      335529.462     1566718.434      335586.753
     1566900.726      335819.392     1567079.545      335838.489
      1567316.51      336215.819
#Sta/Elev= 30
       0   785.8      45  774.85    91.5   762.1      96 761.617   101.1  761.07
   110.6  760.94     135 761.548   291.8  769.29   339.4  768.63     349  768.69
   358.5  769.69     368  772.36   396.4  782.42   415.3  791.04   434.2  801.31
   443.7  805.75   453.1  808.74   519.4  822.21   538.3  827.85   577.1  833.22
   606.1  835.82   615.8  836.21   644.9  834.93   673.9  834.92   741.7  830.86
   809.5   824.9   848.3  818.97   877.3  815.86   935.5  812.64   983.9  811.03
#Mann= 3 , 0 , 0
       0      .1       0      96    .045       0     135     .06       0
Bank Sta=96,135
XS Rating Curve= 0 ,0
Exp/Cntr=0.3,0.1

Type RM Length L Ch R = 1 ,41224.5 ,41169.1,442.4,438.9
XS GIS Cut Line= 4
      1566626.42      335567.656     1566643.781      335619.739
     1566678.503      335873.212     1566998.584      336338.431
#Sta/Elev= 30
       0  786.87    36.6  773.84      64 762.779    74.6  759.82    84.4  759.23
   104.1   760.5     173  766.97   281.2  767.84   300.9  769.14   330.2  779.18
   349.7  783.56   398.4  803.49   408.1  806.12   417.8  807.33   437.3  807.64
   476.2  806.32   505.5  806.29   524.9  808.88   563.9  817.07   573.6  817.36
   602.8  815.06     632  813.89   661.2   813.3   680.7  813.99   709.9  816.52
   748.9  821.43   778.1  826.07     817  833.52   836.5  835.02   875.4   835.9
#Mann= 3 , 0 , 0
       0      .1       0      64    .045       0   104.1     .06       0
Bank Sta=64,104.1
XS Rating Curve= 0 ,0
Exp/Cntr=0.3,0.1

Type RM Length L Ch R = 1 ,40782.2 ,11618.2,219.1,208.3
XS GIS Cut Line= 4
     1566253.156      335822.864     1566263.573       335847.17
     1566284.406      335946.128     1566464.962      336058.975
#Sta/Elev= 26
       0  778.53     8.8  774.69    17.6  770.31    26.4  765.25    35.6  760.77
    44.8   759.3      54  760.88    63.2  763.22    72.4  765.04    81.6  766.13
    90.8  766.85     100  767.42   109.2  767.86   118.4  768.14   137.2  768.49
   166.3  768.87   195.3  769.41   214.7  769.52   243.7  769.53   263.1  769.68
   282.4  769.99   301.8  770.48   311.5  771.23   321.1  773.52   330.8  777.22
   340.5  781.09
#Mann= 3 , 0 , 0
       0      .1       0    26.4    .045       0    72.4     .09       0
Bank Sta=26.4,72.4
XS Rating Curve= 0 ,0
Exp/Cntr=0.3,0.1

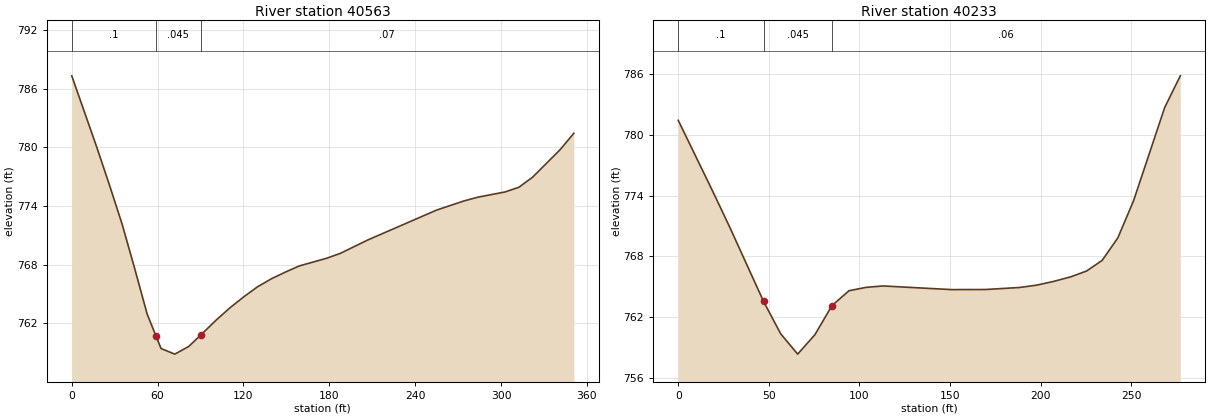
Type RM Length L Ch R = 1 ,40563   ,253,330.1,374.9
XS GIS Cut Line= 4
     1566027.028       335880.59     1566055.674      335924.861
     1566098.628      336021.953     1566114.253      336213.359
#Sta/Elev= 30
       0  787.31    17.6  779.96    26.4  776.12    32.8  773.23    35.2  772.14
    43.9  767.65    52.7  762.95      59 760.664    62.4  759.43      72  758.86
    81.7  759.64      90  760.79     101  762.35   110.6   763.6   120.3  764.73
   129.9  765.75   139.6  766.57   149.2  767.24   158.9  767.87   178.1  768.66
   187.7  769.16   206.9  770.53   254.9  773.58   274.1  774.52   283.7   774.9
   302.9  775.44   312.5  775.92   322.1  776.95   341.3  779.76   350.9  781.44
#Mann= 3 , 0 , 0
       0      .1       0      59    .045       0      90     .07       0
Bank Sta=59,90
XS Rating Curve= 0 ,0
Exp/Cntr=0.3,0.1

Type RM Length L Ch R = 1 ,40233   ,266.7,246.2,209.1
XS GIS Cut Line= 3
     1565873.382       335943.09     1565779.632      336138.403
     1565771.819      336198.298
#Sta/Elev= 23
       0   781.4    18.8   774.5    28.3  770.93    47.1  763.57    56.5   760.4
    65.9  758.39    75.4   760.3    84.8  763.16    94.2  764.63   103.6  764.96
     113   765.1   150.7  764.74   169.6  764.75   188.4  764.95   197.8  765.18
   207.2  765.55   216.6     766   225.3  766.57   233.9  767.62   242.5  769.82
   251.2  773.48   268.4  782.67     277  785.78
#Mann= 3 , 0 , 0
       0      .1       0    47.1    .045       0    84.8     .06       0
Bank Sta=47.1,84.8
XS Rating Curve= 0 ,0
Exp/Cntr=0.3,0.1