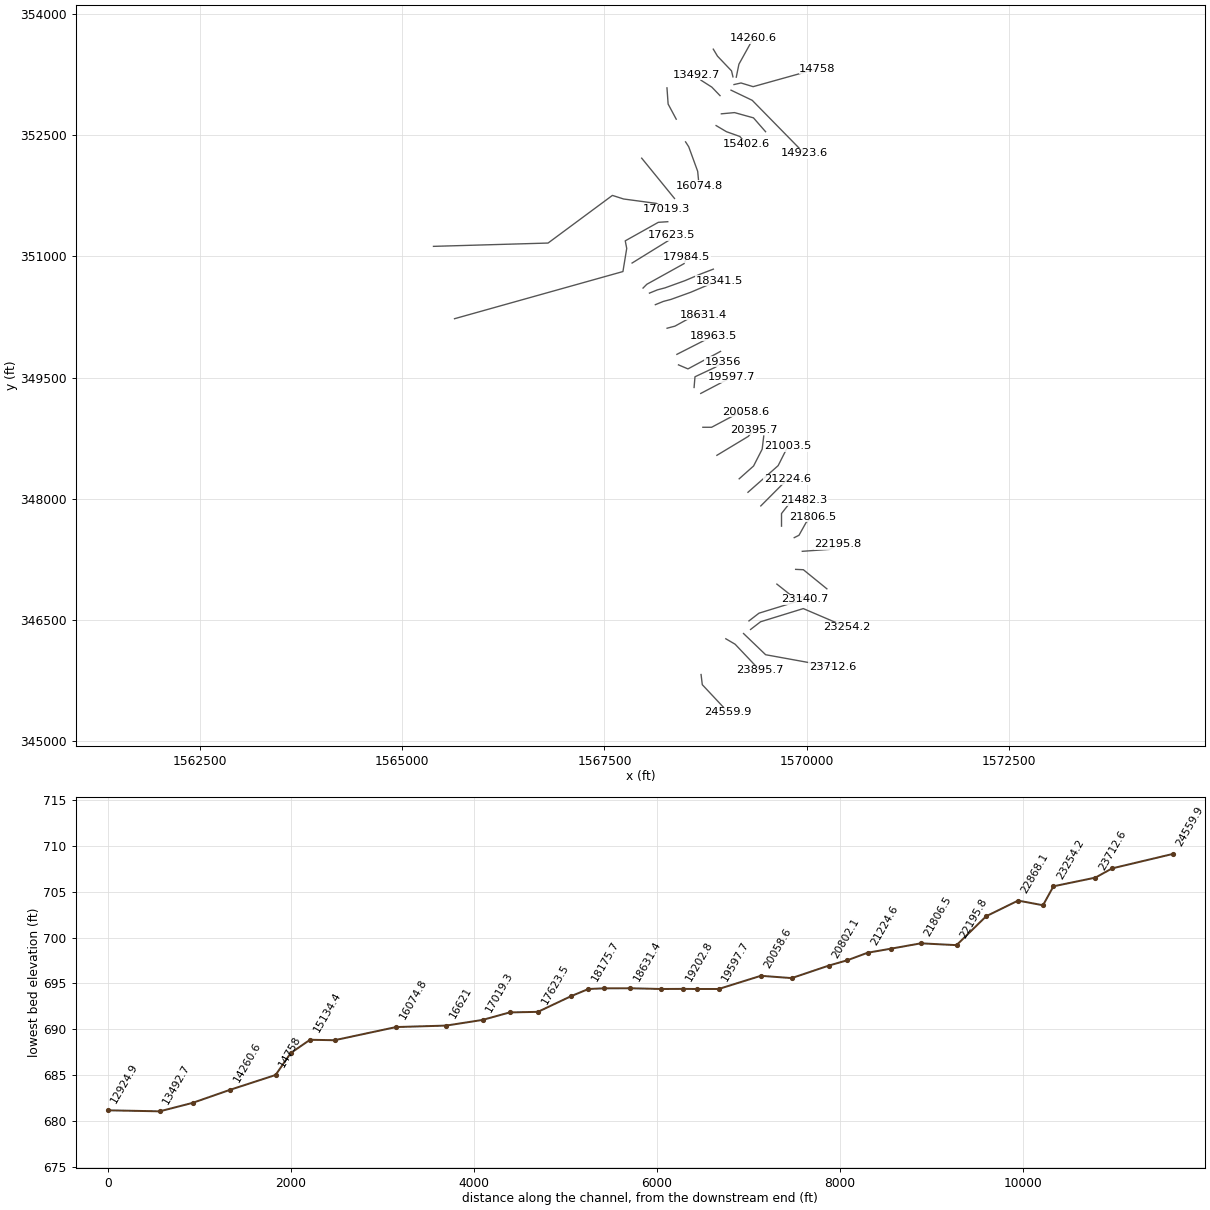
HEC-RAS study SNCHOCRK.prj: SNCHOCRK

--- SNCHOCRK.g02 (geometry) --- (continued)

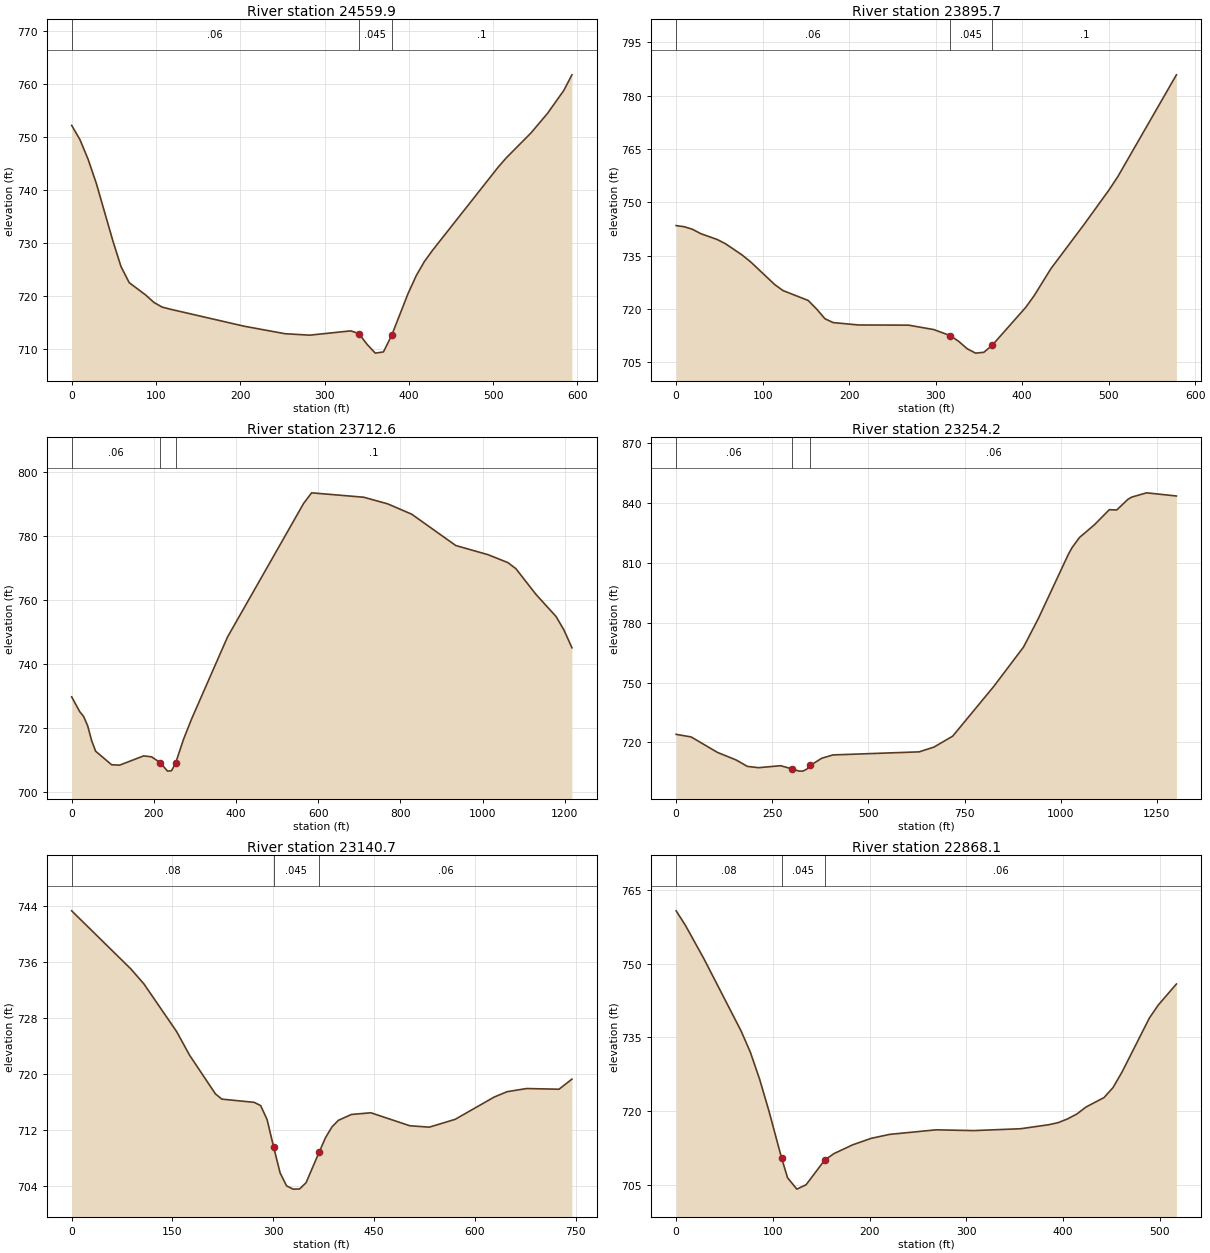
Type RM Length L Ch R = 1 ,24559.9 ,663.5,664.3,664.3
XS GIS Cut Line= 3
     1568694.562      345822.864     1568709.753      345696.996
     1569028.764      345356.284
#Sta/Elev= 30
       0  752.14     9.8  749.46    19.5  745.74    29.3  741.16    48.8  730.39
    58.5   725.5    68.3  722.45    87.8  720.13    97.5  718.74   107.3  717.85
     117  717.45   204.6  714.24   253.2  712.82   282.4  712.55     331  713.36
   340.7  712.86   350.4  710.83   360.2  709.16   369.9  709.39   379.6   712.5
     399  720.38   408.8  723.79   418.5  726.46   428.2  728.58     506  744.26
   515.7  746.03   544.9  750.71   564.4  754.38   583.8  758.72   593.5  761.68
#Mann= 3 , 0 , 0
       0     .06       0   340.7    .045       0   379.6      .1       0
Bank Sta=340.7,379.6
XS Rating Curve= 0 ,0
Exp/Cntr=0.3,0.1

Type RM Length L Ch R = 1 ,23895.7 ,180.8,183,184.8
XS GIS Cut Line= 3
     1569000.552      346265.573     1569115.569      346198.298
     1569421.559      345874.948
#Sta/Elev= 30
       0  743.45     9.5  743.13      19   742.4    28.6  741.17    47.6  739.53
    57.1  738.34    76.1  735.21    85.7  733.34   114.2  726.82   123.7  725.16
   152.6   722.4   162.3  720.02     172  717.26   181.6  716.17   210.7   715.5
   268.7  715.45   297.8  714.21   317.1  712.49   326.8  710.87   336.5  708.81
   346.2  707.58   355.8  707.82   365.5  709.81   404.2  720.46   413.9  723.73
   433.3  731.34     472  743.89     501  753.66   510.7  757.24   578.4  785.86
#Mann= 3 , 0 , 0
       0     .06       0   317.1    .045       0   365.5      .1       0
Bank Sta=317.1,365.5
XS Rating Curve= 0 ,0
Exp/Cntr=0.3,0.1

Type RM Length L Ch R = 1 ,23712.6 ,404.2,458.4,511.5
XS GIS Cut Line= 3
     1569219.736      346330.677     1569493.174       346068.09
     1570317.826       345918.35
#Sta/Elev= 30
       0  729.74    19.4  725.16    29.2  723.59    38.9  720.71    48.6  716.09
    58.3  712.78    97.2  708.56   116.6  708.43     175  711.32   194.4  711.03
   215.3  709.23   233.3  706.57     243   706.7   252.7  709.02   272.2  716.52
   291.6   722.8   379.1  748.39   564.3  790.08   583.8  793.39   710.5  792.02
   768.9  789.95   827.4  786.72   934.6  776.95  1012.6  774.11  1061.3  771.63
  1080.8  769.74  1129.5  761.73  1178.3  754.85  1197.8   750.6  1217.2  745.05
#Mann= 3 , 0 , 0
       0     .06       0   215.3    .045       0   252.7      .1       0
Bank Sta=215.3,252.7
XS Rating Curve= 0 ,0
Exp/Cntr=0.3,0.1

Type RM Length L Ch R = 1 ,23254.2 ,112,113.5,114.8
XS GIS Cut Line= 5
     1569306.542       346380.59      1569430.24      346476.076
     1569549.597      346512.968     1569958.771      346639.331
     1570502.288      346406.632
#Sta/Elev= 30
       0  724.06    39.1  722.75   107.4  715.01   156.3  711.19   185.1     708
   213.9  707.34   271.6  708.34   300.7  706.78   320.1  705.62   329.9  705.65
   339.6   706.6   349.3  708.53   378.5  712.07   407.7  713.74   631.6  715.28
   670.5  717.68   719.1  723.17   825.7  748.06   903.3  767.86     942  782.24
  1019.6  814.26  1029.3  817.65  1048.7  822.76  1087.4  829.11  1126.2   836.7
  1145.6  836.55  1174.7  841.91  1184.4  842.99  1223.1  845.15  1300.7  843.56
#Mann= 3 , 0 , 0
       0     .06       0   300.7    .045       0   349.3     .06       0
Bank Sta=300.7,349.3
XS Rating Curve= 0 ,0
Exp/Cntr=0.3,0.1

Type RM Length L Ch R = 1 ,23140.7 ,322.7,272.6,222.2
XS GIS Cut Line= 4
      1569287.01      346486.927     1569410.708      346582.413
     1569530.066      346619.305     1569972.774      346756.024
#Sta/Elev= 30
       0  743.25    87.9  734.98   107.4  732.84   156.3  726.01   175.5  722.65
   213.9  717.14   223.5  716.39   271.6  715.93   281.2  715.47   290.8  713.48
   300.5  709.58   310.2  705.86   319.8  704.02   329.5  703.55   339.1  703.57
   348.8  704.46   368.1  708.78   377.7  710.88   387.4  712.43     397  713.37
   416.3   714.2   445.3  714.44   503.2  712.59   532.2  712.39   570.8  713.51
   628.7  716.68     648  717.45     677   717.9   725.2   717.8   744.5  719.24
#Mann= 3 , 0 , 0
       0     .08       0   300.5    .045       0   368.1     .06       0
Bank Sta=300.5,368.1
XS Rating Curve= 0 ,0
Exp/Cntr=0.3,0.1

Type RM Length L Ch R = 1 ,22868.1 ,337.1,348.2,347.6
XS GIS Cut Line= 4
     1569632.062      346942.656     1569842.566      346775.555
     1569987.965      346784.236     1570081.281      346740.833
#Sta/Elev= 30
       0  760.79     9.6  757.83    28.8  750.99    67.2  736.28    76.8  731.93
    86.4  726.41      96  719.96  108.95  710.45   115.2  706.38   124.8  704.06
   134.4  704.96   153.6  709.98   163.2   711.3   182.4  713.08   201.6  714.41
   220.8  715.22   268.8  716.15   307.6  715.99   356.2  716.37   385.3  717.19
     395  717.61   404.7  718.37   414.4  719.38   423.8  720.79   442.5  722.73
   451.8  724.77   461.2  727.98   489.3  738.92   498.6   741.6   517.3  745.87
#Mann= 3 , 0 , 0
       0     .08       0  108.95    .045       0   153.6     .06       0
Bank Sta=108.95,153.6
XS Rating Curve= 0 ,0
Exp/Cntr=0.3,0.1

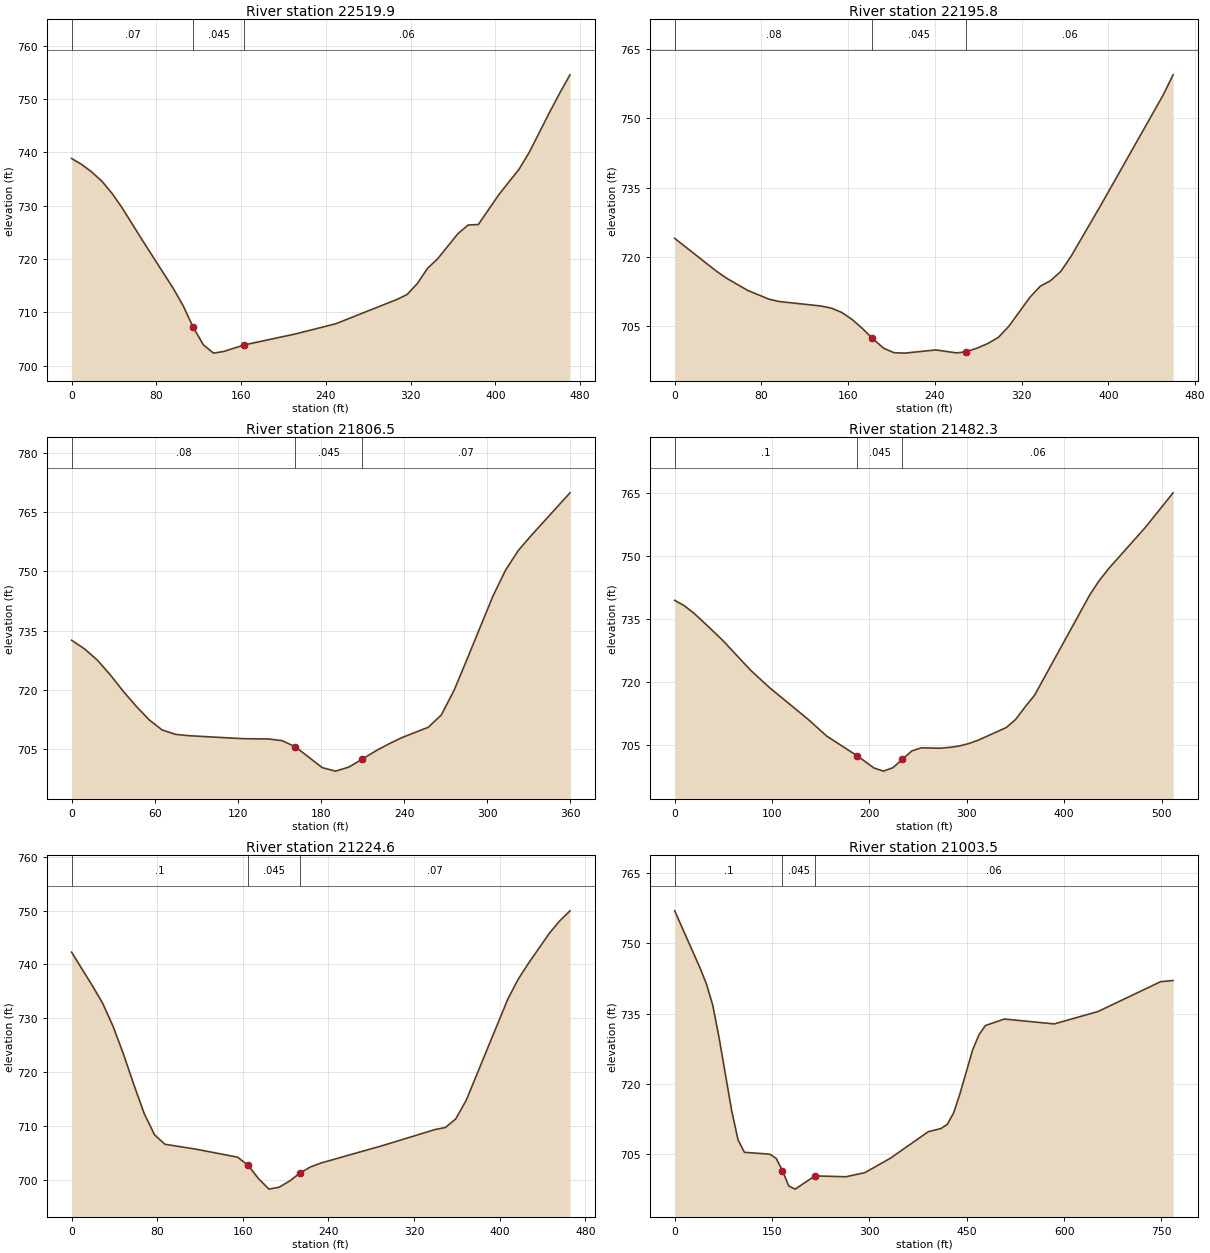
Type RM Length L Ch R = 1 ,22519.9 ,297.8,324.1,361.9
XS GIS Cut Line= 3
     1569864.267      347124.948     1569959.753      347120.607
     1570250.552      346884.062
#Sta/Elev= 30
       0  738.86     9.6  737.73    19.1  736.32    28.7  734.57    38.2  732.31
    47.8  729.58    66.9   723.5    95.6  714.61   105.2  711.29   114.8   707.2
   124.4   703.9     134  702.35   143.6  702.66   162.9  703.89   210.9  705.93
   249.4  707.86     307  712.41   316.6  713.33   326.3  715.39   335.9  718.24
   345.5  720.04   364.7  724.77   374.3  726.38   383.9  726.47   403.2  732.06
   422.4  736.86     432  740.02   451.2  747.54   460.8  751.14   470.4  754.55
#Mann= 3 , 0 , 0
       0     .07       0   114.8    .045       0   162.9     .06       0
Bank Sta=114.8,162.9
XS Rating Curve= 0 ,0
Exp/Cntr=0.3,0.1

Type RM Length L Ch R = 1 ,22195.8 ,332.3,389.3,438.9
XS GIS Cut Line= 3
     1569946.733      347348.472     1570283.104      347372.343
     1570389.441      347433.107
#Sta/Elev= 30
       0  724.01    38.5  716.91    48.2  715.34    67.4  712.75    86.7  710.88
    96.4  710.35   134.9  709.38   144.5  708.92   154.2  707.98   163.8  706.44
   173.4  704.46     182 702.474   192.7  700.25   202.3  699.28     212  699.19
   240.9  699.88   260.1  699.24     269 699.497   279.4  700.31     289  701.29
   298.7  702.63   308.3  705.02   327.6  711.26   337.2  713.67   346.6  714.85
   356.1  716.86   365.5  720.09   393.7  731.46   450.3   754.9   459.7  759.38
#Mann= 3 , 0 , 0
       0     .08       0     182    .045       0     269     .06       0
Bank Sta=182,269
XS Rating Curve= 0 ,0
Exp/Cntr=0.3,0.1

Type RM Length L Ch R = 1 ,21806.5 ,332,324.3,316.4
XS GIS Cut Line= 4
     1569846.906      347517.743       1569905.5       347547.04
     1569994.476      347706.545     1570079.111      347779.245
#Sta/Elev= 30
       0  732.56     9.4  730.36    18.7  727.49    28.1  723.72    37.4  719.58
    46.8  715.78    56.2  712.32    65.5   709.8    75.1  708.71    84.7  708.37
   123.2  707.62   142.4  707.53     152  707.11   161.6  705.53   180.9  700.28
   190.5  699.39   200.1  700.41   209.7  702.41   219.3  704.47   228.9  706.27
   238.5   707.9   257.4   710.5   266.8   713.6     276  719.82   285.3  727.65
   303.9  743.58   313.2  750.32   322.5  755.35   331.8  759.13   359.7  769.92
#Mann= 3 , 0 , 0
       0     .08       0   161.6    .045       0   209.7     .07       0
Bank Sta=161.6,209.7
XS Rating Curve= 0 ,0
Exp/Cntr=0.3,0.1

Type RM Length L Ch R = 1 ,21482.3 ,262.9,257.6,250.7
XS GIS Cut Line= 4
     1569689.571      347659.887     1569689.571      347816.137
     1569820.865      347984.323     1569963.009      347978.897
#Sta/Elev= 30
       0  739.41     9.8  738.14    19.5  736.39    29.3  734.31    48.8  730.02
    78.1  722.76    97.7   718.6   136.7  711.19   156.2  707.13   187.7  702.42
   204.7  699.55   214.4  698.81   224.1  699.61   233.8  701.62   243.5   703.6
   253.2  704.35   272.6  704.26   282.3  704.45     292  704.77   301.7  705.34
   311.4  706.13   340.5  709.16   350.2   711.1   359.9  714.08   369.6  716.84
   426.5  740.77     436  744.08   445.5  746.88   483.4  756.74   511.9  764.96
#Mann= 3 , 0 , 0
       0      .1       0   187.7    .045       0   233.8     .06       0
Bank Sta=187.7,233.8
XS Rating Curve= 0 ,0
Exp/Cntr=0.3,0.1

Type RM Length L Ch R = 1 ,21224.6 ,224.2,221.1,217.9
XS GIS Cut Line= 2
     1569433.495      347910.538     1569762.271      348240.399
#Sta/Elev= 30
       0  742.28    19.4  736.07    29.1  732.79    38.8  728.51    48.5  723.37
    58.2  717.72    67.9  712.34    77.6  708.41    87.3  706.67   116.4  705.76
   155.2  704.28     165  702.76   174.6  700.32   184.4  698.36     194  698.72
   203.8  699.87   213.5  701.35   223.2  702.47   232.9  703.19   291.1  706.46
   339.6   709.4   349.3  709.78     359  711.38   368.7   714.8   407.5  733.52
   417.2  737.22   426.9  740.21   446.3  745.74     456  748.05   465.7  749.94
#Mann= 3 , 0 , 0
       0      .1       0     165    .045       0   213.5     .07       0
Bank Sta=165,213.5
XS Rating Curve= 0 ,0
Exp/Cntr=0.3,0.1

Type RM Length L Ch R = 1 ,21003.5 ,200.7,201.5,203.7
XS GIS Cut Line= 3
     1569274.532      348079.266     1569647.796      348409.127
     1569769.324      348650.013
#Sta/Elev= 30
       0  756.97    39.1  744.75    48.8  741.38    58.6  736.84    68.4  729.86
    87.9  714.21    97.7     708   107.4  705.41   146.5     705   156.3  704.12
     166  701.48   175.8   698.2   185.6  697.54   216.2  700.37   263.7  700.18
     293  701.06   332.1  704.12   390.7   709.8   410.2  710.48     420  711.37
   429.8  713.83   439.5  717.91   459.1  727.29   468.8  730.49   478.6  732.47
   507.8  733.86   584.8  732.82   652.3  735.47   748.7  741.84   767.9  742.09
#Mann= 3 , 0 , 0
       0      .1       0     166    .045       0   216.2     .06       0
Bank Sta=166,216.2
XS Rating Curve= 0 ,0
Exp/Cntr=0.3,0.1

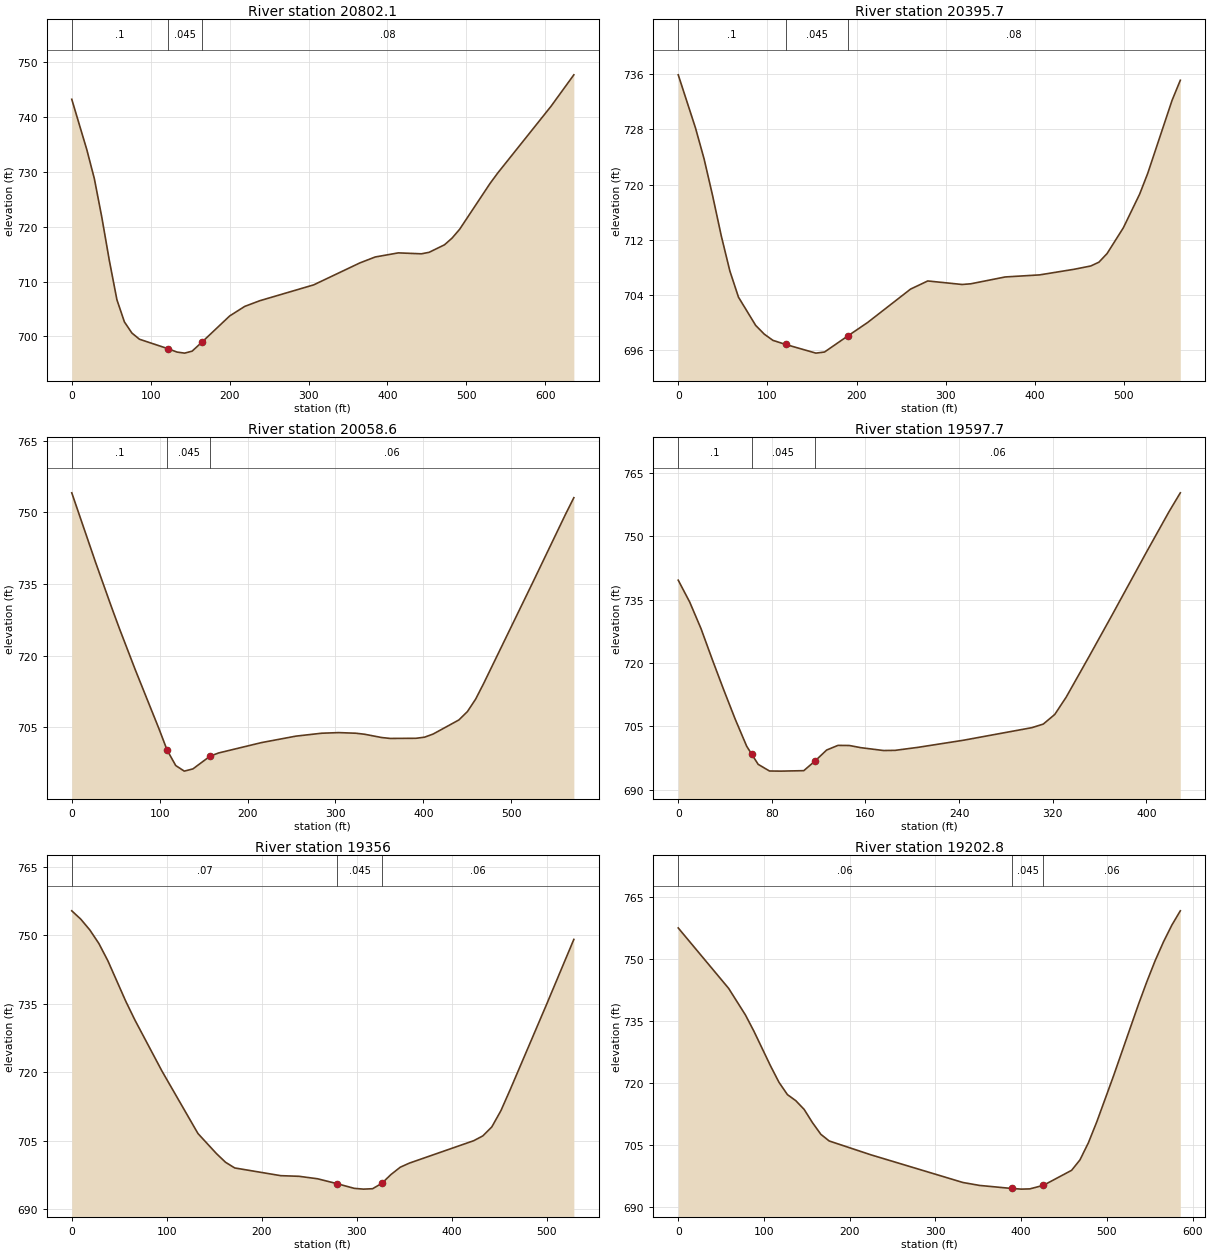
Type RM Length L Ch R = 1 ,20802.1 ,417.4,406.4,391.3
XS GIS Cut Line= 4
     1569166.025      348246.367     1569343.976      348404.787
     1569450.313       348613.12     1569469.845      348775.881
#Sta/Elev= 30
       0  743.22    19.1  734.02    28.6  728.76    38.1   721.7    47.6  713.84
    57.2  706.69    66.7  702.65    76.2  700.62    85.8  699.49     122 697.762
   133.4  697.15     143  696.96   152.5  697.32     165 698.972   200.1  703.74
   219.2  705.48   238.2  706.51   306.5   709.4     365   713.4   384.4  714.48
   413.7  715.23   442.9  715.06   452.7  715.33   472.2   716.7   481.8  717.92
   491.4  719.53     530   727.9   539.6  729.77   607.2  741.95   636.1  747.68
#Mann= 3 , 0 , 0
       0      .1       0     122    .045       0     165     .08       0
Bank Sta=122,165
XS Rating Curve= 0 ,0
Exp/Cntr=0.3,0.1

Type RM Length L Ch R = 1 ,20395.7 ,354.6,337,337.2
XS GIS Cut Line= 3
     1568890.417      348537.166     1569278.872      348771.541
     1569348.317      348856.176
#Sta/Elev= 30
       0  735.89    19.3  728.22      29  723.72    38.6  718.37    48.3  712.56
    57.9  707.49    67.6  703.69    86.9   699.6    96.5  698.34   106.2  697.44
   120.7  696.84   154.4  695.59   164.1  695.75   190.7  698.12   212.4  700.02
   260.6  704.86   279.9  706.04   318.5  705.53   328.2  705.63   366.8  706.62
   405.4  706.92     444  707.73   462.8  708.21   471.9  708.76     481     710
   499.3  713.74   517.6  718.62   526.7  721.64     554  732.21   563.2   735.1
#Mann= 3 , 0 , 0
       0      .1       0   120.7    .045       0   190.7     .08       0
Bank Sta=120.7,190.7
XS Rating Curve= 0 ,0
Exp/Cntr=0.3,0.1

Type RM Length L Ch R = 1 ,20058.6 ,443.9,460.9,461.2
XS GIS Cut Line= 4
     1568716.806      348884.388     1568825.313      348884.388
     1569126.963      349044.978      1569244.15       349075.36
#Sta/Elev= 30
       0  754.07    27.1  739.52    45.2  730.17    54.2  725.68    72.3  717.03
    99.5  704.58   108.5  700.23   118.3  697.01     128  695.84   137.8   696.3
   157.3  698.96   167.1  699.64   215.9  701.81     255  703.16   284.3  703.77
   303.8   703.9   323.3  703.77   333.1  703.56   352.6  702.87   362.4  702.68
   391.7  702.71   401.4  702.94   411.2   703.6   440.5  706.55   450.2   708.3
   459.6  710.92   468.9  714.26   524.7  735.37     562  749.64   571.3  753.05
#Mann= 3 , 0 , 0
       0      .1       0   108.5    .045       0   157.3     .06       0
Bank Sta=108.5,157.3
XS Rating Curve= 0 ,0
Exp/Cntr=0.3,0.1

Type RM Length L Ch R = 1 ,19597.7 ,241.5,241.7,240
XS GIS Cut Line= 2
     1568690.765      349303.225     1569070.539      349502.877
#Sta/Elev= 30
       0  739.64     9.8  734.46    19.5  728.14    29.2  720.77      39  713.57
    48.8  706.64    58.5   700.3    62.7  698.46    68.3  696.01      78  694.43
    87.8   694.4   107.3  694.51     117  696.82   126.8  699.39   136.5   700.5
   146.3  700.47     156  699.96   175.5  699.28   185.3  699.32   204.8  700.03
   243.8  701.72   302.3   704.7     312  705.55   321.8  707.83   331.5   711.9
     351  721.49   370.6  731.29   399.8   746.1   419.3   755.8   429.1  760.34
#Mann= 3 , 0 , 0
       0      .1       0    62.7    .045       0     117     .06       0
Bank Sta=62.7,117
XS Rating Curve= 0 ,0
Exp/Cntr=0.3,0.1

Type RM Length L Ch R = 1 ,19356   ,151.9,153.2,157.8
XS GIS Cut Line= 4
     1568608.299      349377.009      1568619.15      349509.388
     1568873.056      349628.745     1568966.372       349696.02
#Sta/Elev= 30
       0  755.39     9.5  753.56      19   751.2    28.5  748.24      38  744.44
    56.9  735.54    66.4  731.48    94.9  720.28   132.8  706.59   152.2   702.2
   161.8  700.29   171.5  699.04   219.9  697.35   239.2  697.21   258.6  696.67
   279.5  695.58   297.3  694.57     307   694.4   316.6  694.49   326.3  695.67
     336  697.61   345.7   699.2   355.3   700.1     423  705.01   432.6  706.06
   442.1  708.04   451.7  711.62   461.3  716.15   499.7  734.88   528.4  749.13
#Mann= 3 , 0 , 0
       0     .07       0   279.5    .045       0   326.3     .06       0
Bank Sta=279.5,326.3
XS Rating Curve= 0 ,0
Exp/Cntr=0.3,0.1

Type RM Length L Ch R = 1 ,19202.8 ,239.5,239.3,235.8
XS GIS Cut Line= 3
     1568415.157      349656.957     1568532.345      349607.044
      1568935.99      349824.058
#Sta/Elev= 30
       0  757.43    58.8  742.85    78.4  736.43    88.2  732.55   107.8  724.09
   117.6  720.16   127.4  717.21   137.1  715.76   146.9  713.64   156.6  710.45
   166.4  707.63   176.1  706.03   224.9  702.68   332.1  696.01   351.6   695.3
     389  694.57   400.4  694.41   410.2  694.47     426 695.329   458.9  698.95
   468.6  701.45   478.4  705.56   488.2  710.61   507.6  721.62   536.9  738.99
   546.7  744.48   556.4  749.56   566.2  754.13   575.9  758.14   585.7  761.56
#Mann= 3 , 0 , 0
       0     .06       0     389    .045       0     426     .06       0
Bank Sta=389,426
XS Rating Curve= 0 ,0
Exp/Cntr=0.3,0.1

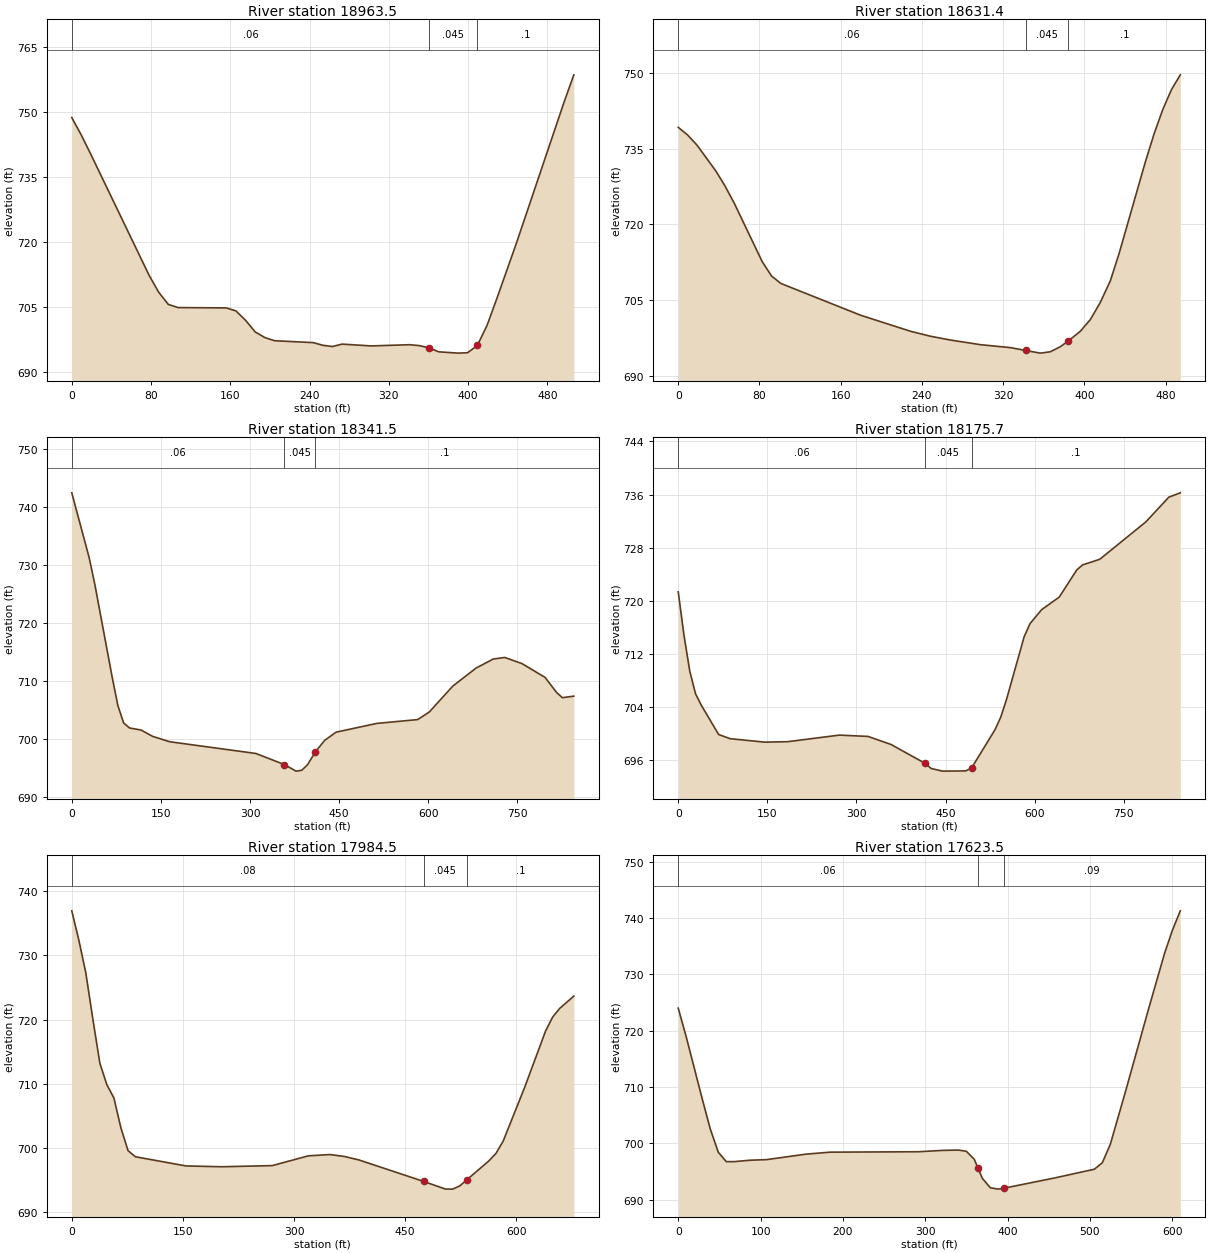
Type RM Length L Ch R = 1 ,18963.5 ,332.2,332.1,332.7
XS GIS Cut Line= 2
     1568395.626      349787.166     1568847.015        350017.2
#Sta/Elev= 30
       0  748.69     9.7  744.63    19.5  740.09    77.9   712.4    87.7  708.44
    97.4  705.63   107.2   704.9   155.9  704.82   165.6  704.14   175.4  701.96
   185.1  699.28   194.9  697.98   204.6  697.26   243.6  696.82   253.3  696.21
     263  695.92   272.8  696.48     302  696.06     341  696.34   350.7  696.13
   360.5  695.62   370.2   694.7   389.7   694.4   399.4  694.49   409.2  696.16
   418.9  700.72   428.7  706.85   448.2  719.44   496.9  752.35   506.6  758.54
#Mann= 3 , 0 , 0
       0     .06       0   360.5    .045       0   409.2      .1       0
Bank Sta=360.5,409.2
XS Rating Curve= 0 ,0
Exp/Cntr=0.3,0.1

Type RM Length L Ch R = 1 ,18631.4 ,297.6,290,282
XS GIS Cut Line= 4
     1568274.098      350110.516     1568371.754      350136.558
     1568656.042      350292.808     1568723.317      350277.617
#Sta/Elev= 30
       0  739.22     9.2  737.71    18.4  735.71    36.8  730.64    45.9  727.66
    55.1  724.21    82.7   712.6    91.9  709.76   101.1  708.28   179.7  701.98
   228.9   698.8   248.5  697.82   268.2  697.07   297.7  696.15   327.2  695.57
     342 695.005   356.6  694.48   366.5  694.75   376.3  695.76     384 696.864
     396  698.82   405.8  701.13   415.6  704.52   425.5  708.81   434.1   714.2
     460  732.38   468.6  737.94   477.2  742.78   485.8  746.73   494.4  749.62
#Mann= 3 , 0 , 0
       0     .06       0     342    .045       0     384      .1       0
Bank Sta=342,384
XS Rating Curve= 0 ,0
Exp/Cntr=0.3,0.1

Type RM Length L Ch R = 1 ,18341.5 ,165.2,165.8,167.3
XS GIS Cut Line= 6
     1568129.241      350402.183       1568228.2      350442.547
      1568321.95      350467.287     1568566.741      350555.829
     1568756.845      350636.558     1568919.606      350699.058
#Sta/Elev= 30
       0  742.41    29.2  731.28    38.9  726.59      68  710.66    77.7  705.72
    87.4  702.76    97.2   701.9   116.6  701.55     136  700.46     165  699.53
   309.9  697.51     358 695.594   377.4  694.47     387  694.61   396.7  695.56
     410 697.778   425.6  699.77   444.9  701.18   513.3  702.69   582.2  703.35
   601.8  704.66   641.2  709.11   680.4  712.22   709.4  713.78   728.8  714.05
   757.8  712.99   796.6  710.61     816  708.02   825.7  707.12     845  707.39
#Mann= 3 , 0 , 0
       0     .06       0     358    .045       0     410      .1       0
Bank Sta=358,410
XS Rating Curve= 0 ,0
Exp/Cntr=0.3,0.1

Type RM Length L Ch R = 1 ,18175.7 ,183.5,191.3,197.4
XS GIS Cut Line= 6
     1568056.325      350545.412     1568155.283      350585.777
     1568249.033      350610.516     1568493.825      350699.058
     1568683.929      350779.787     1568846.689      350842.287
#Sta/Elev= 30
       0  721.37     9.7  714.84    19.4  709.44    29.2  706.01    38.9   704.3
      68  699.91    87.4  699.28   145.7  698.76   184.4  698.83   271.3  699.82
   319.5  699.62   358.1  698.41   415.9  695.55   425.6   694.8   444.9   694.4
   483.8  694.43   493.6  694.86     533  700.61   542.8  702.52   552.7  705.25
   582.2  714.62     592  716.58   611.7   718.7   641.2  720.58   670.7  724.66
   680.4  725.42   709.4  726.27   786.9  731.89   825.7  735.62     845  736.27
#Mann= 3 , 0 , 0
       0     .06       0   415.9    .045       0   493.6      .1       0
Bank Sta=415.9,493.6
XS Rating Curve= 0 ,0
Exp/Cntr=0.3,0.1

Type RM Length L Ch R = 1 ,17984.5 ,358.6,361,363.7
XS GIS Cut Line= 4
     1567976.898      350607.912     1568023.773      350654.787
     1568483.408      350909.995     1568518.564       350988.12
#Sta/Elev= 30
       0  736.91     9.5  732.38    18.9   727.3    28.4  720.11    37.9  713.21
    47.4  709.84    56.8  707.82    66.3  703.15      76  699.59    85.8  698.65
   153.9  697.22   202.6  697.09   270.7  697.27   319.4  698.79   348.6  698.99
   368.1  698.69   387.6  698.15   474.9  694.81   504.4  693.62   514.1  693.61
   523.9  694.12   533.6   695.1   562.8  697.98   572.6  699.17   582.3  701.08
   611.1  709.38   639.6  718.22   649.1  720.38   658.7  721.74   677.7  723.64
#Mann= 3 , 0 , 0
       0     .08       0   474.9    .045       0   533.6      .1       0
Bank Sta=474.9,533.6
XS Rating Curve= 0 ,0
Exp/Cntr=0.3,0.1

Type RM Length L Ch R = 1 ,17623.5 ,309.4,308.3,298.3
XS GIS Cut Line= 3
     1567841.481      350917.808     1568295.908      351199.058
     1568333.668      351264.162
#Sta/Elev= 30
       0  724.01     9.7  718.92    29.2  707.88    38.9  702.58    48.6  698.46
    58.3  696.78      68  696.78    87.4  697.03   106.9  697.13   155.5  698.11
   184.6  698.46   291.5  698.53   320.6  698.77   340.1  698.83   349.8  698.62
   359.5   697.2     364 695.641   369.2  693.84     379  692.14   388.7   691.9
     395 692.049   456.7  693.87   505.3  695.43     515  696.58   524.7  699.84
   543.8  709.56     572  724.31   590.9  733.89   600.3  737.91   609.7  741.28
#Mann= 3 , 0 , 0
       0     .06       0     364    .045       0     395     .09       0
Bank Sta=364,395
XS Rating Curve= 0 ,0
Exp/Cntr=0.3,0.1

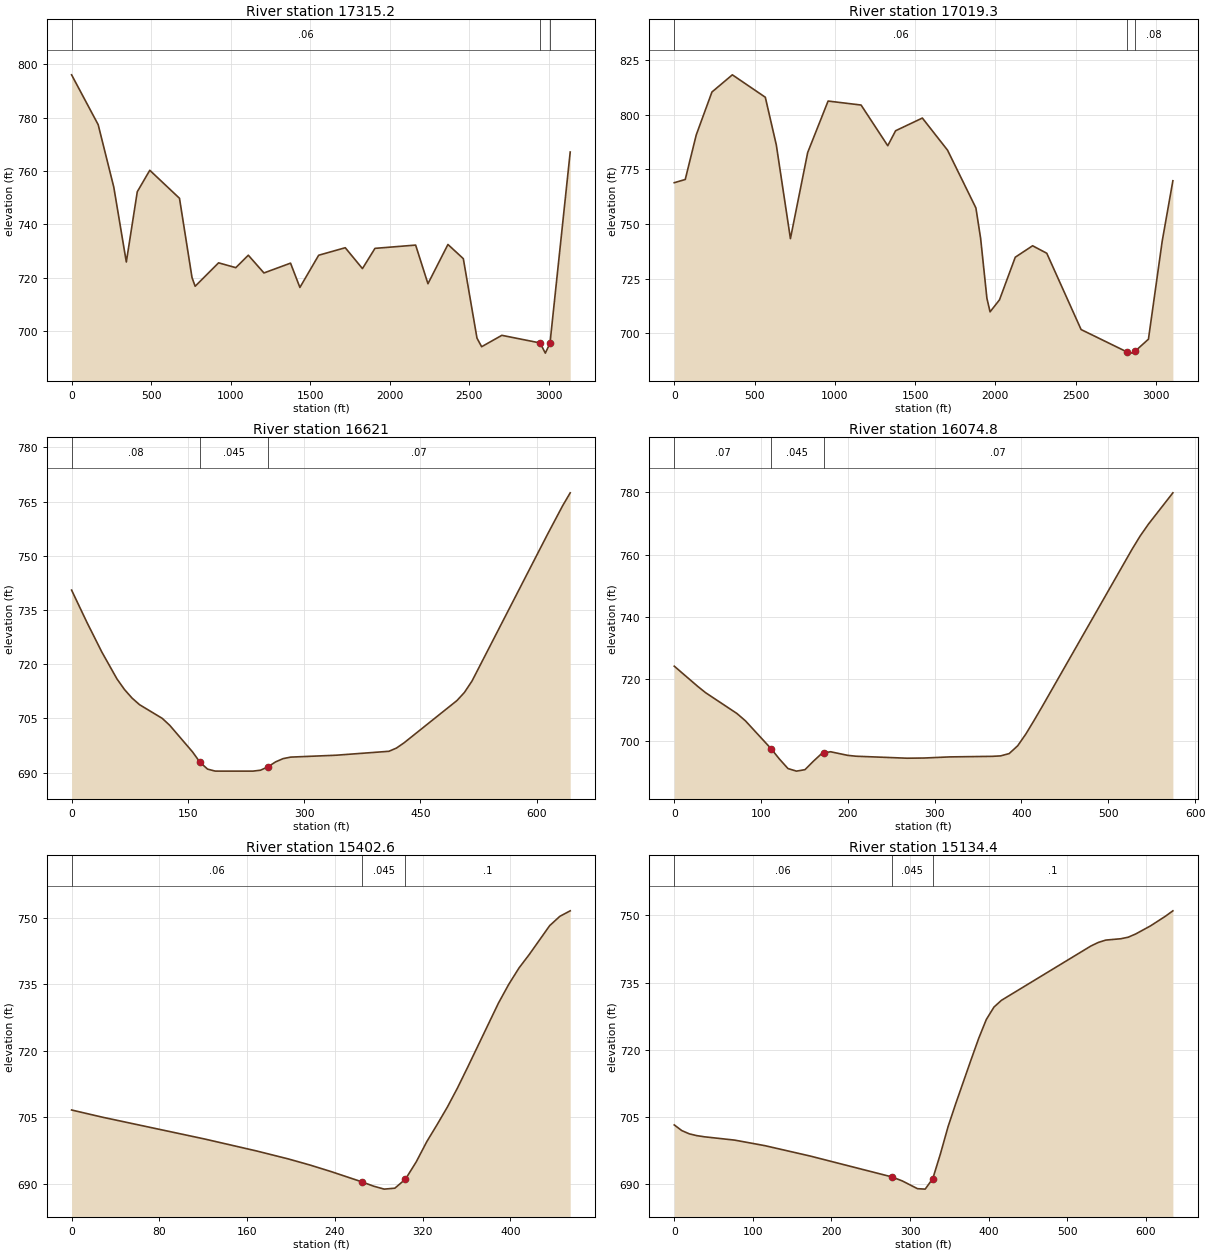
Type RM Length L Ch R = 1 ,17315.2 ,329.3,295.9,267.4
XS GIS Cut Line= 6
     1565645.358      350228.405       1567728.2      350812.339
     1567775.075      351098.797     1567756.845      351192.547
       1568165.7      351421.714     1568282.887      351429.527
#Sta/Elev= 30
       0  795.98   167.2  777.32   265.5   753.9   344.1  725.94     413  752.23
   491.6  760.26   678.4  749.78   757.1  720.14   776.8  716.86   924.2  725.63
  1032.4  723.82  1111.1  728.48  1209.4  721.84  1376.6  725.51  1435.5  716.42
  1553.5  728.47  1720.7  731.28  1828.8  723.47  1907.5  731.04  2163.2  732.27
  2240.6  717.81  2366.3   732.5    2463  727.19  2548.9  697.45  2578.2  694.24
  2705.2   698.5  2945.6  695.65  2978.6  691.84  3007.9  695.51  3135.1  767.09
#Mann= 3 , 0 , 0
       0     .06       0  2945.6    .045       0  3007.9     .08       0
Bank Sta=2945.6,3007.9
XS Rating Curve= 0 ,0
Exp/Cntr=0.3,0.1

Type RM Length L Ch R = 1 ,17019.3 ,436.6,398.3,358.2
XS GIS Cut Line= 6
     1565384.941      351124.239     1566802.157      351165.164
     1567597.991      351755.047     1567736.012      351710.777
     1568142.262      351656.089     1568264.137      351582.478
#Sta/Elev= 30
       0  768.87    68.4  770.33   136.9  790.68   234.7  810.29   361.8  818.14
   567.1   807.9   635.6  786.14   723.6  743.32   831.1  782.66   958.2  806.16
  1163.6  804.34  1329.8  785.76  1378.7   792.6  1545.3   798.4  1702.2  783.72
  1878.8  757.34  1908.2  743.47  1947.4  716.08  1967.1  709.87  2025.9  715.38
    2124  734.83  2231.9  740.06  2320.2  736.64    2534  701.79  2817.7 691.631
  2846.2  691.02  2870.7 691.903  2953.5  697.39  3039.2  742.17  3105.7  769.75
#Mann= 3 , 0 , 0
       0     .06       0  2817.7    .045       0  2870.7     .08       0
Bank Sta=2817.7,2870.7
XS Rating Curve= 0 ,0
Exp/Cntr=0.3,0.1

Type RM Length L Ch R = 1 ,16621   ,561.4,546.2,528.8
XS GIS Cut Line= 2
     1567960.318      352216.159     1568366.134      351717.027
#Sta/Elev= 30
       0  740.51    19.5  731.71      39  723.37    58.5  715.94    68.2     713
      78  710.62    87.7  708.79     117     705   126.7  703.06     156  695.73
   165.7  692.84   175.4  690.96   185.2  690.41   194.9   690.4   233.9   690.4
   243.7  690.65   253.4   691.6   263.2  692.96   272.9  693.86   282.7  694.28
   341.1   694.8   409.4  695.89   419.1  696.78   428.9  698.23   497.1  709.92
   506.8  712.18   516.6  715.34     614  755.95   633.5  763.85   643.3  767.44
#Mann= 3 , 0 , 0
       0     .08       0   165.7    .045       0   253.4     .07       0
Bank Sta=165.7,253.4
XS Rating Curve= 0 ,0
Exp/Cntr=0.3,0.1

Type RM Length L Ch R = 1 ,16074.8 ,627.9,672.3,702.7
XS GIS Cut Line= 4
     1568502.852      352417.981     1568541.915      352357.218
     1568652.592      352053.398     1568669.953      351875.447
#Sta/Elev= 30
       0  724.04    27.1  717.52    36.1   715.5    72.2   708.8      82  706.44
   111.4  697.51   121.2  694.12     131  691.07   140.8  690.24   150.6  690.71
   160.4  693.46   170.2  695.99   172.1  696.08     180  696.48   199.6  695.33
   209.4  695.04   268.2   694.4   287.8  694.46   317.2  694.82   366.2     695
     376  695.15   385.8  695.89   395.6   698.4     405  702.18   414.4  706.52
   423.8  711.01   527.3  761.66   536.7  765.96   546.2  769.77   574.4  779.87
#Mann= 3 , 0 , 0
       0     .07       0   111.4    .045       0   172.1     .07       0
Bank Sta=111.4,172.1
XS Rating Curve= 0 ,0
Exp/Cntr=0.3,0.1

Type RM Length L Ch R = 1 ,15402.6 ,264.6,268.2,285.2
XS GIS Cut Line= 4
     1568880.457      352619.804     1569008.495       352543.85
     1569173.425      352485.256     1569260.231        352387.6
#Sta/Elev= 25
       0  706.63    27.9  705.02     121  700.11   168.3  697.42   197.5  695.61
   216.9  694.26   236.4  692.77   264.4  690.46   275.3  689.47     285   688.8
   294.7  689.01   304.4  691.05   314.2  694.94   323.9  699.53   333.2  703.32
   342.6  707.29   351.9  711.63   361.2  716.32   389.2  730.73   398.6  734.96
   407.9  738.63   417.2  741.65   435.9  748.18   445.2  750.28   454.6  751.51
#Mann= 3 , 0 , 0
       0     .06       0   264.4    .045       0   304.4      .1       0
Bank Sta=264.4,304.4
XS Rating Curve= 0 ,0
Exp/Cntr=0.3,0.1

Type RM Length L Ch R = 1 ,15134.4 ,219.9,210.7,193
XS GIS Cut Line= 4
     1568945.561      352765.204     1569108.321      352780.395
     1569342.696      352715.291     1569492.436       352543.85
#Sta/Elev= 30
       0   703.2     9.6  701.93    19.2   701.2    28.8   700.8    38.5  700.54
    76.9   699.8   115.4  698.56   173.2  696.23   276.6  691.59     290  690.69
   309.4  688.95   319.2  688.85   328.9  691.21   338.6  696.73   348.3   702.8
   358.1  707.97   377.5  717.73   387.3  722.55     397  726.77   406.7  729.53
   416.2  731.04     530  743.18   539.5  743.98     549   744.5     568   744.8
   577.4  745.14   586.9  745.86   605.9  747.68   624.9  749.84   634.3  751.04
#Mann= 3 , 0 , 0
       0     .06       0   276.6    .045       0   328.9      .1       0
Bank Sta=276.6,328.9
XS Rating Curve= 0 ,0
Exp/Cntr=0.3,0.1

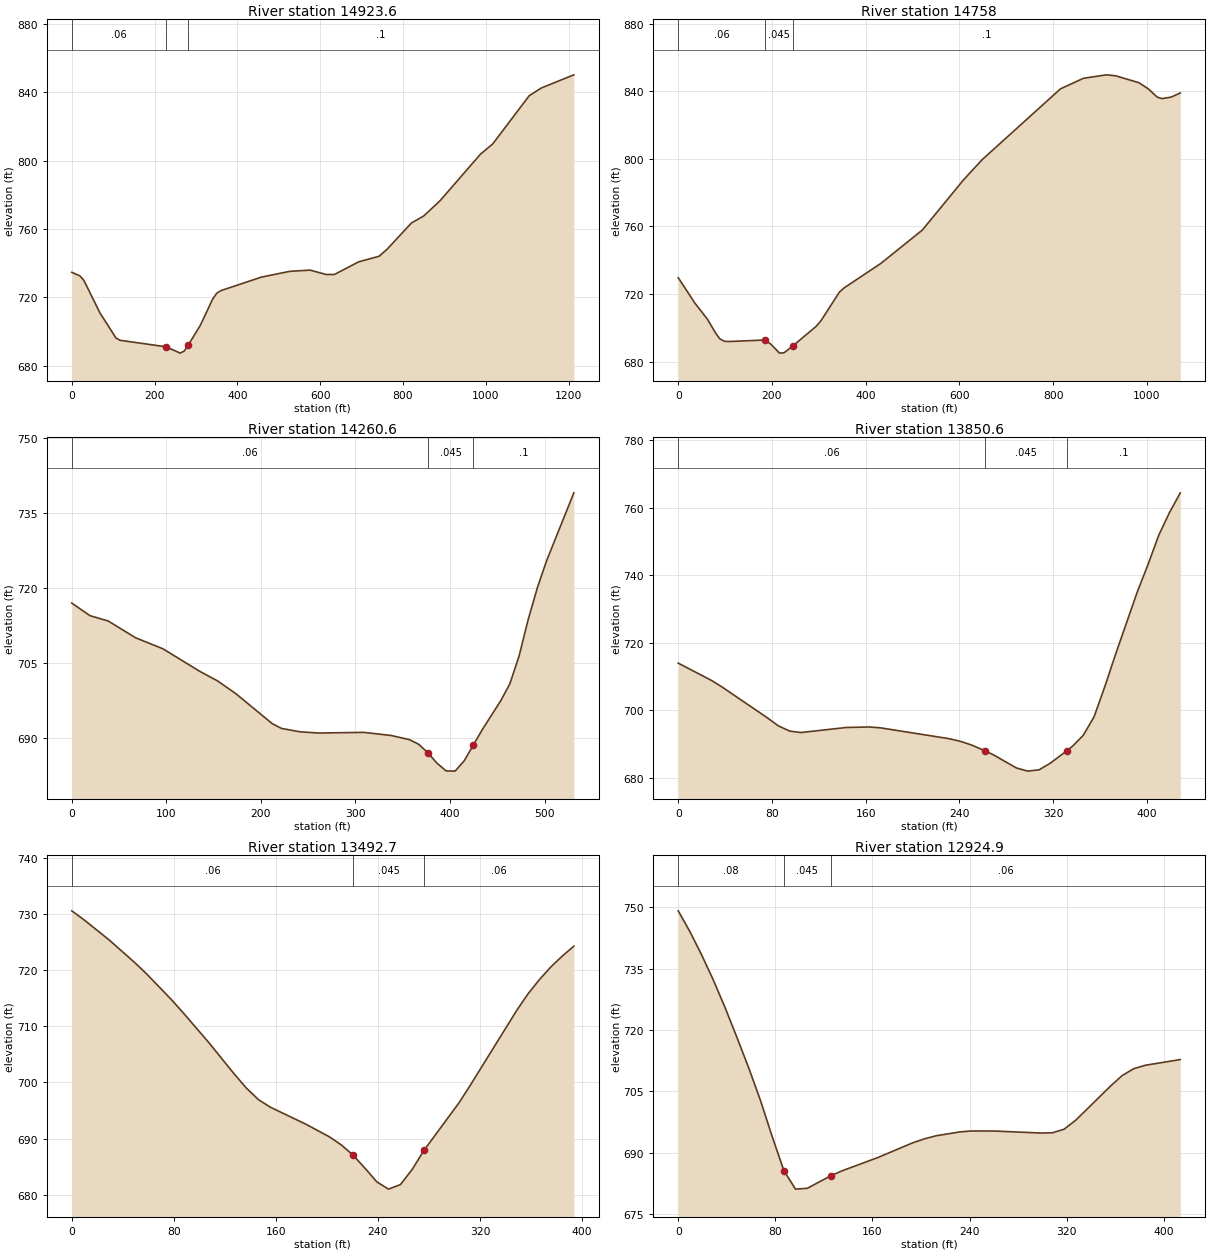
Type RM Length L Ch R = 1 ,14923.6 ,157.8,165.6,196.4
XS GIS Cut Line= 3
     1569064.918      353058.172     1569327.505      352932.304
     1569972.188      352274.116
#Sta/Elev= 30
       0  734.67    19.4  732.65    29.1  730.07      68  710.96   106.8  696.26
   116.5  694.92   227.6  691.11   262.1   687.4   271.8  688.66   281.5  692.16
   310.8  703.83   340.2  719.01     350  722.44   359.8  723.96   457.8  731.87
   526.4  735.26   575.4  735.97   614.6   733.4   634.2  733.42     693  740.84
     742  744.06   761.7  748.25   820.5   763.6   849.9  767.66   889.1  776.51
   987.1  803.85  1016.5  809.79  1104.7  838.04  1134.1  842.58  1212.5  850.26
#Mann= 3 , 0 , 0
       0     .06       0   227.6    .045       0   281.5      .1       0
Bank Sta=227.6,281.5
XS Rating Curve= 0 ,0
Exp/Cntr=0.3,0.1

Type RM Length L Ch R = 1 ,14758   ,428.6,497.4,551.4
XS GIS Cut Line= 4
     1569101.811      353127.617     1569188.616      353147.148
     1569338.356      353101.575     1570133.647      353323.595
#Sta/Elev= 30
       0  729.64    35.6  714.59    62.3  705.08    80.1  696.71      89   693.4
    98.8  691.99   108.5  691.88   184.2  692.75   196.6  690.54   216.2     685
   225.9  685.24   245.5  689.48   294.6  700.94   304.5  704.15   343.8  721.06
   353.6  723.53   432.3   738.1   520.7  757.81   609.2  787.71   648.5  799.52
   815.6  841.41   864.8  847.67   913.9   849.7   933.6   849.1   982.7  845.04
  1002.4  841.52    1022  836.49  1031.9  835.63  1051.5   836.5  1071.2  838.97
#Mann= 3 , 0 , 0
       0     .06       0   184.2    .045       0   245.5      .1       0
Bank Sta=184.2,245.5
XS Rating Curve= 0 ,0
Exp/Cntr=0.3,0.1

Type RM Length L Ch R = 1 ,14260.6 ,344.3,410,469.6
XS GIS Cut Line= 3
     1569130.023      353218.763     1569162.575      353379.353
     1569340.526      353700.534
#Sta/Elev= 30
       0  716.99    19.3  714.47    38.6   713.4    67.5  710.05    96.4  707.85
   134.9  703.39   154.2  701.42   173.5  698.88   212.2  692.85   221.8  691.92
   241.2  691.25   260.5     691   308.8  691.13   337.8  690.51   357.1  689.68
   366.8  688.77   376.4   687.1   386.1     685   395.8  683.43   405.4  683.38
   415.1  685.46   424.8  688.64   434.4  691.75   453.7  697.46   463.4  700.87
   473.1  706.42   482.7  713.68   492.4  720.06     502  725.36     531  739.04
#Mann= 3 , 0 , 0
       0     .06       0   376.4    .045       0   424.8      .1       0
Bank Sta=376.4,424.8
XS Rating Curve= 0 ,0
Exp/Cntr=0.3,0.1

Type RM Length L Ch R = 1 ,13850.6 ,345.3,357.9,374.5
XS GIS Cut Line= 4
      1569088.79      353223.103     1569071.429      353296.888
     1568897.818      353479.179     1568845.734      353565.876
#Sta/Elev= 30
       0  713.97    28.4  708.84    37.9  706.78    75.8  697.83    85.5  695.37
    95.2  693.82   104.8  693.39   143.6  694.89   162.9  695.04   172.6  694.79
   230.7   691.6   240.4  690.84   250.1  689.74   262.1  687.96   269.4  686.73
   288.8  682.88   298.5  681.95   308.2  682.35   317.8  684.33   332.1  688.06
   336.7  689.34   345.9   692.6   355.1  698.08   364.3  707.08   373.5  716.67
   391.9  735.02   401.1  743.18   410.3  751.89   419.5  758.65   428.7  764.46
#Mann= 3 , 0 , 0
       0     .06       0   262.1    .045       0   332.1      .1       0
Bank Sta=262.1,332.1
XS Rating Curve= 0 ,0
Exp/Cntr=0.3,0.1

Type RM Length L Ch R = 1 ,13492.7 ,593.5,567.9,542.1
XS GIS Cut Line= 4
     1568929.068      352990.356     1568827.505      353095.824
     1568694.693       353180.46     1568637.401       353249.47
#Sta/Elev= 30
       0  730.53     9.8   728.9    29.3  725.35    48.8  721.44    58.6  719.33
    78.1  714.74    87.8  712.28   107.4  707.11   126.9  701.64   136.7  699.04
   146.4  696.94   155.7   695.6   183.5  692.58     202  690.33   211.3  688.89
   220.5  687.08   229.8  684.77   239.1  682.33   248.3  681.03   257.6  681.83
   266.8  684.51   276.1  687.92   303.9  696.49   312.9  699.68   348.8  712.81
   357.7  715.77   366.7  718.32   375.7  720.58   384.6   722.5   393.6  724.24
#Mann= 3 , 0 , 0
       0     .06       0   220.5    .045       0   276.1     .06       0
Bank Sta=220.5,276.1
XS Rating Curve= 0 ,0
Exp/Cntr=0.3,0.1

Type RM Length L Ch R = 1 ,12924.9 ,230.9,188.9,146.8
XS GIS Cut Line= 3
     1568387.401      352698.689     1568287.141      352886.189
     1568272.818       353086.71
#Sta/Elev= 30
       0  749.12     9.7     744    19.3  738.34      29  732.16    38.7  725.41
    48.3  718.24      58  710.81    67.6  702.93    77.3  694.08      87  685.68
    96.6  681.14   106.3  681.34   125.6  684.39   135.3  685.65   164.3  688.84
   193.3  692.47     203  693.44   212.6  694.18   231.8  695.11   241.3  695.34
   260.5  695.33   298.8  694.84   308.4  694.91   317.9  695.78   327.5  697.99
   356.2  706.34   365.8   708.9   375.4  710.58   384.9   711.4   413.6  712.79
#Mann= 3 , 0 , 0
       0     .08       0      87    .045       0   125.6     .06       0
Bank Sta=87,125.6
XS Rating Curve= 0 ,0
Exp/Cntr=0.3,0.1