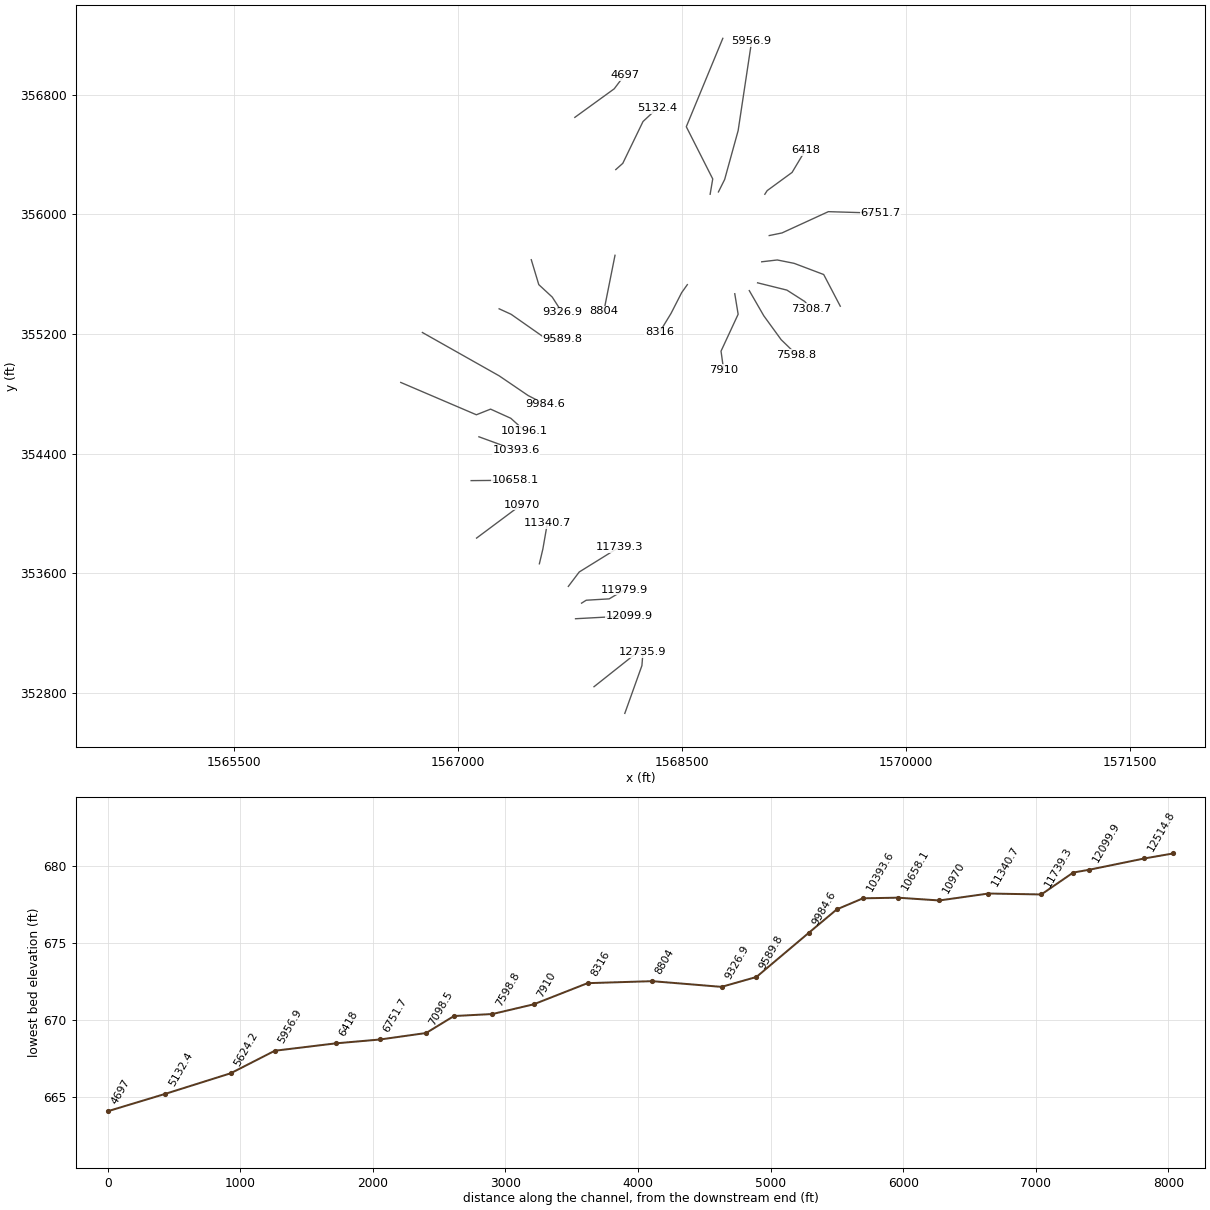
HEC-RAS study SNCHOCRK.prj: SNCHOCRK

--- SNCHOCRK.g02 (geometry) --- (continued)

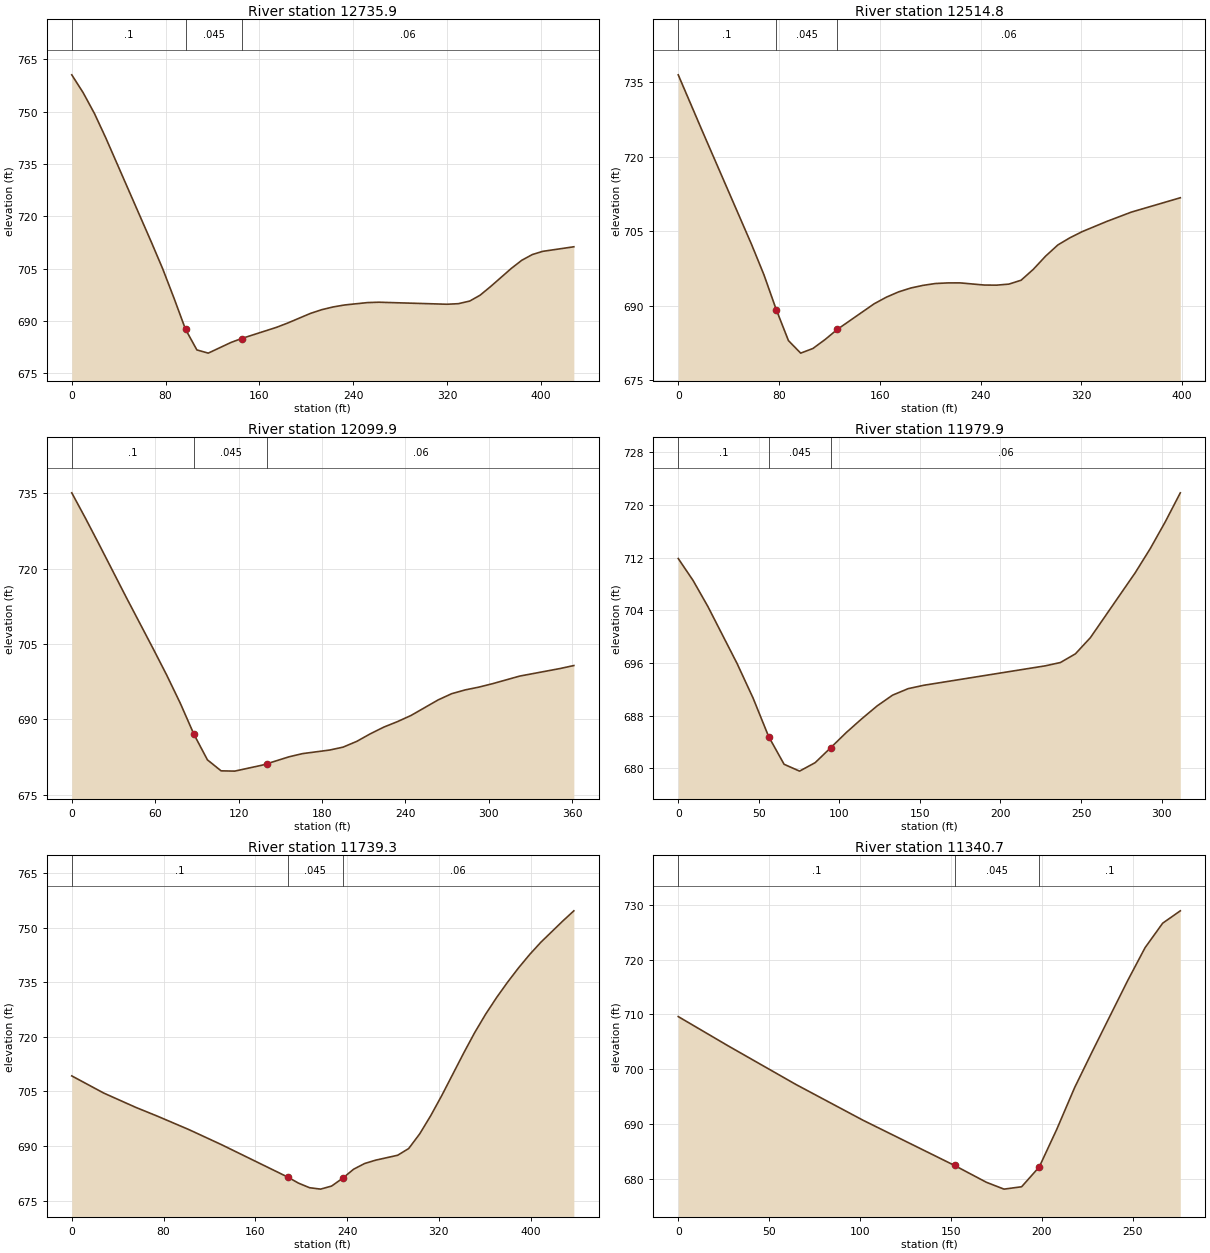
Type RM Length L Ch R = 1 ,12735.9 ,248.8,221.1,192.9
XS GIS Cut Line= 3
     1568118.448      352665.037     1568233.032      352984.482
     1568239.976      353073.023
#Sta/Elev= 30
       0  760.55     9.7  755.44    19.4  749.43    29.1  742.41    67.9  712.59
    77.6  704.92    87.3  696.45      97  687.63   106.7  681.71   116.4  680.79
   135.8  683.85   144.8  684.97   174.5  688.17   184.2  689.42   203.6  692.18
   213.3  693.25     223  694.03   232.7  694.59   252.1  695.27   261.8  695.38
     320   694.8   329.7  694.96   339.4  695.71   348.2  697.38   357.1  699.84
   374.9  705.08   383.8   707.4   392.7  709.03   401.5  709.95   428.2  711.27
#Mann= 3 , 0 , 0
       0      .1       0      97    .045       0   144.8     .06       0
Bank Sta=97,144.8
XS Rating Curve= 0 ,0
Exp/Cntr=0.3,0.1

Type RM Length L Ch R = 1 ,12514.8 ,446.1,414.8,384
XS GIS Cut Line= 2
     1567912.141       352843.22     1568224.641      353090.616
#Sta/Elev= 30
       0  736.51    19.4  725.02    58.3   702.3      68  696.27    77.8  689.24
    87.5  682.98    97.2  680.46   106.9  681.39   116.7  683.22   126.4  685.26
   155.5  690.39   165.3  691.74     175   692.8   184.7  693.58   194.4  694.11
   204.2  694.48   213.9   694.6   223.6  694.61     243  694.17   252.8  694.15
   262.5  694.36   272.2  695.14   281.9  697.34   291.6  699.98   301.4  702.25
   311.1  703.71   320.8  704.94   340.2  706.98   359.7  708.86   398.6  711.75
#Mann= 3 , 0 , 0
       0      .1       0    77.8    .045       0   126.4     .06       0
Bank Sta=77.8,126.4
XS Rating Curve= 0 ,0
Exp/Cntr=0.3,0.1

Type RM Length L Ch R = 1 ,12099.9 ,110.5,120,120.2
XS GIS Cut Line= 2
     1567788.443      353297.647      1568149.12      353317.179
#Sta/Elev= 30
       0  735.05     9.8  730.03    19.5  724.89      39  714.38    58.6  704.04
    68.3  698.82    78.1  693.21    87.9  687.04    97.6  681.97   107.4  679.79
   117.2  679.73   136.7   680.9   140.8  681.23   156.2  682.57     166  683.21
   185.5  683.92   195.2   684.5     205  685.64   214.8  687.15   224.5  688.48
   234.3  689.57   244.1   690.8   263.6  693.89   273.3  695.12   283.1  695.88
   292.9  696.43   302.6   697.1   322.2  698.62   351.4  700.13   361.2  700.72
#Mann= 3 , 0 , 0
       0      .1       0    87.9    .045       0   140.8     .06       0
Bank Sta=87.9,140.8
XS Rating Curve= 0 ,0
Exp/Cntr=0.3,0.1

Type RM Length L Ch R = 1 ,11979.9 ,224.4,240.6,266
XS GIS Cut Line= 4
     1567828.807      353401.814     1567860.057      353421.345
     1568013.703       353430.46      1568117.87      353491.658
#Sta/Elev= 24
       0  711.85     9.2  708.52    18.4  704.56    36.6  695.86    46.5  690.62
    56.1  684.81    65.7  680.59    75.3  679.55      85  680.84    94.6   683.1
   104.2  685.39   113.8  687.48   123.4  689.45     133  691.09   142.7  692.08
   152.3  692.59   227.9  695.55   237.2  696.05   246.5  697.37   255.8  699.83
   283.7  709.72     293  713.38   302.3  717.44   311.6  721.83
#Mann= 3 , 0 , 0
       0      .1       0    56.1    .045       0    94.6     .06       0
Bank Sta=56.1,94.6
XS Rating Curve= 0 ,0
Exp/Cntr=0.3,0.1

Type RM Length L Ch R = 1 ,11739.3 ,355.9,398.6,440.7
XS GIS Cut Line= 3
     1567740.266      353513.793     1567813.182      353610.147
     1568082.713      353776.814
#Sta/Elev= 30
       0  709.25    27.9  704.53    55.8   700.6    74.4  698.22   102.2  694.48
   130.4  690.37   188.1  681.47   197.7  679.77   207.3  678.52   216.9  678.13
   226.5  678.97   236.1  681.11   245.7   683.6   255.3  685.17   264.9  686.09
   284.1  687.44   293.7  689.28   303.3  693.31   312.9   698.3   322.5  703.82
   341.7  715.55   351.3  721.17   360.9  726.26   370.5  730.85   380.1  735.08
   389.7  739.02   399.3  742.66   408.9  745.97   428.1  751.83   437.7  754.62
#Mann= 3 , 0 , 0
       0      .1       0   188.1    .045       0   236.1     .06       0
Bank Sta=188.1,236.1
XS Rating Curve= 0 ,0
Exp/Cntr=0.3,0.1

Type RM Length L Ch R = 1 ,11340.7 ,408.9,370.7,332.7
XS GIS Cut Line= 3
     1567546.255      353664.835     1567569.693      353763.793
     1567599.641      353935.668
#Sta/Elev= 16
       0  709.62    27.7  704.24    64.7  697.26   101.7  690.73     152   682.5
   169.5  679.44   179.2  678.19   188.9  678.62   198.6  682.23   208.3  689.13
     218  696.64   227.7  703.21   247.1  716.08   256.8  722.16   266.5  726.63
   276.2  728.88
#Mann= 3 , 0 , 0
       0      .1       0     152    .045       0   198.6      .1       0
Bank Sta=152,198.6
XS Rating Curve= 0 ,0
Exp/Cntr=0.3,0.1

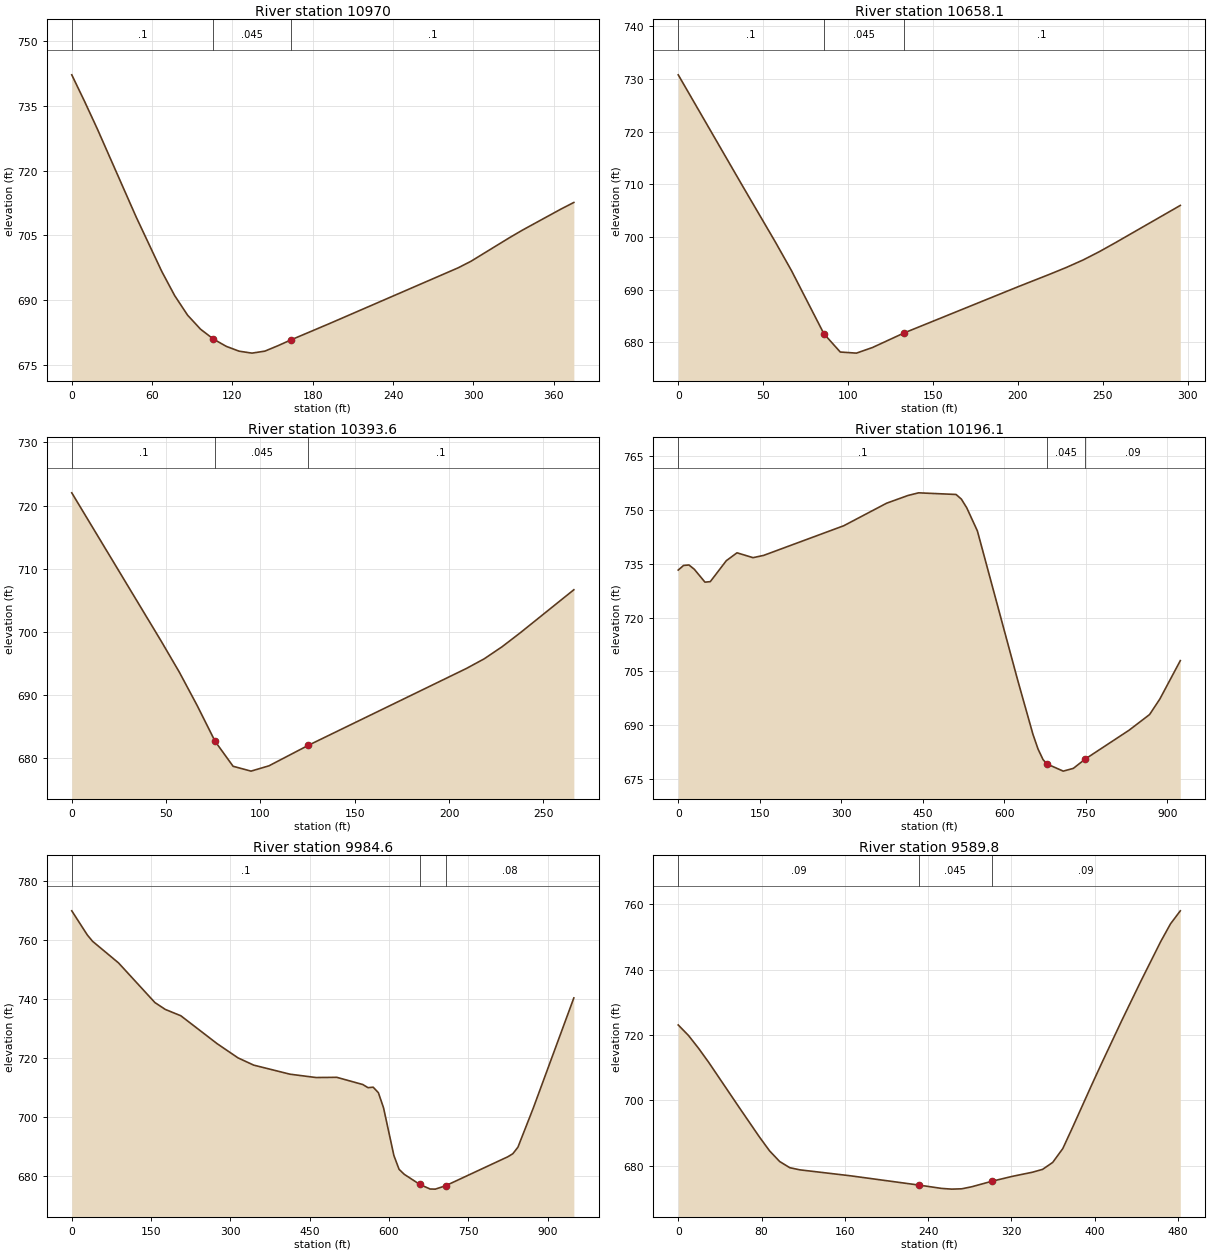
Type RM Length L Ch R = 1 ,10970   ,343.5,311.9,279.8
XS GIS Cut Line= 2
     1567125.682       353836.71     1567426.463      354060.668
#Sta/Elev= 22
       0  742.22     9.6  736.04    19.2  729.61    48.1  709.28    67.3  696.62
    76.9  691.05    86.5  686.54    96.2  683.28   105.8     681   115.4  679.31
     125  678.19   134.6  677.74   144.2   678.2   153.8  679.43   163.5  680.78
   192.3  684.56   288.5  697.49   298.1  699.01   326.9  704.48   336.5  706.22
   365.4  711.12     375  712.65
#Mann= 3 , 0 , 0
       0      .1       0   105.8    .045       0   163.5      .1       0
Bank Sta=105.8,163.5
XS Rating Curve= 0 ,0
Exp/Cntr=0.3,0.1

Type RM Length L Ch R = 1 ,10658.1 ,282.5,264.6,246.5
XS GIS Cut Line= 2
     1567089.224      354220.824     1567384.797      354223.429
#Sta/Elev= 16
       0  730.79    38.1  709.55    57.2  699.02    66.7  693.58    85.8  681.58
    95.4  678.13   104.9  677.92   114.4  678.99   132.8  681.73   200.2  690.55
   219.3  692.98   228.8  694.24   238.4  695.62   247.9  697.19   257.4   698.9
   295.6  705.98
#Mann= 3 , 0 , 0
       0      .1       0    85.8    .045       0   132.8      .1       0
Bank Sta=85.8,132.8
XS Rating Curve= 0 ,0
Exp/Cntr=0.3,0.1

Type RM Length L Ch R = 1 ,10393.6 ,201.1,197.4,193.6
XS GIS Cut Line= 2
     1567141.307      354513.793     1567391.307      354422.647
#Sta/Elev= 14
       0  722.01    47.5  698.44      57  693.58    66.5  688.26      76  682.59
    85.5  678.65      95  677.88   104.5  678.72   125.3  681.96   209.1  694.15
   218.6  695.69   228.1  697.61   237.6  699.79   266.1  706.64
#Mann= 3 , 0 , 0
       0      .1       0      76    .045       0   125.3      .1       0
Bank Sta=76,125.3
XS Rating Curve= 0 ,0
Exp/Cntr=0.3,0.1

Type RM Length L Ch R = 1 ,10196.1 ,221.2,211.5,201.4
XS GIS Cut Line= 5
      1566617.87      354877.074      1567124.38      354660.929
     1567219.432      354698.689     1567354.849      354637.491
     1567445.995       354555.46
#Sta/Elev= 30
       0  733.28     9.8  734.57    19.7   734.7    29.5  733.52    49.2  729.91
      59  730.05    88.5   735.9   108.2   738.1   137.7  736.74   157.3  737.38
   304.8  745.66   383.5  751.94   422.9   754.1   442.5  754.84   511.4  754.38
   521.2  753.08     531  750.69   550.7  744.19   625.1  702.42     653  687.41
   662.3  683.33   671.6  680.36   678.9  679.15   708.7  677.16   727.3  677.93
   748.9   680.5   829.9  688.58   867.6  692.95   886.5  697.28   924.2     708
#Mann= 3 , 0 , 0
       0      .1       0   678.9    .045       0   748.9     .09       0
Bank Sta=678.9,748.9
XS Rating Curve= 0 ,0
Exp/Cntr=0.3,0.1

Type RM Length L Ch R = 1 ,9984.6  ,394.7,394.8,395.3
XS GIS Cut Line= 4
     1566762.835      355210.842     1567276.724      354921.345
     1567471.168      354789.401     1567582.279      354732.109
#Sta/Elev= 30
       0  769.98    29.5  761.78    39.3  759.66    88.5  752.32   157.3  738.88
     177  736.55   206.4   734.4   275.2  724.92   314.6  720.12   344.1  717.68
   412.9   714.6     462  713.47   501.4  713.54   550.5   711.1   560.3  710.04
   570.2  710.19     580  708.34   589.8  703.21   609.4  687.02   619.2  682.35
     629  680.66   658.4  677.23   677.9  675.68   687.7  675.64   707.3  676.79
   824.8   686.6   834.4  687.64     844  689.85   872.9  703.04   949.8  740.46
#Mann= 3 , 0 , 0
       0      .1       0   658.4    .045       0   707.3     .08       0
Bank Sta=658.4,707.3
XS Rating Curve= 0 ,0
Exp/Cntr=0.3,0.1

Type RM Length L Ch R = 1 ,9589.8  ,269.6,262.9,249.8
XS GIS Cut Line= 4
     1567276.724      355369.262     1567356.585      355332.804
     1567587.488      355171.345     1567700.335      355169.609
#Sta/Elev= 30
       0  723.03     9.8  719.84    19.5  715.91    29.3  711.58    58.5  697.82
      78  688.75    87.8  684.48    97.5  681.22   107.2  679.34   116.9  678.68
   165.5  676.86     231  674.03     253     673   262.7  672.78   272.4  672.88
   282.1  673.51     301  675.16     321  676.69   340.4  677.96   350.1  678.83
   359.8  680.96   369.5   685.2     379  691.76   397.8  705.06   407.2  711.56
     426  724.29   444.8  736.64   463.6  748.59     473     754   482.4  757.98
#Mann= 3 , 0 , 0
       0     .09       0     231    .045       0     301     .09       0
Bank Sta=231,301
XS Rating Curve= 0 ,0
Exp/Cntr=0.3,0.1

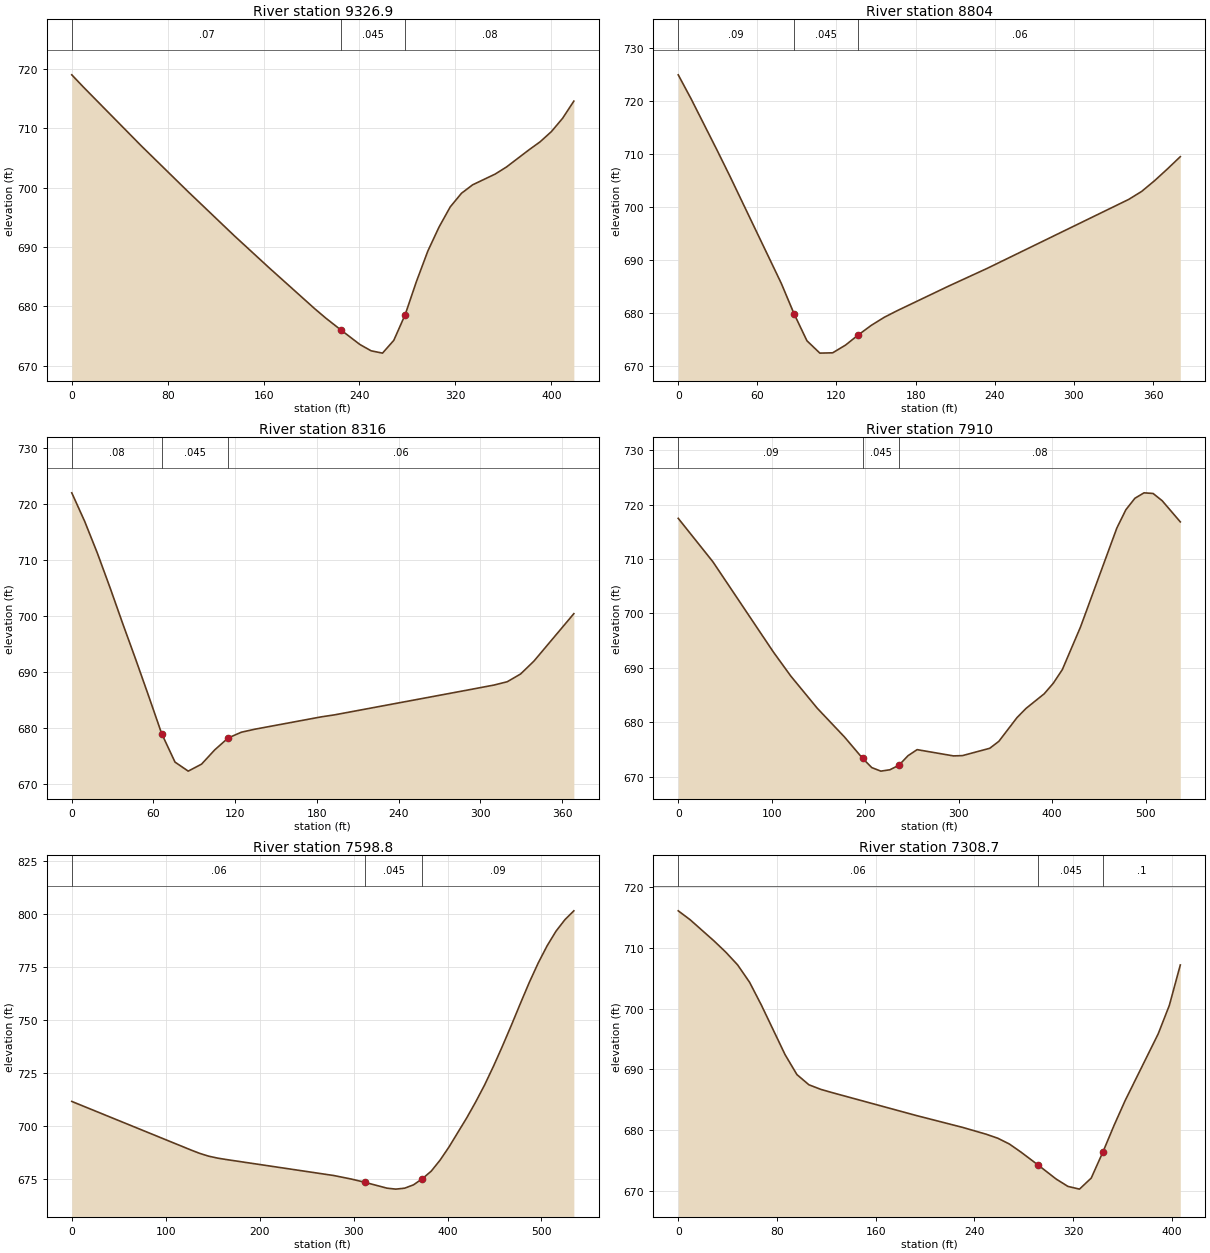
Type RM Length L Ch R = 1 ,9326.9  ,573.7,522.8,477.6
XS GIS Cut Line= 4
     1567492.002      355697.387     1567542.349       355530.72
     1567632.627      355447.387     1567698.599      355344.956
#Sta/Elev= 27
       0  719.03     9.7  716.97      58  707.06    96.7  699.41   135.4  691.95
   164.4  686.56   202.5  679.65   211.9  678.04   224.9  675.98   240.3   673.6
   249.7  672.53   259.2  672.14   268.6  674.29   278.1  678.62   287.5  684.21
     297  689.33   306.3  693.36   315.7  696.78   325.1  699.08   334.4   700.5
   353.2  702.31   362.6   703.5   381.3  706.38   390.7  707.75   400.1  709.47
   409.4   711.7   418.8   714.6
#Mann= 3 , 0 , 0
       0     .07       0   224.9    .045       0   278.1     .08       0
Bank Sta=224.9,278.1
XS Rating Curve= 0 ,0
Exp/Cntr=0.3,0.1

Type RM Length L Ch R = 1 ,8804    ,506.9,488,473.9
XS GIS Cut Line= 2
     1568052.766      355726.901     1567978.113      355353.637
#Sta/Elev= 21
       0  724.88     9.8  720.34    29.3  710.77      39   705.9    78.1  685.66
    87.8  679.93    97.6  674.83   107.4  672.51   117.1  672.57   126.9  674.03
   136.6  675.95   146.4  677.74   156.2  679.25   165.9  680.48     205  685.12
   234.2  688.45   341.6  701.44   351.4  702.94   361.1  704.94   370.9  707.16
   380.7  709.48
#Mann= 3 , 0 , 0
       0     .09       0    87.8    .045       0   136.6     .06       0
Bank Sta=87.8,136.6
XS Rating Curve= 0 ,0
Exp/Cntr=0.3,0.1

Type RM Length L Ch R = 1 ,8316    ,399.2,406.1,408
XS GIS Cut Line= 4
     1568537.141       355530.72     1568498.946      355476.901
     1568427.766      355338.012     1568351.377      355213.012
#Sta/Elev= 23
       0  722.01     9.4  716.97    18.9  711.19    28.3  704.96    37.7  698.49
    47.1   692.2    56.6  685.66      66  679.07    75.8  673.99    85.5  672.38
    95.3  673.63     105  676.18   114.8  678.29   124.5  679.32   134.3  679.85
     183  682.05   192.8  682.41   290.4  686.83     310  687.73   319.7  688.32
   329.5   689.7   339.3     692   368.6  700.46
#Mann= 3 , 0 , 0
       0     .08       0      66    .045       0   114.8     .06       0
Bank Sta=66,114.8
XS Rating Curve= 0 ,0
Exp/Cntr=0.3,0.1

Type RM Length L Ch R = 1 ,7910    ,257.2,311.2,365.6
XS GIS Cut Line= 4
     1568854.849      355469.956     1568877.418      355332.804
     1568762.835      355086.276     1568780.196      354961.276
#Sta/Elev= 30
       0  717.47    37.1  709.48   101.9  692.87   120.5  688.46   148.7  682.57
   177.8  677.29   197.2  673.36     207  671.66   216.7  671.01   226.4  671.26
   236.1   672.1   245.8  673.85   255.5  674.96   294.3  673.81     304  673.86
   333.2  675.21   342.9  676.48   362.3  680.84     372  682.54   391.4  685.22
   401.1  687.15   410.8  689.67   430.3  697.52   469.1  715.68   478.8  719.06
   488.5  721.17   498.2  722.16   507.9  722.04   517.6  720.71     537  716.82
#Mann= 3 , 0 , 0
       0     .09       0   197.2    .045       0   236.1     .08       0
Bank Sta=197.2,236.1
XS Rating Curve= 0 ,0
Exp/Cntr=0.3,0.1

Type RM Length L Ch R = 1 ,7598.8  ,270.9,290.1,296.9
XS GIS Cut Line= 4
     1568952.071       355490.79     1569049.293      355322.387
     1569165.613      355162.665     1569268.043      355063.706
#Sta/Elev= 30
       0  711.73   126.4  688.92   136.1  687.25   145.8  685.91   155.6  684.97
   165.3  684.28   279.1  676.78     298  675.09   312.6  673.53   335.6  670.83
     345  670.38   354.4  670.83   363.8   672.4   373.2  675.29   382.6  678.82
     392  683.99   401.5  690.19   420.5     704     430  711.48   439.5   719.5
     449  728.37   458.5  737.82     468  747.66   477.5  757.82     487  767.76
   496.5  776.93     506  785.07   515.5  791.98     525  797.42   534.5  801.59
#Mann= 3 , 0 , 0
       0     .06       0   312.6    .045       0   373.2     .09       0
Bank Sta=312.6,373.2
XS Rating Curve= 0 ,0
Exp/Cntr=0.3,0.1

Type RM Length L Ch R = 1 ,7308.7  ,200,210.2,231.4
XS GIS Cut Line= 4
     1569007.627      355542.873     1569203.807      355494.262
     1569323.599      355417.873     1569365.266      355370.998
#Sta/Elev= 29
       0   716.1     9.6  714.64    28.9  711.16    38.5   709.3    48.1   707.2
    57.8  704.34    67.4  700.56    86.6   692.4    96.2  689.12   105.9  687.44
   115.5  686.69   125.1  686.13   192.5   682.4   230.5  680.42   249.5   679.3
   258.9  678.64   268.4  677.68   277.9  676.33   291.6  674.23   306.3  671.91
   315.8   670.7   325.2  670.25   334.7  672.07   344.2  676.38   353.2  680.75
   362.1   684.8     389  695.84     398  700.52   406.9  707.18
#Mann= 3 , 0 , 0
       0     .06       0   291.6    .045       0   344.2      .1       0
Bank Sta=291.6,344.2
XS Rating Curve= 0 ,0
Exp/Cntr=0.3,0.1

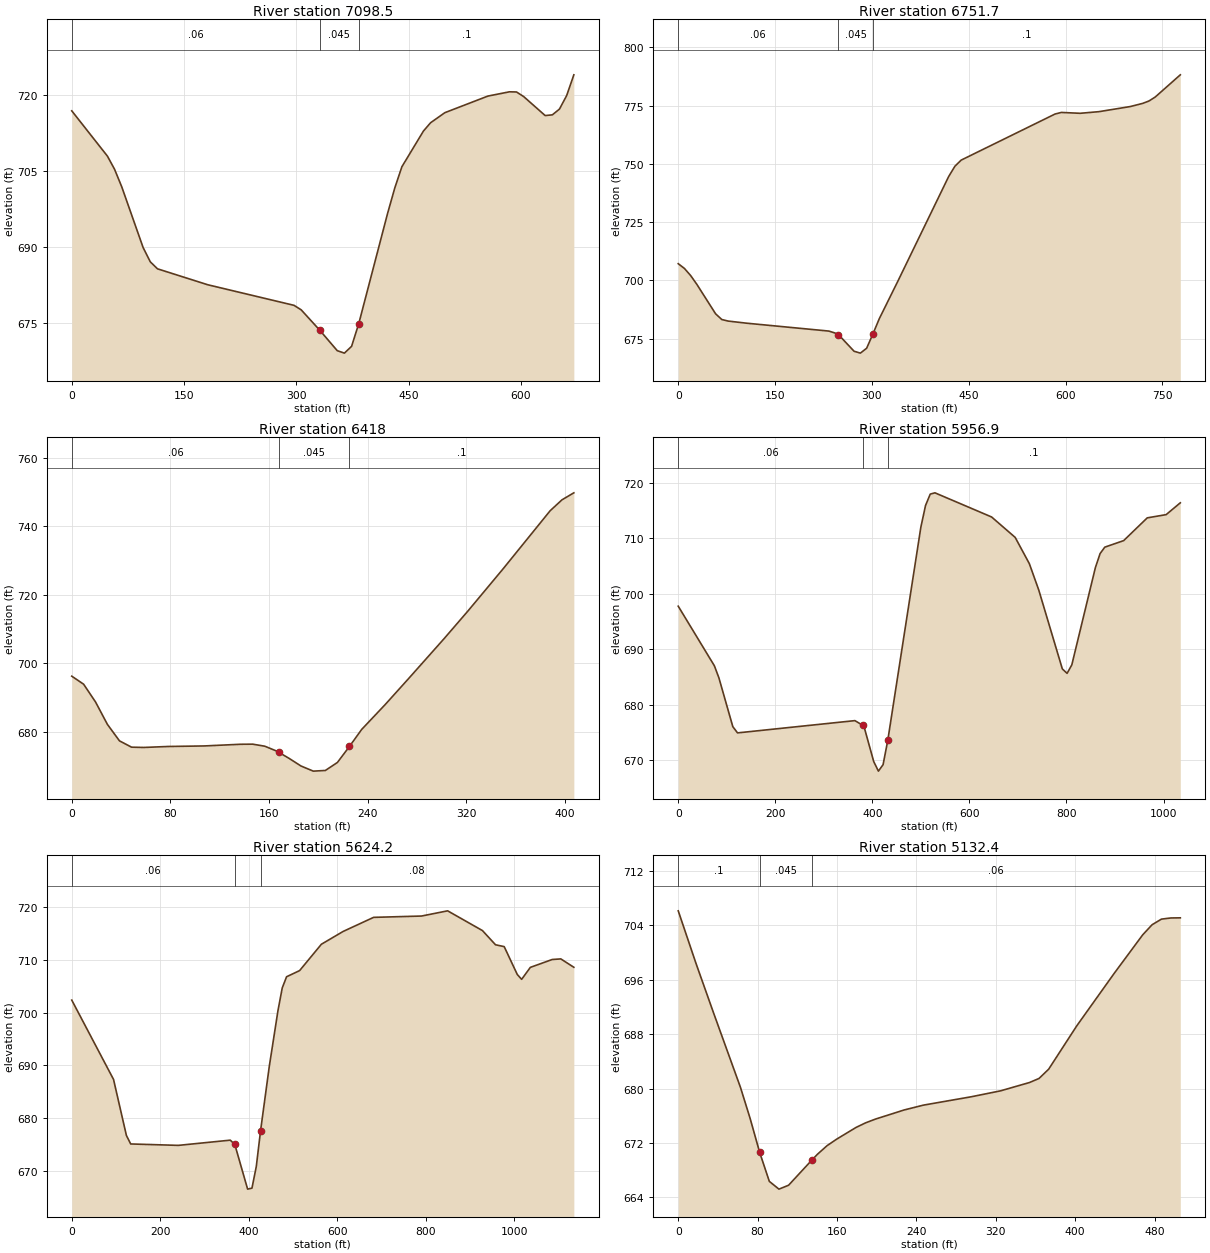
Type RM Length L Ch R = 1 ,7098.5  ,306.9,346.7,386.2
XS GIS Cut Line= 5
     1569035.404      355683.498     1569139.571      355695.651
     1569252.418      355673.081     1569450.335      355598.429
     1569561.446      355386.623
#Sta/Elev= 30
       0  716.91    47.7  707.97    57.2  705.38    66.7  701.96    95.3  689.97
   104.9  687.15   114.5  685.77   181.6  682.63   296.9  678.57   306.5  677.68
   331.2  673.68   354.6  669.64   364.2  669.15   373.8  670.49   383.4  674.97
   421.9   696.7   431.5   701.7     441  705.89   469.8  712.93   479.3  714.56
   498.4  716.55   555.9  719.82   584.6  720.66   594.1  720.63   603.7  719.72
   632.4  715.98     642  716.12   651.5  717.26   661.1  719.92   670.7  724.01
#Mann= 3 , 0 , 0
       0     .06       0   331.2    .045       0   383.4      .1       0
Bank Sta=331.2,383.4
XS Rating Curve= 0 ,0
Exp/Cntr=0.3,0.1

Type RM Length L Ch R = 1 ,6751.7  ,323.3,333.7,352.4
XS GIS Cut Line= 4
     1569085.752      355858.845     1569170.821      355876.206
     1569481.585      356018.567     1569830.543      356008.151
#Sta/Elev= 30
       0  707.14     9.6  705.09    19.3  702.02    28.9  698.24    57.9  685.61
    67.5  683.16    77.2   682.5   106.4  681.57   233.3   678.2   243.1  677.35
   248.1   676.3   252.8  675.32   272.4  669.54   282.2  668.73   291.9  670.84
   301.7  677.02   311.4  683.47   340.8  699.94   418.9  744.54   428.6  748.98
   438.3  751.61   583.8  771.41   593.5  772.09   622.6  771.72   651.7  772.42
   700.2  774.61   719.6  775.98   729.3  777.01     739  778.72   777.8  788.24
#Mann= 3 , 0 , 0
       0     .06       0   248.1    .045       0   301.7      .1       0
Bank Sta=248.1,301.7
XS Rating Curve= 0 ,0
Exp/Cntr=0.3,0.1

Type RM Length L Ch R = 1 ,6418    ,427.4,461.1,489.8
XS GIS Cut Line= 4
     1569056.238      356134.887     1569071.863      356159.192
     1569238.529       356280.72     1569327.071       356428.29
#Sta/Elev= 29
       0  696.23     9.6  693.89    19.3  688.68    28.9  682.15    38.7  677.33
    48.5  675.48    58.4   675.4      78  675.68   107.5  675.84   136.9  676.33
   146.8  676.36   156.6  675.76   166.4  674.31   168.1  673.95   176.2  672.23
     186  669.97   195.9  668.48   205.7  668.67   215.5  671.01   225.3  675.71
   235.2  680.67   254.3  687.95   273.4  695.59   302.1  707.22   321.2   715.2
   349.9   727.6   388.1  744.59   397.7  747.78   407.3  749.82
#Mann= 3 , 0 , 0
       0     .06       0   168.1    .045       0   225.3      .1       0
Bank Sta=168.1,225.3
XS Rating Curve= 0 ,0
Exp/Cntr=0.3,0.1

Type RM Length L Ch R = 1 ,5956.9  ,294.7,332.7,366
XS GIS Cut Line= 4
     1568745.474      356150.512     1568787.141      356233.845
     1568877.418      356560.234     1568967.544      357156.234
#Sta/Elev= 30
       0  697.72    74.5  686.98    83.8  684.81   112.5  676.01   122.2  674.89
   364.1   677.1   379.9  676.27   383.4  675.85   402.8  669.73   412.5     668
   422.1  669.16   431.8  673.54   499.9  711.93   509.6  715.87   519.3  717.92
     529  718.15   645.7   713.8   694.3  710.12   723.5  705.39   742.9  700.64
   791.5  686.42   801.3  685.62     811  687.14   859.6  704.67   869.3   707.2
     879  708.36   917.9  709.54   966.5  713.64  1005.4  714.22  1034.6  716.35
#Mann= 3 , 0 , 0
       0     .06       0   379.9    .045       0   431.8      .1       0
Bank Sta=379.9,431.8
XS Rating Curve= 0 ,0
Exp/Cntr=0.3,0.1

Type RM Length L Ch R = 1 ,5624.2  ,543,491.8,445
XS GIS Cut Line= 4
     1568689.918      356134.887     1568707.279      356237.317
     1568530.196      356586.276     1568774.836      357177.067
#Sta/Elev= 30
       0   702.4    94.4  687.35   123.5  676.71   133.2  675.11   240.8  674.84
   358.2  675.83   368.4  675.02   397.4  666.54   407.2  666.73     417  670.83
   426.7  677.65   446.3  689.79   465.9  700.37   475.6   704.7   485.4  706.83
   514.9     708   564.1     713   613.3  715.43   682.1   718.1   790.3  718.35
   849.4  719.34   928.1  715.59   957.6   712.9   977.2  712.55  1006.8  707.26
  1016.6  706.34  1036.3  708.61  1085.5   710.1  1105.1  710.22  1134.6  708.63
#Mann= 3 , 0 , 0
       0     .06       0   368.4    .045       0   426.7     .08       0
Bank Sta=368.4,426.7
XS Rating Curve= 0 ,0
Exp/Cntr=0.3,0.1

Type RM Length L Ch R = 1 ,5132.4  ,454.7,435.4,409.7
XS GIS Cut Line= 4
     1568057.974      356299.817     1568104.849      356341.484
     1568240.266      356620.998     1568337.488      356711.276
#Sta/Elev= 30
       0  706.13    17.9   698.4    35.8  691.04    62.7  680.18    72.4  675.63
    82.1   670.6    91.8  666.35   101.5  665.21   111.2  665.78   134.4  669.44
   140.4  670.35   150.1  671.61   159.8  672.57   179.2  674.28   188.9  674.96
   198.6   675.5   227.7  676.85   247.1  677.56   295.7   678.8   324.8  679.66
   353.9  680.88   363.6  681.48   373.3  682.84   401.7  689.23   439.6  696.98
   468.1   702.6   477.6  704.09     487  704.91   496.5  705.08     506   705.1
#Mann= 3 , 0 , 0
       0      .1       0    82.1    .045       0   134.4     .06       0
Bank Sta=82.1,134.4
XS Rating Curve= 0 ,0
Exp/Cntr=0.3,0.1

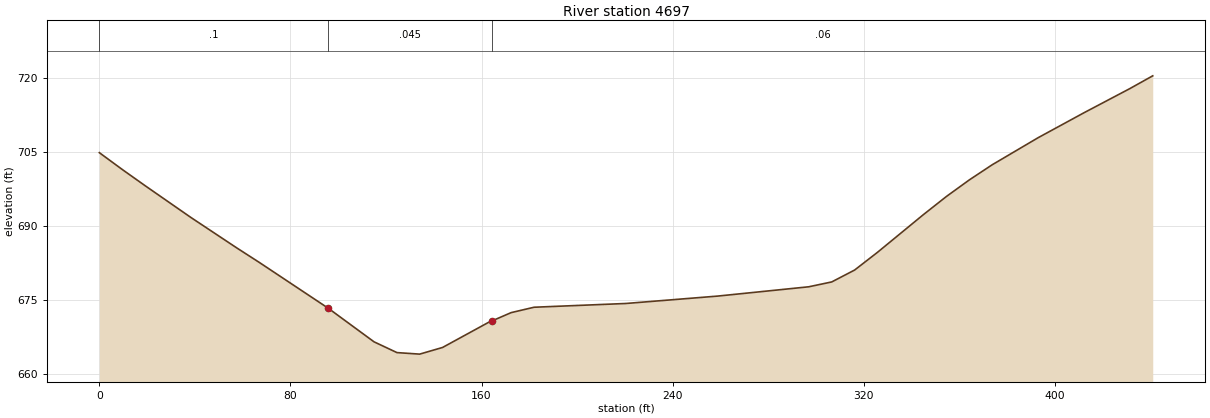
Type RM Length L Ch R = 1 ,4697    ,293.4,286.7,279.4
XS GIS Cut Line= 3
     1567783.668      356648.776     1568047.557      356839.748
     1568117.002      356931.762
#Sta/Elev= 29
       0  704.86     9.6  701.45    19.2  698.16    38.3  691.75    57.5  685.59
    67.1   682.6    95.8  673.38     115  666.57   124.6  664.39   134.1  664.08
   143.7  665.43   162.9   670.5   164.5  670.83   172.4  672.48     182  673.57
   220.4  674.33   258.7  675.82     297  677.71   306.6  678.69   316.2   681.1
   325.7  684.66     345  692.32   354.6  695.98   364.2  699.34   373.8  702.41
     393  707.88   412.2  712.93   431.4  717.82     441  720.41
#Mann= 3 , 0 , 0
       0      .1       0    95.8    .045       0   164.5     .06       0
Bank Sta=95.8,164.5
XS Rating Curve= 0 ,0
Exp/Cntr=0.3,0.1