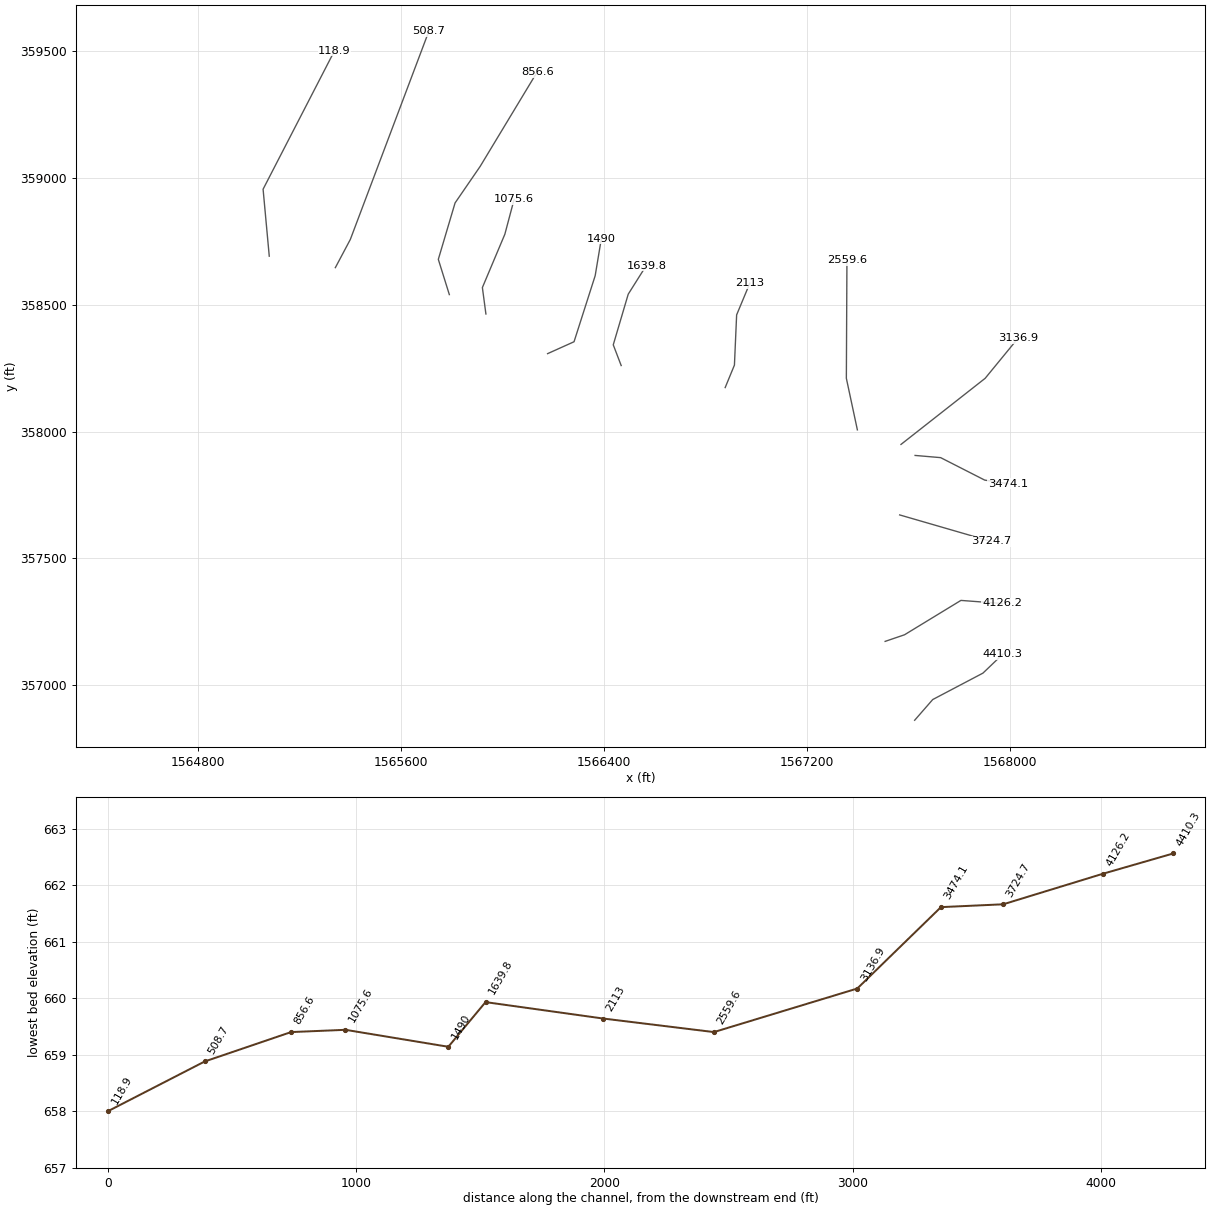
HEC-RAS study SNCHOCRK.prj: SNCHOCRK

--- SNCHOCRK.g02 (geometry) --- (continued)

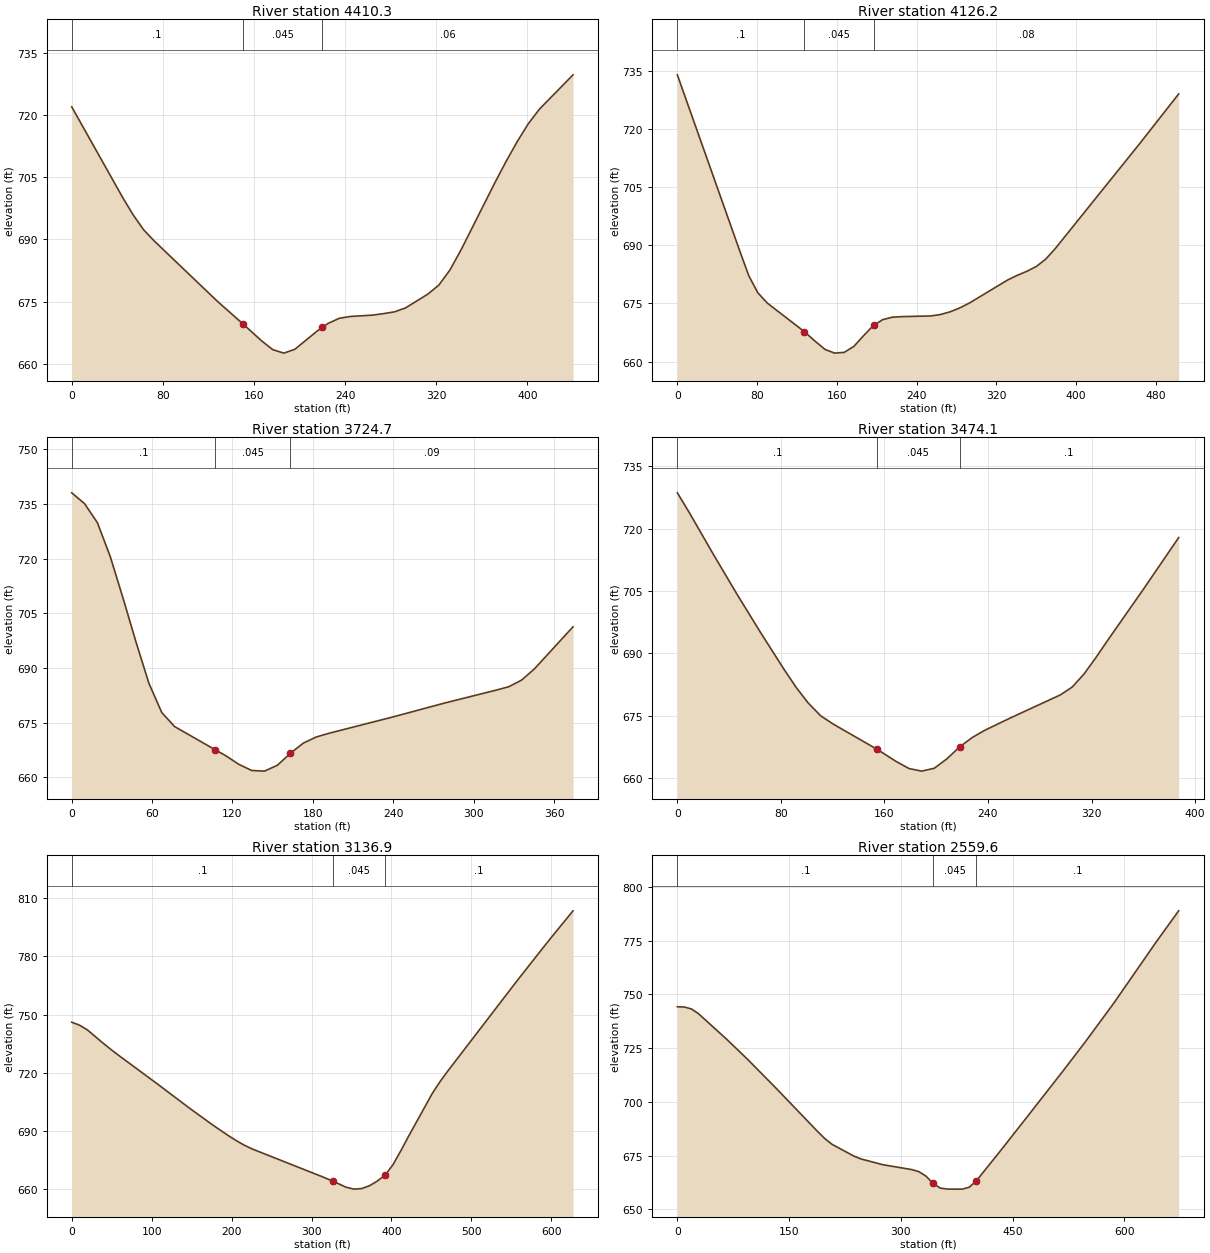
Type RM Length L Ch R = 1 ,4410.3  ,281.1,284.2,287.6
XS GIS Cut Line= 4
     1567623.946      356862.317     1567695.127      356943.915
     1567893.043      357048.081     1567971.168      357122.734
#Sta/Elev= 30
       0  721.97    45.1  699.91    54.1  695.84    63.2  692.28    72.2  689.68
   127.7   675.1   150.1  669.65   166.6  665.54   176.4  663.41   186.1  662.56
   195.8  663.48   215.2  667.84   220.1  668.78     225  669.72   234.7  670.95
   244.4   671.4   263.9  671.72   273.6  672.08   283.3  672.52     293  673.47
   312.5  676.78   322.2  678.96   331.9  682.59   341.8  687.51   371.2  703.56
     381  708.68   390.9  713.53   400.7  717.88   410.5  721.41     440  729.69
#Mann= 3 , 0 , 0
       0      .1       0   150.1    .045       0   220.1     .06       0
Bank Sta=150.1,220.1
XS Rating Curve= 0 ,0
Exp/Cntr=0.3,0.1

Type RM Length L Ch R = 1 ,4126.2  ,442.6,401.5,359
XS GIS Cut Line= 4
     1567507.627      357173.081     1567584.016      357199.123
     1567806.238       357334.54     1567967.696      357322.387
#Sta/Elev= 30
       0  733.92    62.8  688.39    71.7  682.12    80.7  677.76    90.3  675.08
   127.5  667.72   138.5   665.2   148.2  663.15   157.8   662.2   167.4   662.4
   177.1  663.94   186.7  666.67   196.4  669.26   197.5  669.44     206  670.83
   215.6  671.46   225.3  671.61   254.2  671.78   263.8  672.14   273.5  672.84
   283.1  673.83   292.8  675.09   331.3  681.05   340.9  682.24   350.5  683.28
     360  684.52   369.5  686.42     379  689.13   464.8  716.54   502.8  728.99
#Mann= 3 , 0 , 0
       0      .1       0   127.5    .045       0   197.5     .08       0
Bank Sta=127.5,197.5
XS Rating Curve= 0 ,0
Exp/Cntr=0.3,0.1

Type RM Length L Ch R = 1 ,3724.7  ,259.9,250.6,241.2
XS GIS Cut Line= 2
     1567564.918      357671.345     1567924.293      357567.179
#Sta/Elev= 26
       0  738.07     9.6  735.09    19.2  729.85    28.8  720.53    38.4  709.03
      48  697.08    57.6   685.8    67.2  677.75    76.8  673.89   106.8  667.59
   115.1  665.87   124.7  663.53   134.3  661.84   143.9  661.66   153.5  663.27
   163.1   666.5   172.7  669.31   182.3     671   191.9  672.04   239.8  676.54
   278.2  680.34   316.6  683.88   326.2  684.83   335.8  686.65   345.4  689.74
   374.2  701.29
#Mann= 3 , 0 , 0
       0      .1       0   106.8    .045       0   163.1     .09       0
Bank Sta=106.8,163.1
XS Rating Curve= 0 ,0
Exp/Cntr=0.3,0.1

Type RM Length L Ch R = 1 ,3474.1  ,279.8,337.2,394.3
XS GIS Cut Line= 4
     1567625.682       357905.72     1567726.377       357897.04
     1567899.988      357808.498     1567990.266      357794.609
#Sta/Elev= 27
       0  728.63     9.2  723.89    27.6  713.94    45.9  704.31    64.3  694.99
    82.7  685.99    91.9  681.73   101.1  678.02   110.8  674.92   120.6  672.91
   154.4  666.85   169.3  663.89     179  662.23   188.8  661.61   198.5   662.3
   208.3  664.58     218  667.42   227.7  669.68   237.5  671.44     257  674.37
     296  679.98   305.1  681.87   314.2     685   323.4  688.96   332.5  693.12
   359.9  705.33   387.3  717.84
#Mann= 3 , 0 , 0
       0      .1       0   154.4    .045       0     218      .1       0
Bank Sta=154.4,218
XS Rating Curve= 0 ,0
Exp/Cntr=0.3,0.1

Type RM Length L Ch R = 1 ,3136.9  ,531.3,577.3,622.5
XS GIS Cut Line= 3
     1567570.127      357949.123     1567901.724       358209.54
     1568032.084      358368.517
#Sta/Elev= 30
       0  746.08     9.8  744.55    19.6  742.12    39.2  735.32      49  732.08
    58.8  728.99   107.9  714.09   147.1  701.91   176.5  693.15   196.1  687.68
   205.9  685.13   215.7  682.83   225.5  680.89   313.8   666.5   326.7  664.28
   343.2  661.17     353  660.17   362.8  660.45   372.6  661.92   382.4  664.34
   392.2  667.44     402  672.78   411.8  679.95   421.6  687.51     451  709.33
   460.8   715.5   470.6  720.99   558.7  768.22   597.8   788.6   627.2  803.41
#Mann= 3 , 0 , 0
       0      .1       0   326.7    .045       0   392.2      .1       0
Bank Sta=326.7,392.2
XS Rating Curve= 0 ,0
Exp/Cntr=0.3,0.1

Type RM Length L Ch R = 1 ,2559.6  ,448.3,446.6,444.5
XS GIS Cut Line= 3
     1567398.252      358006.415     1567354.849       358209.54
     1567357.171      358674.506
#Sta/Elev= 30
       0  744.28     9.4  744.16    18.9  743.27    28.3   741.1    66.1  729.19
    94.4  719.77   132.2  706.47   188.8  686.03   198.3  682.81   207.7  680.23
   236.8  674.79   246.5  673.44   275.5  670.79   314.3  668.51     324  667.55
   333.6  665.46   343.3  662.04     353  659.86   362.7  659.42   372.4   659.4
   382.1   659.4   391.8   660.3   401.4  663.33   430.5  675.89   469.3  692.99
   517.7  714.47   546.8  727.66   585.5  745.88   643.6  774.95   672.7  788.94
#Mann= 3 , 0 , 0
       0      .1       0   343.3    .045       0   401.4      .1       0
Bank Sta=343.3,401.4
XS Rating Curve= 0 ,0
Exp/Cntr=0.3,0.1

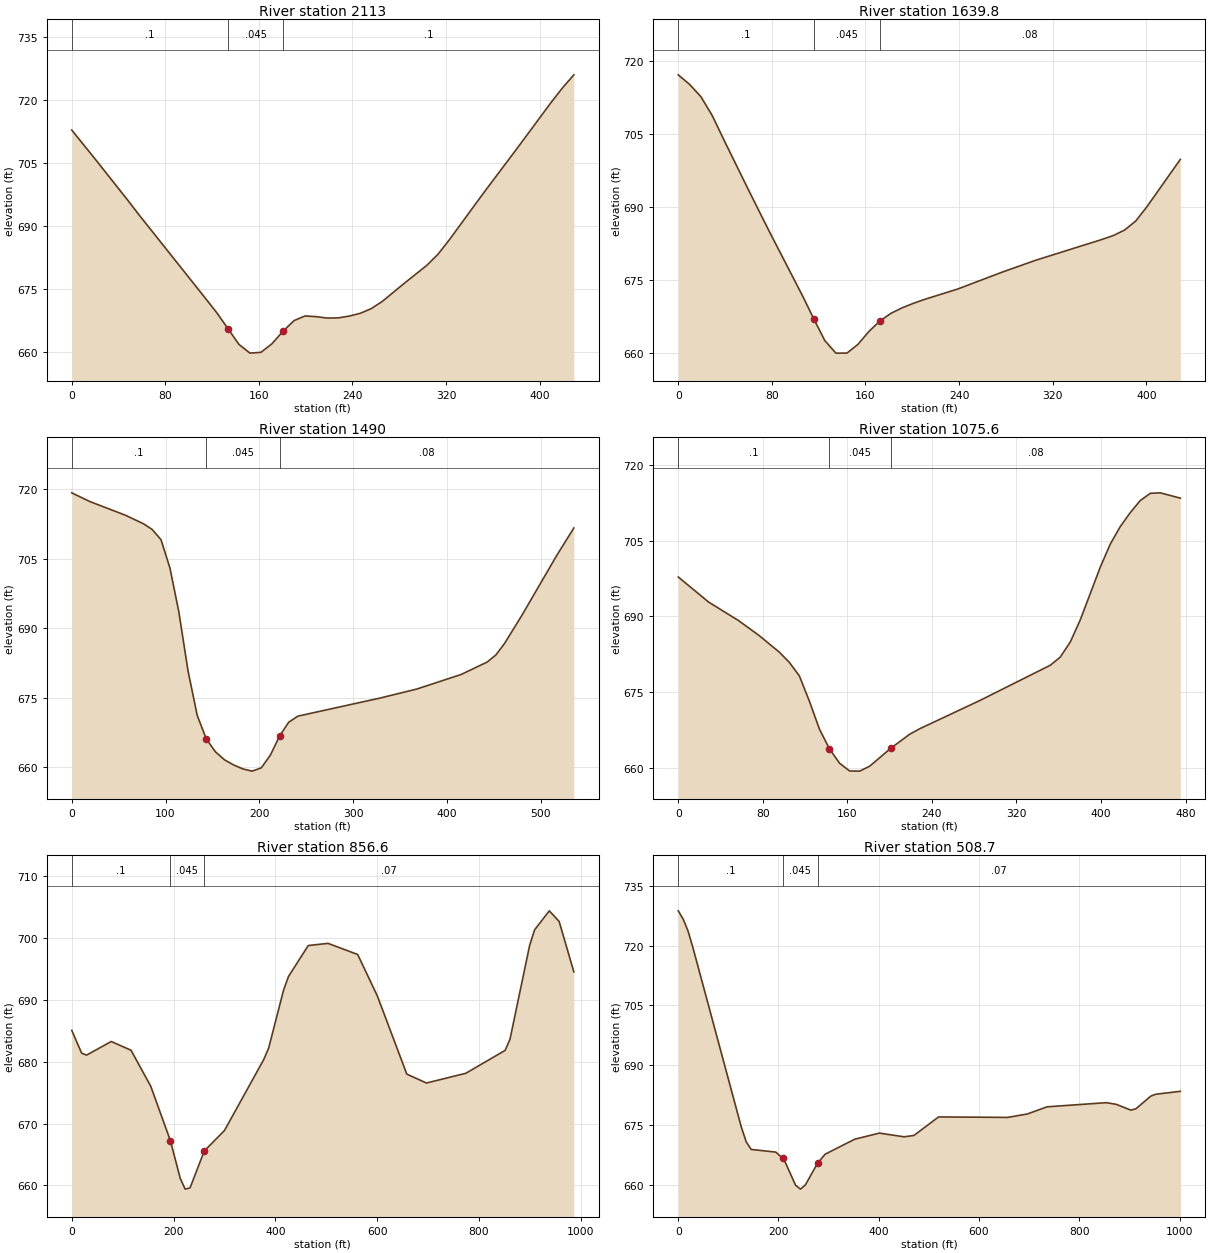
Type RM Length L Ch R = 1 ,2113    ,485.3,473.2,460.8
XS GIS Cut Line= 4
     1566877.418      358173.081     1566913.877      358261.623
     1566922.557       358459.54     1566974.641       358584.54
#Sta/Elev= 30
       0  712.74    19.2  706.13    47.9  696.04    57.4   692.6   114.6  672.59
   124.1  669.22   133.5  665.49   142.9  661.73   152.4  659.64   161.8  659.83
   171.2  661.88   180.7  664.87   190.1  667.39   199.5  668.49     209  668.32
   218.4  667.99   227.8  668.03   237.3  668.46   246.7  669.12   256.1  670.24
   265.6  671.97   284.4  676.28   303.5  680.52   313.2   683.2   322.9  686.64
   351.9  697.69   380.9  708.43   409.9  719.34   419.6  722.79   429.3   725.9
#Mann= 3 , 0 , 0
       0      .1       0   133.5    .045       0   180.7      .1       0
Bank Sta=133.5,180.7
XS Rating Curve= 0 ,0
Exp/Cntr=0.3,0.1

Type RM Length L Ch R = 1 ,1639.8  ,150.9,149.8,148.7
XS GIS Cut Line= 4
     1566467.696      358259.887     1566436.446      358341.484
     1566495.474      358541.137     1566566.654      358653.984
#Sta/Elev= 29
       0   717.1     9.7  715.14    19.4   712.6    29.1  708.71    38.8  703.85
    58.2  694.35      68  689.63    77.7  684.98   106.3  671.66   115.8  666.99
   125.2  662.52   134.7  659.93   144.2  659.94   153.6  661.74   163.1  664.43
   172.5  666.56     182  668.14   191.5  669.25   200.9  670.16   210.4  670.96
   238.8   673.1   276.6  676.55   305.1  678.98   362.3   683.3   371.8  684.09
   381.3   685.2   390.9  687.06   400.4  689.98     429  699.73
#Mann= 3 , 0 , 0
       0      .1       0   115.8    .045       0   172.5     .08       0
Bank Sta=115.8,172.5
XS Rating Curve= 0 ,0
Exp/Cntr=0.3,0.1

Type RM Length L Ch R = 1 ,1490    ,417.9,414.4,409.6
XS GIS Cut Line= 4
     1566177.766      358306.762     1566281.932      358353.637
     1566365.266      358614.054     1566389.571      358759.887
#Sta/Elev= 30
       0  719.27      19  717.41    57.1  714.44    76.2  712.62    85.7  711.37
    95.2  709.14   104.7  703.04   114.2  693.55     124   680.8   133.8  671.19
   143.5  666.08   153.3   663.3     163  661.57   172.8  660.45   182.6  659.61
   192.4  659.14   202.1  659.84   211.9  662.62   221.6  666.72   231.4  669.71
   241.2  671.02   329.1  674.94   368.1  676.88   415.4  680.03   443.1  682.71
   452.3  684.23   461.6  686.73   480.1   692.8     517  705.65   535.5  711.67
#Mann= 3 , 0 , 0
       0      .1       0   143.5    .045       0   221.6     .08       0
Bank Sta=143.5,221.6
XS Rating Curve= 0 ,0
Exp/Cntr=0.3,0.1

Type RM Length L Ch R = 1 ,1075.6  ,213.5,219,224.1
XS GIS Cut Line= 4
      1565934.71      358463.012     1565920.821      358567.179
     1566009.363      358777.248     1566045.821      358914.401
#Sta/Elev= 30
       0  697.81    28.7  692.86    57.3  689.16    76.4  686.26    95.5  682.98
   105.1  680.94   114.6  678.26   124.1  673.26   133.6  667.74   143.1  663.83
   152.6  661.01   162.1  659.47   171.6  659.44   181.1  660.41   201.1  663.96
   219.1  666.75   228.6  667.83   285.6  673.42     352  680.37   361.4  681.97
   370.9  684.95   380.4  689.35   399.3  699.76   408.7  704.29   418.2  707.77
   427.7  710.54   437.1  712.91   446.6  714.34     456  714.44     475  713.39
#Mann= 3 , 0 , 0
       0      .1       0   143.1    .045       0   201.1     .08       0
Bank Sta=143.1,201.1
XS Rating Curve= 0 ,0
Exp/Cntr=0.3,0.1

Type RM Length L Ch R = 1 ,856.6   ,351.6,347.9,344.1
XS GIS Cut Line= 5
     1565790.613      358539.401      1565747.21       358678.29
     1565813.182      358900.512     1565912.141      359044.609
     1566136.678      359416.484
#Sta/Elev= 30
       0  685.05    19.4  681.38    29.1  681.06    77.6  683.26   116.4  681.85
   155.2  676.03   193.8  667.23   213.1  661.15   222.8   659.4   232.4   659.6
   260.4  665.57     300  668.87   377.3  680.36     387  682.24   416.2  691.58
   425.9  693.78   464.7  698.77   503.6  699.12   561.8  697.32   600.4  690.63
   658.3  677.99   696.9  676.55   774.2  678.12   851.4  681.82     861  683.61
   899.6  698.77   909.3   701.3   938.3  704.38   957.6  702.67   986.5  694.52
#Mann= 3 , 0 , 0
       0      .1       0   193.8    .045       0   260.4     .07       0
Bank Sta=193.8,260.4
XS Rating Curve= 0 ,0
Exp/Cntr=0.3,0.1

Type RM Length L Ch R = 1 ,508.7   ,380.8,389.9,384.1
XS GIS Cut Line= 3
     1565341.539      358645.651     1565400.566      358756.762
     1565709.594      359576.206
#Sta/Elev= 30
       0  728.73     9.7  726.69    19.4  723.73      29  719.64   125.8  674.47
   135.7  670.74   145.5  668.84   194.7  668.17     208  666.65   214.4  665.38
   234.1  659.86   243.9  658.88   253.7  659.95     278  665.39   293.1  667.65
   352.1  671.41   401.3  672.94   450.5  672.01   470.2  672.35   519.4     677
   657.2  676.88   696.6  677.75   735.9  679.54     854  680.58   873.7  680.16
   903.2   678.7     913  679.05   942.6  682.21   952.4  682.69  1001.6  683.43
#Mann= 3 , 0 , 0
       0      .1       0     208    .045       0     278     .07       0
Bank Sta=208,278
XS Rating Curve= 0 ,0
Exp/Cntr=0.3,0.1

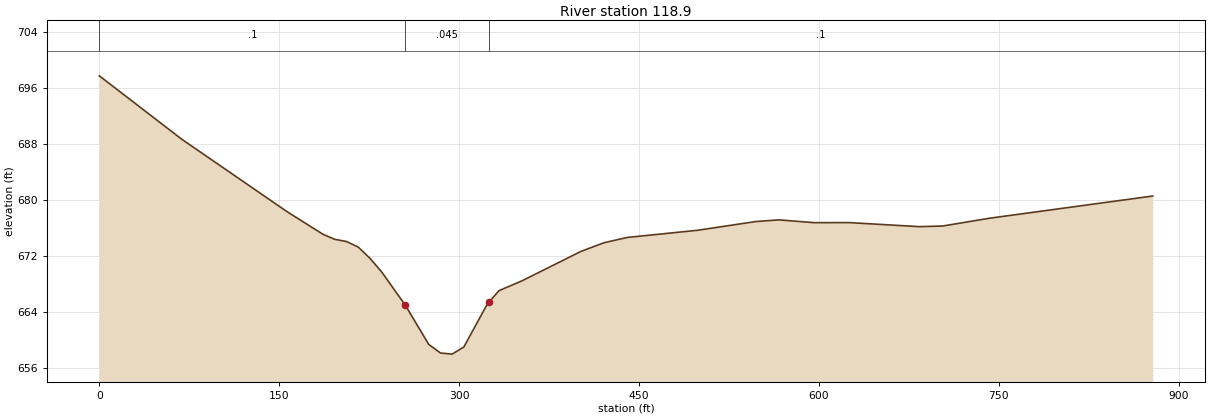
Type RM Length L Ch R = 1 ,118.9   ,126.3,118.9,126.4
XS GIS Cut Line= 3
     1565081.122       358690.79     1565056.816      358954.679
     1565338.066      359499.817
#Sta/Elev= 30
       0  697.78    68.7  688.72     157  678.31   186.5  675.13   196.3  674.41
   206.1   674.1   215.9   673.3   225.8  671.67   235.6  669.71   255.2  664.98
   274.7  659.38   284.5  658.16   294.2     658     304  659.03   323.4  665.12
   325.2  665.48   333.2  667.07   352.6  668.49   401.3  672.66   420.8  673.92
   440.3  674.68   498.7   675.7   547.4  676.95   566.8  677.19   596.1  676.79
   625.3   676.8   683.7  676.22   703.2  676.31   742.1  677.42   878.4   680.6
#Mann= 3 , 0 , 0
       0      .1       0   255.2    .045       0   325.2      .1       0
Bank Sta=255.2,325.2
XS Rating Curve= 0 ,0
Exp/Cntr=0.3,0.1